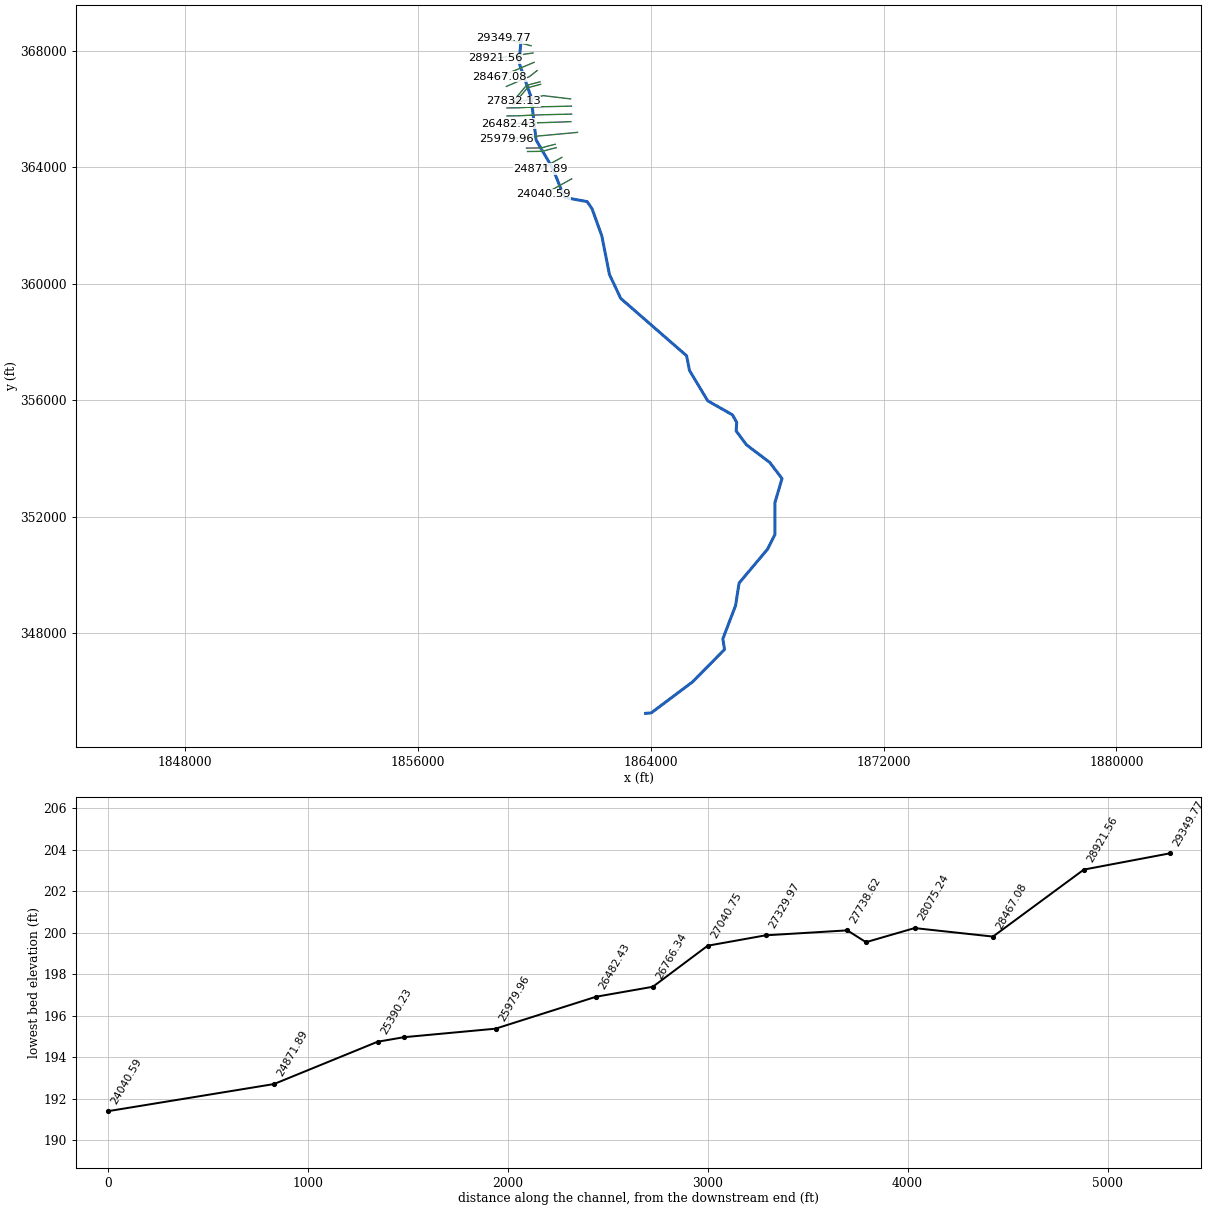
--- bridge.prj (project) ---

Proj Title=Bridge Creek to Leith Creek
Current Plan=p01
Default Exp/Contr=0.3,0.1
English Units
Geom File=g02
Flow File=f01
Plan File=p01
Y Axis Title=Elevation
X Axis Title(PF)=Main Channel Distance
X Axis Title(XS)=Station
BEGIN DESCRIPTION:
Approximate Study of Bridge Creek and Big Branch
END DESCRIPTION:
DSS Export Rating Curves= 0
DSS Export Rating Curve Sorted= 0
DSS Export Volume Flow Curves= 0
DXF OffsetX= 0
DXF OffsetY= 0
DXF ScaleX= 1
DXF ScaleY= 10

--- bridge.p01 (plan) ---

Plan Title=Bridge Plan
Version=September 1998 Version 2.2
Short Identifier=1
Geom File=g02
Flow File=f01
Interactive Comp Mode
Subcritical Flow
K Sum by GR= 0
Std Step Tol= 0.01
Critical Tol= 0.01
Num of Std Step Trials= 20
Max Error Tol= 0.3
Flow Tol Ratio= 0.001
Log Output Level= 0
Friction Slope Method= 1
Parabolic Critical Depth
Global Vel Dist= 0 , 0 , 0
Global Log Level= 0
Encroach Param=-1 ,0,0, 2
Encroach River=Branch
Encroach Reach=01
Encroach Node=29349.77
       4      .7
Encroach Node=28921.56
       4      .7
Encroach Node=28467.08
       4      .7
Encroach Node=28075.24
       4      .7
Encroach Node=27832.13
       4      .7
Encroach Node=27784.59
       4      .7
Encroach Node=27738.62
       4      .7
Encroach Node=27329.97
       4      .7
Encroach Node=27040.75
       4      .7
Encroach Node=26913.42
       4      .7
Encroach Node=26766.34
       4      .7
Encroach Node=26482.43
       4      .7
Encroach Node=25979.96
       4      .7
Encroach Node=25522.58
       4      .5
Encroach Node=25453.51
       4      .5
Encroach Node=25390.23
       4      .5
Encroach Node=24871.89
       4      .7
Encroach Node=24040.59
       4      .7
Encroach Node=23497.81
       4      .7
Encroach Node=23355.75
       4      .7
Encroach Node=23234.31
       4      .7
Encroach Node=22689.94
       4      .7
Encroach Node=21248.40
       4      .7
Encroach Node=19781.87
       4      .7
Encroach Node=18479.08
       4      .7
Encroach Node=17130.69
       4      .7
Encroach Node=16237.34
       4      .7
Encroach Node=15881.32
       4      .7
Encroach Node=15824.28
       4      .7
Encroach Node=15761.12
       4      .7
Encroach Node=15605.88
       4      .7
Encroach Node=14174.54
       4      .7
Encroach Node=13325.81
       4      .7
Encroach Node=12309.25
       4      .7
Encroach Node=11090.38
       4      .7
Encroach Node=10900.67
       4      .7
Encroach Node=10526.78
       4      .7
Encroach Node=10413.42
       4      .7
Encroach Node=10238.63
       4      .7
Encroach Node=9348.119
       4      .7
Encroach Node=8220.093
       4      .7
Encroach Node=6465.662
       4      .7
Encroach Node=5285.766
       4      .7
Encroach Node=3636.885
       4      .7
Encroach Node=3492.557
       1  646.93   683.6
Encroach Node=3418.85
       1  646.93   683.6
Encroach Node=3345.369
       1  646.93   683.6
Encroach Node=3165.191
       4      .7
Encroach Node=2402.302
       4      .7
Encroach Node=790.421
       4      .7
Encroach River=Bridge
Encroach Reach=Upper
Encroach Node=47941.55
       4      .7
Encroach Node=47139.47
       4      .7
Encroach Node=46447.44
       4      .7
Encroach Node=45948.17
       4      .7
Encroach Node=45628.34
       4      .7
Encroach Node=44674.82
       4      .7
Encroach Node=44618.41
       4      .7
Encroach Node=44576.00
       4      .7
Encroach Node=43666.57
       4      .7
Encroach Node=43100.01
       4      .7
Encroach Node=43025.74
       4      .7
Encroach Node=42938.20
       4      .7
Encroach Node=42230.55
       4      .7
Encroach Node=41357.80
       4      .7
Encroach Node=40239.21
       4      .7
Encroach Node=40006.87
       4      .7
Encroach Node=39938.02
       4      .7
Encroach Node=39880.65
       4      .7
Encroach Node=39519.29
       4      .7
Encroach Node=39151.26
       4      .7
Encroach Node=38764.91
       4      .7
Encroach Node=38644.00
       4      .7
Encroach Node=38504.79
       4      .7
Encroach Node=37857.93
       4      .7
Encroach Node=36740.31
       4      .7
Encroach Node=36561.67
       1  614.03  656.33
Encroach Node=36501.73
       1  614.03  656.33
Encroach Node=36427.51
       1  614.03  656.33
Encroach Node=36243.94
       1  672.31  863.58
Encroach Node=34450.17
       1  526.17  717.44
Encroach Node=32976.05
       4      .7
Encroach Node=32042.03
       4      .7
Encroach Node=31310.59
       4      .7
Encroach Node=31192.96
       4      .7
Encroach Node=24781.27
       4      .7
Encroach Node=24614.45
       4      .7
Encroach Node=24034.29
       4      .7
Encroach Node=23331.04
       4      .7
Encroach Node=22384.44
       4      .7
Encroach Node=21520.11
       4      .7
Encroach Node=21126.50
       4      .7
Encroach Node=20313.04
       4      .7
Encroach Node=18878.03
       4      .7
Encroach Node=18813.32
       4      .7
Encroach Node=18736.72
       4      .7
Encroach Node=17476.14
       4      .7
Encroach Node=16419.06
       4      .7
Encroach Node=15697.09
       4      .7
Encroach Node=15590.30
       4      .7
Encroach Node=15524.23
       4      .7
Encroach Node=14068.20
       4      .7
Encroach Node=12341.15
       4      .7
Encroach Node=11230.99
       4      .7
Encroach Node=9625.100
       4      .7
Encroach Node=9211.982
       4      .7
Encroach Node=9117.01
       4      .7
Encroach Node=9025.128
       4      .7
Encroach Node=7925.282
       4      .7
Encroach Reach=Lower
Encroach Node=6222.692
       4      .7
Encroach Node=6144.58
       4      .7
Encroach Node=6044.962
       4      .7
Encroach Node=5113.489
       4      .7
Encroach Node=4499.303
       4      .7
Encroach Node=4387.80
       4      .7
Encroach Node=4267.838
       4      .7
Encroach Node=4115.594
       4      .7
Encroach Node=2190.713
       4      .7

--- bridge.f01 (steady flow) ---

Flow Title=Bridge Flow Data
Version=September 1998 Version 2.2
Number of Profiles= 2
Profile Names=100yr,floodway
River Rch & RM=Branch,01              ,29349.77
     993     993
River Rch & RM=Branch,01              ,22689.94
    1086    1086
River Rch & RM=Branch,01              ,15605.88
    1132    1132
River Rch & RM=Branch,01              ,10413.42
    1446    1446
River Rch & RM=Branch,01              ,8220.093
    1526    1526
River Rch & RM=Branch,01              ,3165.191
    1550    1550
River Rch & RM=Bridge,Upper           ,47941.55
     224     224
River Rch & RM=Bridge,Upper           ,40239.21
     750     750
River Rch & RM=Bridge,Upper           ,38504.79
     889     889
River Rch & RM=Bridge,Upper           ,36243.94
    1044    1044
River Rch & RM=Bridge,Upper           ,31051.00
    1222    1222
River Rch & RM=Bridge,Upper           ,28223.21
    1251    1251
River Rch & RM=Bridge,Upper           ,26551.63
    1261    1261
River Rch & RM=Bridge,Upper           ,25501.89
    1498    1498
River Rch & RM=Bridge,Upper           ,24034.29
    1563    1563
River Rch & RM=Bridge,Upper           ,18736.72
    1628    1628
River Rch & RM=Bridge,Upper           ,15524.23
    1648    1648
River Rch & RM=Bridge,Upper           ,14068.20
    1733    1733
River Rch & RM=Bridge,Upper           ,9025.128
    1751    1751
River Rch & RM=Bridge,Lower           ,6222.692
    2574    2574
River Rch & RM=Bridge,Lower           ,4115.594
    2592    2592
Boundary for River Rch & Prof#=Branch,01              , 1
Up Type= 0
Dn Type= 0
Boundary for River Rch & Prof#=Branch,01              , 2
Up Type= 0
Dn Type= 0
Boundary for River Rch & Prof#=Bridge,Upper           , 1
Up Type= 0
Dn Type= 0
Boundary for River Rch & Prof#=Bridge,Upper           , 2
Up Type= 0
Dn Type= 0
Boundary for River Rch & Prof#=Bridge,Lower           , 1
Up Type= 0
Dn Type= 3
Dn Slope=.0012
Boundary for River Rch & Prof#=Bridge,Lower           , 2
Up Type= 0
Dn Type= 3
Dn Slope=.0012
DSS Import GetInterval= 0
DSS Import GetPeak= 0
DSS Import FillOption= 0

--- bridge.g02 (geometry) ---

Geom Title=Modified Geometry
Version=September 1998 Version 2.2

Junct Name=2
Junct Desc=, 0 , 0 ,-1
Up River,Reach=Branch          ,01
Up River,Reach=Bridge          ,Upper
Dn River,Reach=Bridge          ,Lower
Junc L&A=791.56,0
Junc L&A=1702.59,0

River Reach=Branch          ,01
Junct Up Dn=                ,2
Reach XY= 30
     1859555.152      368401.147     1859483.701       367584.94
     1859894.749      366411.413     1860067.138      364939.131
     1860639.692      363956.704     1861039.454      362963.324
     1861823.658      362817.572      1861990.47      362572.531
     1862326.197      361639.571     1862586.652      360318.928
     1862974.804      359494.918     1865236.743       357524.73
     1865338.228      357016.801     1865961.762      355978.251
      1866813.98      355494.065     1866957.733      355236.246
     1866938.739      354944.178     1867291.822      354467.228
      1868091.83      353862.003     1868514.599      353306.091
     1868272.024      352483.606     1868270.877      351384.723
     1868016.351       350880.48      1867040.12      349719.524
     1866918.518      348942.983     1866481.333      347801.967
     1866540.077      347437.777     1865447.995      346330.661
     1864023.109      345261.574     1863830.082      345243.287

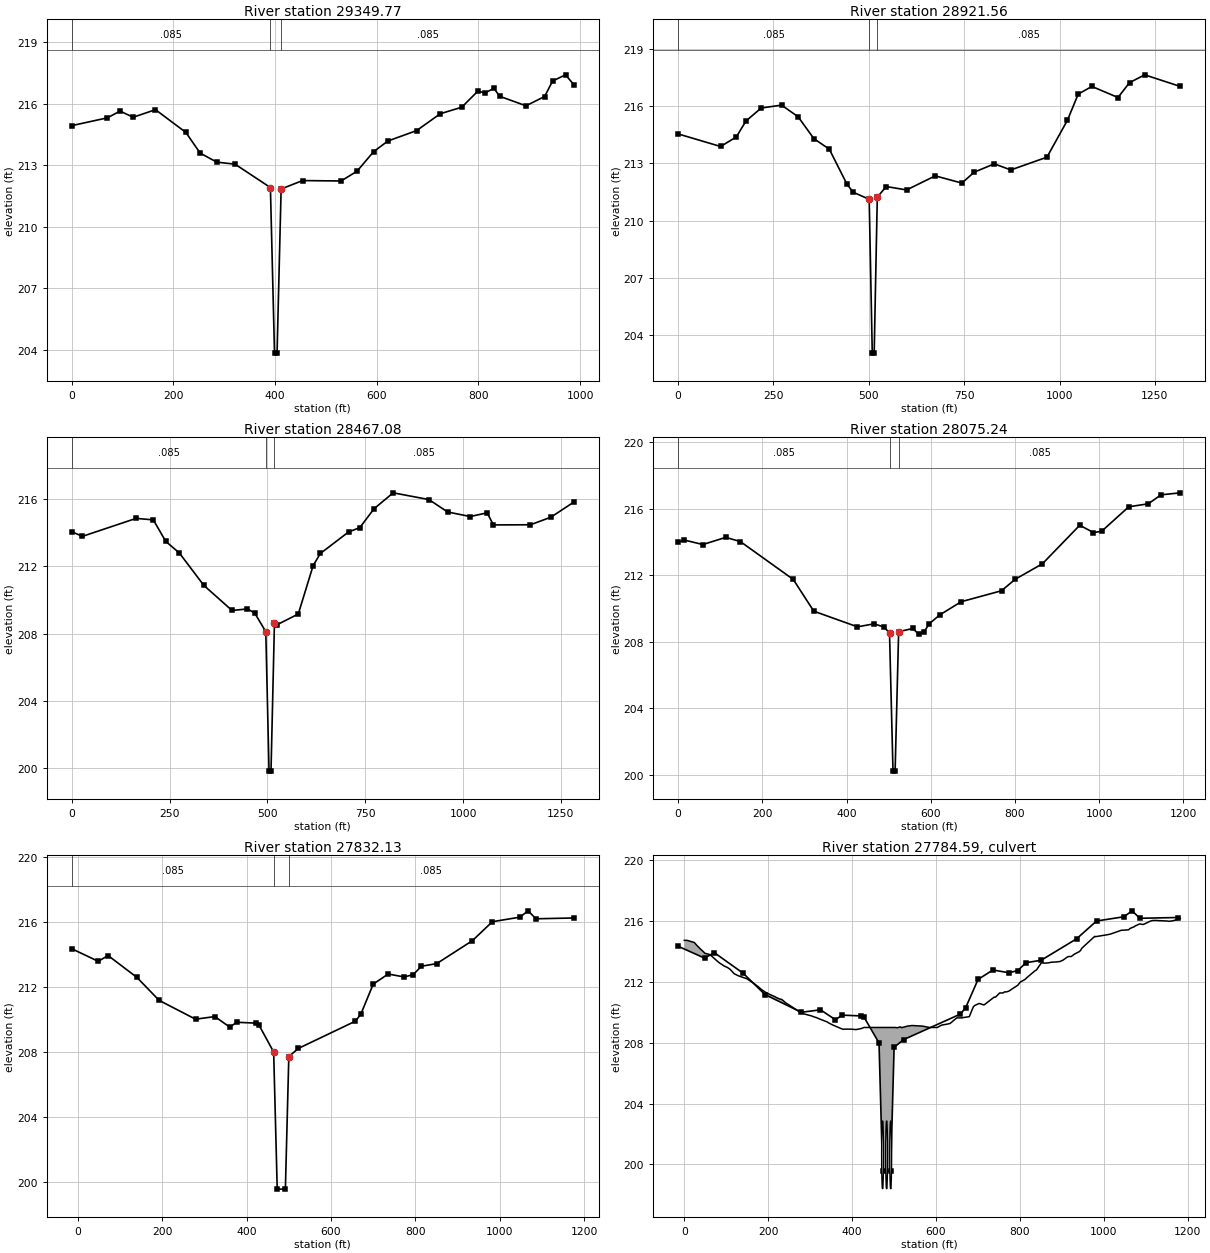
Type RM Length L Ch R = 1 ,29349.77,391.98,428.2,459.01
XS GIS Cut Line= 2
     1859896.262      368171.084     1858942.023      368425.969
#Sta/Elev= 30
       0  214.93   70.08  215.31   95.19  215.64  121.01  215.34  164.88  215.71
   224.6   214.6  252.75  213.59  285.44  213.15  321.39  213.05  390.91  211.91
  398.99  203.83  403.99  203.83     412  211.84  454.19  212.25  529.91  212.23
  561.44  212.71  593.85  213.66  621.97  214.18  678.54  214.69   724.9  215.51
  767.24  215.83  798.81  216.61  813.11  216.53  830.49  216.75     842  216.36
  893.58   215.9   930.1  216.35  946.04  217.11  971.32  217.41  987.69  216.93
#Mann= 3 , 0 , 0
       0    .085       0  390.91    .055       0     412    .085       0
Bank Sta=390.91,412
Exp/Cntr=.3,.1

Type RM Length L Ch R = 1 ,28921.56,440.71,454.48,477.1
XS GIS Cut Line= 2
     1859965.284      367923.417     1858661.985      367736.651
#Sta/Elev= 30
       0  214.55  111.31  213.89  152.48  214.39  178.02  215.23  217.92  215.91
  271.22  216.06  314.59  215.45  356.02   214.3  396.37  213.75   442.5  211.92
  458.93  211.49  500.94  211.12  509.01  203.05  514.01  203.05  522.19  211.23
  545.62  211.79  598.91  211.61  674.07  212.35  744.07  211.97  775.93  212.54
  828.91  212.98  872.27  212.66  966.98  213.33 1020.77  215.27 1048.95  216.64
 1084.85  217.04  1153.2  216.46 1183.46  217.24  1223.2  217.65 1316.61  217.04
#Mann= 3 , 0 , 0
       0    .085       0  500.94    .055       0  522.19    .085       0
Bank Sta=500.94,522.19
Exp/Cntr=.3,.1

Type RM Length L Ch R = 1 ,28467.08,391.56,391.84,392.05
XS GIS Cut Line= 2
     1859999.619      367601.359     1858816.775      367104.425
#Sta/Elev= 30
       0  214.07   27.48  213.79  164.75  214.86   208.7  214.77  240.46  213.49
   275.2   212.8  337.39  210.88  409.72  209.38  449.09  209.47  467.52  209.23
  495.99  208.12  504.29  199.82  509.29  199.82  518.12  208.65  525.55  208.54
  579.01  209.17  616.96  212.05  635.33  212.77   707.4  214.05  736.22  214.31
  772.44  215.43  821.41  216.38  912.65  215.98  960.57  215.24 1018.18  214.97
 1061.69  215.19 1077.36  214.47 1172.24  214.48 1224.42  214.93 1282.99  215.83
#Mann= 3 , 0 , 0
       0    .085       0  495.99    .055       0  518.12    .085       0
Bank Sta=495.99,518.12
Exp/Cntr=.3,.1

Type RM Length L Ch R = 1 ,28075.24,246.72,243.1,271.67
XS GIS Cut Line= 3
     1860100.892      367316.755      1859839.42      367111.393
     1859047.697      366774.403
#Sta/Elev= 30
       0     214   14.63  214.13    58.8  213.86  113.11  214.29  147.77  214.04
  273.53  211.76  322.28  209.85     426  208.91  465.67  209.09  489.73  208.89
  502.16  208.53  510.46  200.23  515.46  200.23  523.85  208.62  557.65  208.81
  571.16  208.47  584.53  208.62  596.72   209.1  621.77  209.63  672.49  210.42
  768.19  211.08  801.26  211.78  865.31   212.7  954.05  215.02  986.63  214.58
 1006.22  214.66 1070.51  216.13 1117.03  216.31 1146.99  216.85 1192.94  216.97
#Mann= 3 , 0 , 0
       0    .085       0  502.16    .055       0  523.85    .085       0
Bank Sta=502.16,523.85
Exp/Cntr=.5,.3

Type RM Length L Ch R = 1 ,27832.13,89.16,93.51,89.36
XS GIS Cut Line= 3
      1860203.82      366932.657     1859737.268      366810.782
     1859282.534        366267.7
#Sta/Elev= 30
  -14.68  214.35   48.42  213.57   71.58  213.93  140.17  212.58  192.58  211.17
  279.01  210.01  324.69  210.17  360.29  209.52   376.4  209.82  421.45  209.77
  428.92  209.67  464.22  207.99  472.66  199.55     492  199.55  500.16  207.71
  522.77  208.21  658.17  209.89  670.91  210.32  700.29  212.17   735.7  212.79
  773.68  212.61  794.85  212.75  814.65  213.27  850.71  213.43  935.16  214.84
  982.69  216.01 1047.99  216.29  1067.4  216.68 1085.99  216.19 1175.85  216.24
#Mann= 3 , 0 , 0
  -14.68    .085       0  464.22    .055       0  500.16    .085       0
Bank Sta=464.22,500.16
Exp/Cntr=.5,.3

Type RM Length L Ch R = 2 ,27784.59,,,
BEGIN DESCRIPTION:
Woodlawn St. (assumed same as SR 1614)
END DESCRIPTION:
Bridge Culvert--1,0,-1,-1, 0
Deck Dist Width WeirC Skew NumUp NumDn MinLoCord MaxHiCord MaxSubmerge Is_Ogee
37.04,21,2.6,0,153,153,208.87,,.95,0,0,0,,
       0    3.78     6.6   13.65   21.78   24.01   29.18   40.39   45.67   48.95
    59.2   62.14   77.08   84.09   95.22  103.13  109.39  119.17  128.71  142.57
  148.01  149.64  154.21  162.58  176.23  185.21  193.32   199.3  216.37  220.79
  227.84  232.56  242.32  248.63  270.85  284.41  285.73  298.93  299.99  312.98
  313.25  314.06   320.6  341.82  342.64  352.65  375.24  378.99  381.66  398.07
  409.15   422.1  428.35  435.15  445.96  449.22  458.97  465.48  469.52  474.01
  475.77  482.45  490.71  498.95   502.9  507.21  515.37  518.69  521.05  533.69
   538.6  539.36  542.32  560.16   567.6  584.35  588.75  593.41  603.27  612.19
  614.37  624.75  633.39  646.75  649.57  662.47  663.78  664.58  679.39  686.88
  689.37  692.71  702.96  714.42  714.52  737.57  738.88   739.6  742.04  751.89
  759.86  763.41  768.04  773.81  782.31  794.72  801.12  811.85  815.74  818.05
  836.48  839.67  842.41  851.23  859.31  868.65  874.61   887.5  896.24  897.97
  902.93  913.49  917.47  922.12   929.8   941.9  945.27  945.91  947.62  978.29
  980.21 1008.92 1015.75  1041.7 1059.09 1062.46 1072.91  1074.9 1075.83 1076.92
 1085.58 1093.77  1098.1 1109.97    1115 1123.51 1128.41 1151.34 1155.21 1163.66
 1172.35 1175.08 1182.38
  214.74  214.74  214.74  214.68  214.62   214.6  214.43  214.12  213.99  213.89
  213.82  213.78  213.41  213.25  213.05  212.95  212.83  212.54  212.41  212.28
  212.23  212.21  212.12  211.97  211.69  211.48  211.33  211.24  211.03  210.96
  210.88  210.85  210.62  210.51  210.11  209.93   209.9   209.8   209.8  209.67
  209.67  209.67  209.59  209.36  209.33  209.19  208.92  208.89   208.9   208.9
  208.87  208.94  209.01  209.01  209.01  209.01  209.01  209.01  209.01  209.01
  209.01  209.01  209.01  209.01  209.01  208.99  209.05  208.99  209.02  209.11
  209.12  209.12  209.14  209.11   209.1  209.01  209.01  209.01  209.01  209.15
  209.17  209.22  209.27  209.57  209.64  209.64  209.65  209.66  209.72  210.23
  210.38  210.46  210.59  210.49  210.49  210.98  211.01     211  211.01  211.28
  211.28  211.35  211.35   211.4  211.56  211.78     212  212.16  212.26  212.32
  212.75  212.79  212.91  213.26  213.24  213.26   213.3  213.32  213.35  213.38
  213.44  213.65  213.68  213.67  213.83     214   214.1  214.14  214.22     215
  214.98  215.11  215.15   215.4  215.43  215.52  215.64  215.69   215.7  215.71
  215.82  215.78  215.83  215.99  216.04  216.05  216.04  216.01  215.99  216.02
  216.08   216.1  216.18
                                                                                
                                                                                
                                                                                
                                                                                
                                                                                
                                                                                
                                                                                
                                                                                
                                                                                
                                                                                
                                                                                
                                                                                
                                                                                
                                                                                
                                                                                
                        
       0    3.78     6.6   13.65   21.78   24.01   29.18   40.39   45.67   48.95
    59.2   62.14   77.08   84.09   95.22  103.13  109.39  119.17  128.71  142.57
  148.01  149.64  154.21  162.58  176.23  185.21  193.32   199.3  216.37  220.79
  227.84  232.56  242.32  248.63  270.85  284.41  285.73  298.93  299.99  312.98
  313.25  314.06   320.6  341.82  342.64  352.65  375.24  378.99  381.66  398.07
  409.15   422.1  428.35  435.15  445.96  449.22  458.97  465.48  469.52  474.01
  475.77  482.45  490.71  498.95   502.9  507.21  515.37  518.69  521.05  533.69
   538.6  539.36  542.32  560.16   567.6  584.35  588.75  593.41  603.27  612.19
  614.37  624.75  633.39  646.75  649.57  662.47  663.78  664.58  679.39  686.88
  689.37  692.71  702.96  714.42  714.52  737.57  738.88   739.6  742.04  751.89
  759.86  763.41  768.04  773.81  782.31  794.72  801.12  811.85  815.74  818.05
  836.48  839.67  842.41  851.23  859.31  868.65  874.61   887.5  896.24  897.97
  902.93  913.49  917.47  922.12   929.8   941.9  945.27  945.91  947.62  978.29
  980.21 1008.92 1015.75  1041.7 1059.09 1062.46 1072.91  1074.9 1075.83 1076.92
 1085.58 1093.77  1098.1 1109.97    1115 1123.51 1128.41 1151.34 1155.21 1163.66
 1172.35 1175.08 1182.38
  214.74  214.74  214.74  214.68  214.62   214.6  214.43  214.12  213.99  213.89
  213.82  213.78  213.41  213.25  213.05  212.95  212.83  212.54  212.41  212.28
  212.23  212.21  212.12  211.97  211.69  211.48  211.33  211.24  211.03  210.96
  210.88  210.85  210.62  210.51  210.11  209.93   209.9   209.8   209.8  209.67
  209.67  209.67  209.59  209.36  209.33  209.19  208.92  208.89   208.9   208.9
  208.87  208.94  209.01  209.01  209.01  209.01  209.01  209.01  209.01  209.01
  209.01  209.01  209.01  209.01  209.01  208.99  209.05  208.99  209.02  209.11
  209.12  209.12  209.14  209.11   209.1  209.01  209.01  209.01  209.01  209.15
  209.17  209.22  209.27  209.57  209.64  209.64  209.65  209.66  209.72  210.23
  210.38  210.46  210.59  210.49  210.49  210.98  211.01     211  211.01  211.28
  211.28  211.35  211.35   211.4  211.56  211.78     212  212.16  212.26  212.32
  212.75  212.79  212.91  213.26  213.24  213.26   213.3  213.32  213.35  213.38
  213.44  213.65  213.68  213.67  213.83     214   214.1  214.14  214.22     215
  214.98  215.11  215.15   215.4  215.43  215.52  215.64  215.69   215.7  215.71
  215.82  215.78  215.83  215.99  216.04  216.05  216.04  216.01  215.99  216.02
  216.08   216.1  216.18
                                                                                
                                                                                
                                                                                
                                                                                
                                                                                
                                                                                
                                                                                
                                                                                
                                                                                
                                                                                
                                                                                
                                                                                
                                                                                
                                                                                
                                                                                
                        
Multiple Barrel Culv=1,4.5,,21,.027,.7,1,2,2,198.38,198.36, 3,Culvert #1  , 0 ,37.04
  472.66  472.66  482.33  482.33     492     492
BC Design=,, 0 ,, 0 ,,,,,,

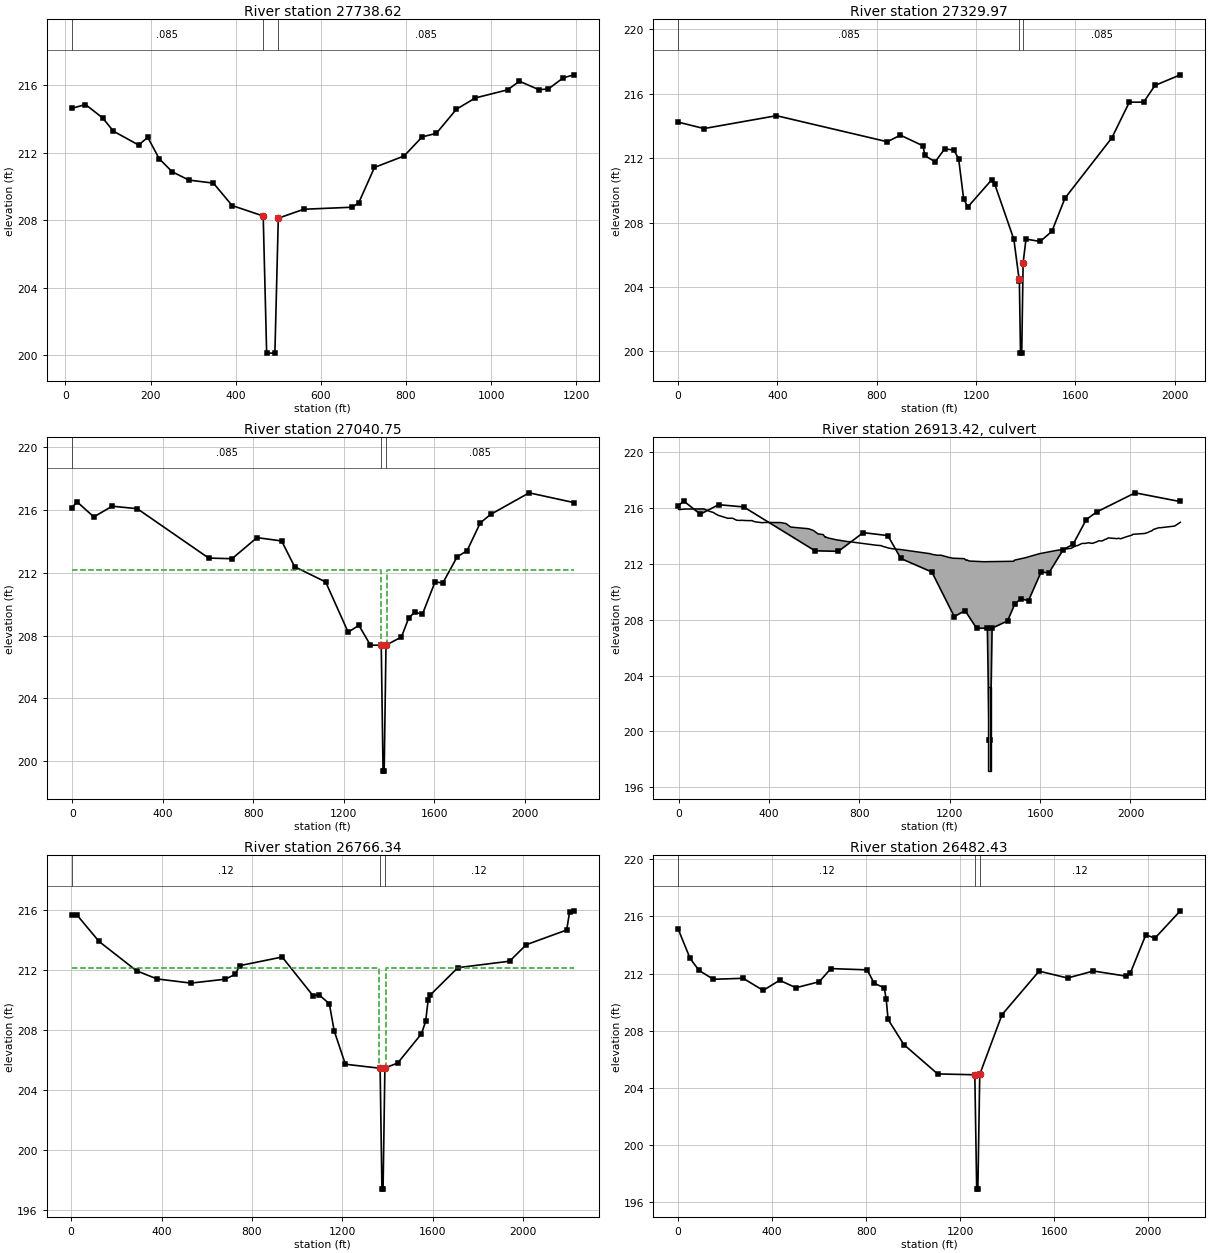
Type RM Length L Ch R = 1 ,27738.62,400.77,408.66,357.21
XS GIS Cut Line= 3
     1860226.855      366846.698     1859771.048       366727.63
     1859316.314      366184.549
#Sta/Elev= 30
   14.68  214.63   47.14  214.86   87.26  214.07  112.75  213.28  171.79  212.46
  193.46  212.91  220.23  211.65  250.38  210.88  289.74  210.38  347.61   210.2
  391.53  208.87  464.53  208.25  472.66  200.12     492  200.12     500  208.12
   559.9  208.65  673.34  208.77  688.67  209.02   725.9  211.13  795.53  211.81
  837.73  212.94  871.16  213.15  918.31  214.58  962.73  215.25 1038.55  215.73
 1066.38  216.24 1111.82  215.74 1134.18  215.78 1169.09  216.44  1194.1  216.62
#Mann= 3 , 0 , 0
   14.68    .085       0  464.53    .055       0     500    .085       0
Bank Sta=464.53,500
Exp/Cntr=.5,.3

Type RM Length L Ch R = 1 ,27329.97,294.65,289.22,273.21
XS GIS Cut Line= 4
     1861252.179      366345.654     1860314.454      366457.714
      1859510.55      366246.587     1859282.534      366150.769
#Sta/Elev= 30
       0  214.24  104.45  213.84  396.14  214.64   842.7  213.02  895.38  213.43
  987.32  212.76  993.03  212.17 1035.32  211.77 1073.49  212.57 1110.87  212.51
 1130.06  211.95 1150.11  209.48 1166.58  208.96 1263.96  210.67 1275.54  210.38
 1352.48  206.95 1373.54  204.47 1374.68  204.34 1379.14  199.88 1384.14  199.88
 1389.76   205.5 1401.32  206.97 1458.29  206.82 1505.67  207.45 1558.15  209.51
 1747.04  213.26 1817.62  215.48 1875.14  215.48 1920.77  216.52 2022.89  217.18
#Mann= 3 , 0 , 0
       0    .085       0 1373.54    .055       0 1389.76    .085       0
Bank Sta=1373.54,1389.76
Exp/Cntr=.5,.3

Type RM Length L Ch R = 1 ,27040.75,275.15,274.4,274.02
XS GIS Cut Line= 5
      1861284.44       366098.75     1860301.772      366075.353
     1859833.834      366058.641     1859466.169      366038.586
      1859065.08      366035.244
#Sta/Elev= 30
   -2.47  216.13   21.79   216.5   95.63  215.55  176.94  216.23  287.72  216.07
  603.52  212.93  706.71  212.89  816.93  214.23  925.89  214.02  983.48  212.38
 1120.73  211.41 1220.02  208.22 1267.73  208.65 1318.65  207.39 1366.43  207.39
 1374.44  199.38 1379.44  199.38 1387.45  207.39 1455.63  207.91  1488.3  209.13
 1513.92  209.48 1548.73  209.37 1604.79  211.43 1638.13  211.33 1702.47  213.02
 1745.67  213.39 1804.34  215.17 1850.41  215.71 2020.53  217.08 2218.03  216.46
#Mann= 3 , 0 , 0
   -2.47    .085       0 1366.43    .055       0 1387.45    .085       0
#XS Ineff= 2 , 0
       0 1363.61  212.15 1390.28       0  212.15
Bank Sta=1366.43,1387.45
Exp/Cntr=.5,.3

Type RM Length L Ch R = 2 ,26913.42,,,
BEGIN DESCRIPTION:
US 74-501 (NCDOT 82 2004)
END DESCRIPTION:
Bridge Culvert--1,0,-1,-1, 0
Deck Dist Width WeirC Skew NumUp NumDn MinLoCord MaxHiCord MaxSubmerge Is_Ogee
89.33,76,2.6,0,135,135,212.15,,.95,0,0,0,,
       0    3.25   23.17    23.3   24.31   43.53  111.46  136.22  138.92  152.77
  159.33  175.04  216.18  218.86  219.97  239.04  256.33  272.66  278.77  281.46
  299.12  304.55  305.45  321.54  323.38   336.7  363.03  370.74  373.86  386.25
  390.38  390.77  429.58  446.93  452.42  471.88  474.29  474.63  474.93  495.93
  546.76  549.08  555.56  570.53   574.6  596.08  611.08  617.11  637.52  639.84
  642.19  648.47  650.38  663.81  705.76  706.68   731.5   752.1  761.81  770.82
  869.36  874.15  896.61  902.79  907.01  915.13  929.84  937.16  942.98  982.95
 1105.69 1107.88 1114.82 1120.28 1145.61 1159.83 1199.85 1200.32 1200.57 1202.12
  1214.2 1263.41 1263.47 1263.67 1272.57 1275.15 1276.12 1283.96 1285.28 1349.19
 1482.24 1484.06  1486.4 1536.01 1595.82 1666.04 1713.83 1737.61 1737.69 1737.79
 1758.06  1764.9 1777.99 1785.86 1800.13 1814.58 1819.39 1829.55 1832.65 1834.81
 1853.63 1859.03 1874.09 1887.73 1891.89 1902.89 1910.89  1924.2  1941.4  1947.1
 1955.94 1984.68 2005.88 2008.12 2009.94 2061.85 2066.95 2078.11 2087.37 2093.42
 2101.66 2127.01 2131.71 2195.36  2220.5
   215.9  215.88  215.91  215.91  215.92  215.92  215.93  215.76  215.74  215.68
  215.61  215.47  215.26  215.25  215.26  215.26  215.12   215.1  215.12  215.11
  215.09  215.08  215.09  215.09   215.1  215.01  214.96  214.94  214.95  214.96
  214.96  214.96  214.95  214.95  214.95  214.89  214.88  214.88  214.88  214.63
  214.55  214.55  214.54  214.52  214.51  214.39  214.21  214.14   214.1  214.09
  214.04   213.9  213.92  213.84  213.69   213.7  213.63  213.58  213.59  213.55
  213.34  213.33   213.3  213.25  213.23   213.2  213.12  213.11  213.08  213.02
  212.74  212.74  212.72  212.68  212.61  212.62  212.44  212.44  212.44  212.44
   212.4  212.37  212.37  212.37  212.25  212.26  212.28  212.21   212.2  212.15
  212.18  212.21  212.26  212.44  212.72  212.94  213.06  213.11  213.11  213.11
  213.29   213.3   213.4  213.46  213.46  213.51  213.49  213.47  213.46  213.48
  213.59  213.65  213.63  213.75  213.76  213.86  213.84  213.82   213.8  213.83
  213.79  213.95  214.05  214.07  214.11  214.17  214.19  214.25  214.33  214.35
  214.46  214.59  214.58   214.7  214.97
                                                                                
                                                                                
                                                                                
                                                                                
                                                                                
                                                                                
                                                                                
                                                                                
                                                                                
                                                                                
                                                                                
                                                                                
                                                                                
                                        
       0    3.25   23.17    23.3   24.31   43.53  111.46  136.22  138.92  152.77
  159.33  175.04  216.18  218.86  219.97  239.04  256.33  272.66  278.77  281.46
  299.12  304.55  305.45  321.54  323.38   336.7  363.03  370.74  373.86  386.25
  390.38  390.77  429.58  446.93  452.42  471.88  474.29  474.63  474.93  495.93
  546.76  549.08  555.56  570.53   574.6  596.08  611.08  617.11  637.52  639.84
  642.19  648.47  650.38  663.81  705.76  706.68   731.5   752.1  761.81  770.82
  869.36  874.15  896.61  902.79  907.01  915.13  929.84  937.16  942.98  982.95
 1105.69 1107.88 1114.82 1120.28 1145.61 1159.83 1199.85 1200.32 1200.57 1202.12
  1214.2 1263.41 1263.47 1263.67 1272.57 1275.15 1276.12 1283.96 1285.28 1349.19
 1482.24 1484.06  1486.4 1536.01 1595.82 1666.04 1713.83 1737.61 1737.69 1737.79
 1758.06  1764.9 1777.99 1785.86 1800.13 1814.58 1819.39 1829.55 1832.65 1834.81
 1853.63 1859.03 1874.09 1887.73 1891.89 1902.89 1910.89  1924.2  1941.4  1947.1
 1955.94 1984.68 2005.88 2008.12 2009.94 2061.85 2066.95 2078.11 2087.37 2093.42
 2101.66 2127.01 2131.71 2195.36  2220.5
   215.9  215.88  215.91  215.91  215.92  215.92  215.93  215.76  215.74  215.68
  215.61  215.47  215.26  215.25  215.26  215.26  215.12   215.1  215.12  215.11
  215.09  215.08  215.09  215.09   215.1  215.01  214.96  214.94  214.95  214.96
  214.96  214.96  214.95  214.95  214.95  214.89  214.88  214.88  214.88  214.63
  214.55  214.55  214.54  214.52  214.51  214.39  214.21  214.14   214.1  214.09
  214.04   213.9  213.92  213.84  213.69   213.7  213.63  213.58  213.59  213.55
  213.34  213.33   213.3  213.25  213.23   213.2  213.12  213.11  213.08  213.02
  212.74  212.74  212.72  212.68  212.61  212.62  212.44  212.44  212.44  212.44
   212.4  212.37  212.37  212.37  212.25  212.26  212.28  212.21   212.2  212.15
  212.18  212.21  212.26  212.44  212.72  212.94  213.06  213.11  213.11  213.11
  213.29   213.3   213.4  213.46  213.46  213.51  213.49  213.47  213.46  213.48
  213.59  213.65  213.63  213.75  213.76  213.86  213.84  213.82   213.8  213.83
  213.79  213.95  214.05  214.07  214.11  214.17  214.19  214.25  214.33  214.35
  214.46  214.59  214.58   214.7  214.97
                                                                                
                                                                                
                                                                                
                                                                                
                                                                                
                                                                                
                                                                                
                                                                                
                                                                                
                                                                                
                                                                                
                                                                                
                                                                                
                                        
Multiple Barrel Culv=2,6,7,76,.012,.4,1,8,1,197.16,197.14, 2,Culvert #1  , 0 ,89.33
 1373.11 1373.11 1380.78 1380.78
BC Design=,, 0 ,, 0 ,,,,,,

Type RM Length L Ch R = 1 ,26766.34,287.13,283.91,281.23
XS GIS Cut Line= 5
     1861287.782      365824.672     1860305.114      365801.275
     1859837.177      365784.563     1859469.512      365764.509
     1859068.422      365761.166
#Sta/Elev= 30
    2.47  215.68   25.53  215.69  123.39  213.92  289.48  211.96  379.52  211.42
   529.7  211.14  681.16   211.4  726.72  211.73  744.67   212.3  933.32  212.88
 1069.62   210.3 1095.58  210.37 1141.85  209.76 1163.41  207.95 1212.78  205.73
 1366.39  205.46 1374.45   197.4 1379.45   197.4 1387.53  205.48 1444.27  205.81
 1548.66  207.75 1567.66  208.58 1578.85  210.03 1589.01  210.36 1710.29  212.17
 1938.92   212.6 2012.56   213.7 2191.28  214.68 2204.11  215.87 2222.97  215.96
#Mann= 3 , 0 , 0
    2.47     .12       0 1366.39    .055       0 1387.53     .12       0
#XS Ineff= 2 , 0
       0 1363.61  212.15 1390.28       0  212.15
Bank Sta=1366.39,1387.53
Exp/Cntr=.5,.3

Type RM Length L Ch R = 1 ,26482.43,460.62,502.47,470.92
XS GIS Cut Line= 2
     1861264.386      365563.964     1859128.586      365490.431
#Sta/Elev= 30
       0  215.12   51.08  213.06   88.94  212.22  150.05   211.6  276.97  211.67
  361.78  210.82  431.78  211.53  501.46  211.01  600.88  211.43  649.83  212.35
   804.2  212.26  834.41  211.32  877.39     211  885.64  210.19  893.45  208.79
  960.75  207.03 1104.48  204.98 1262.58  204.92 1270.58  196.92 1275.58  196.92
 1283.61  204.95 1378.11  209.12  1536.2  212.17 1657.47  211.69 1767.34  212.18
 1905.95  211.82 1924.76  212.05 1990.22  214.71 2029.31  214.48 2137.07  216.39
#Mann= 3 , 0 , 0
       0     .12       0 1262.58    .055       0 1283.61     .12       0
Bank Sta=1262.58,1283.61
Exp/Cntr=.3,.1

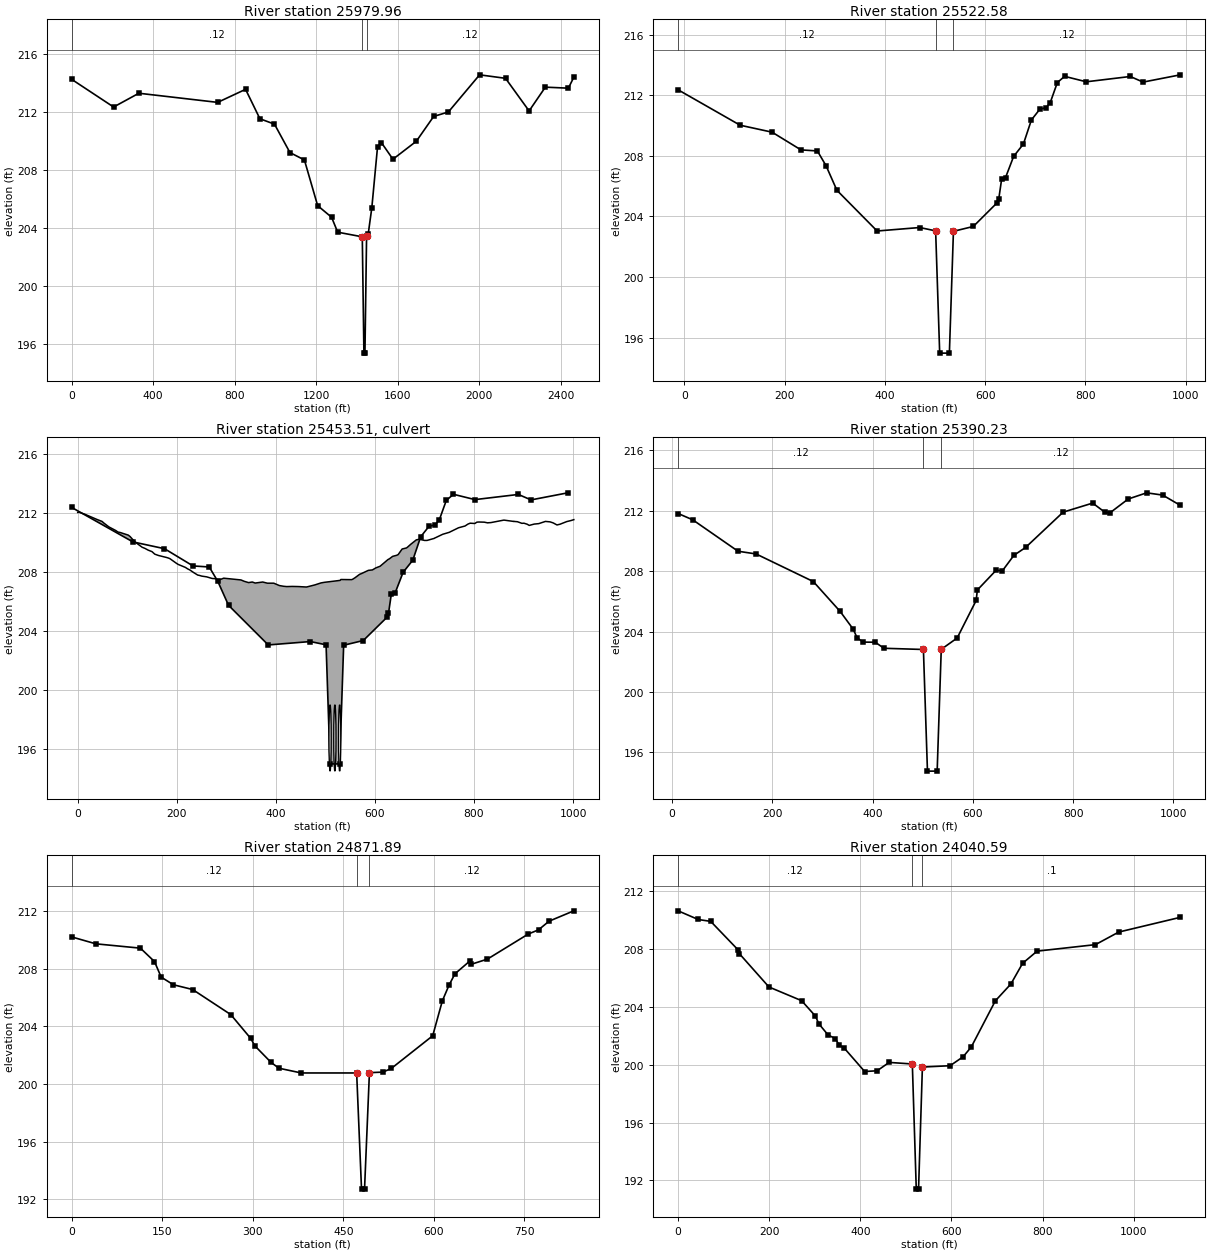
Type RM Length L Ch R = 1 ,25979.96,421.89,457.38,450.85
XS GIS Cut Line= 2
     1861491.669      365196.299     1859038.341      364969.015
#Sta/Elev= 30
       0  214.26  205.87  212.35  329.83   213.3  716.32  212.67  853.32  213.57
  923.56  211.54  995.06  211.17 1070.97  209.21 1141.94   208.7  1206.9  205.55
  1275.2  204.75 1305.21  203.72 1425.89   203.4 1433.91  195.38 1438.91  195.38
 1446.99  203.46 1455.22  203.62 1472.64   205.4 1500.83  209.62 1519.48   209.9
 1576.33  208.75 1691.05  209.99 1776.05   211.7 1848.45  212.01 2001.49  214.57
 2128.67  214.33 2244.32  212.08 2324.03  213.72 2437.09  213.65 2463.83  214.41
#Mann= 3 , 0 , 0
       0     .12       0 1425.89    .055       0 1446.99     .12       0
Bank Sta=1425.89,1446.99
Exp/Cntr=.5,.3

Type RM Length L Ch R = 1 ,25522.58,127.34,132.35,122.06
XS GIS Cut Line= 6
     1860724.488      364787.753     1860482.773      364726.987
     1860305.876      364677.023     1860227.555       364663.52
     1860104.672      364660.819     1859738.724      364656.768
#Sta/Elev= 30
  -12.19  212.37  111.49  210.03   175.2  209.57  232.79   208.4   265.5  208.33
  282.86  207.35  304.45  205.73  384.63  203.04  469.56  203.27  501.32  203.05
   509.4  194.97  528.74  194.97  536.82  203.02  576.47  203.34  624.03  204.91
  627.31  205.18  632.99  206.48  640.72  206.57  656.87  207.97  676.37  208.79
  692.31  210.38   708.9  211.08  721.92   211.2  729.92  211.53  744.03  212.85
  758.49  213.26  801.79   212.9  889.42  213.25  915.06  212.88  989.22  213.36
#Mann= 3 , 0 , 0
  -12.19     .12       0  501.32    .055       0  536.82     .12       0
Bank Sta=501.32,536.82
Exp/Cntr=.5,.3

Type RM Length L Ch R = 2 ,25453.51,,,
BEGIN DESCRIPTION:
SR 1674 (assumed same as SR 1614)
END DESCRIPTION:
Bridge Culvert--1,0,-1,-1, 0
Deck Dist Width WeirC Skew NumUp NumDn MinLoCord MaxHiCord MaxSubmerge Is_Ogee
58.57,21,2.6,0,129,129,206.97,,.95,0,0,0,,
       0     3.5    4.92   14.21   27.43   31.11   38.46   49.12   52.84   62.86
   76.98    81.2    85.6   98.57  102.14  105.86  114.96  115.12  115.19     130
  135.73  142.44  149.98  155.58  163.06  179.78  183.49  186.28  199.64  203.05
   217.4  221.99  226.29  233.63  242.27  245.43  249.24  250.38   260.3  271.38
  278.99  282.47  287.85  294.61  329.55  335.96  344.83  352.39  358.25  373.42
  382.87  387.09  395.73   407.1  415.71  421.84  433.05  443.82  446.16  461.55
  464.25  475.69  478.34   491.3  498.14  529.75  531.11  552.94   555.1  559.77
  568.94  572.68  584.19  586.61  594.76  601.94  610.39  613.57  626.13  629.43
  635.44  635.67  643.64   646.8  654.87  663.52  665.57  671.88  683.54  689.65
  700.11  705.09  719.79  720.49  722.53  736.89  749.99  752.92  768.76  781.84
  787.74  792.17  801.59  805.75   809.6  820.47  827.94  828.82   833.9  860.27
  879.72  880.05  880.16  880.35  887.56  896.53  900.68  907.24   911.4  921.41
  930.51  944.05  953.33  959.69  967.36  973.45  987.18  995.69 1001.41
  212.03  212.04  212.02  211.91  211.72  211.67  211.56  211.42  211.31  211.05
   210.8   210.7  210.67  210.53  210.49  210.39  210.04  210.04  210.04  209.67
  209.59  209.47  209.37   209.2  209.11  208.97  208.93  208.89  208.57   208.5
   208.3   208.2  208.13  207.96  207.78  207.76  207.72  207.71  207.66  207.55
  207.53  207.48  207.48  207.57  207.45  207.36  207.27  207.31  207.24  207.31
  207.23  207.23  207.23  207.07  207.02     207  207.01     207     207  206.97
  206.99  207.09  207.11  207.25  207.29  207.42  207.48  207.47   207.5   207.6
  207.83  207.88  208.06   208.1  208.13  208.27  208.38  208.47  208.83  208.89
  209.05  209.05  209.12  209.17  209.55  209.62  209.67  209.86  210.17  210.21
  210.13  210.13  210.27  210.29  210.32  210.55  210.68  210.73  210.99  211.11
  211.24   211.3  211.28  211.37  211.38  211.37  211.32  211.33  211.34  211.51
  211.42  211.43  211.43  211.42   211.4  211.29   211.3  211.23  211.15  211.24
  211.27  211.42  211.39  211.32  211.18  211.23  211.41  211.48  211.54
                                                                                
                                                                                
                                                                                
                                                                                
                                                                                
                                                                                
                                                                                
                                                                                
                                                                                
                                                                                
                                                                                
                                                                                
                                                                        
       0     3.5    4.92   14.21   27.43   31.11   38.46   49.12   52.84   62.86
   76.98    81.2    85.6   98.57  102.14  105.86  114.96  115.12  115.19     130
  135.73  142.44  149.98  155.58  163.06  179.78  183.49  186.28  199.64  203.05
   217.4  221.99  226.29  233.63  242.27  245.43  249.24  250.38   260.3  271.38
  278.99  282.47  287.85  294.61  329.55  335.96  344.83  352.39  358.25  373.42
  382.87  387.09  395.73   407.1  415.71  421.84  433.05  443.82  446.16  461.55
  464.25  475.69  478.34   491.3  498.14  529.75  531.11  552.94   555.1  559.77
  568.94  572.68  584.19  586.61  594.76  601.94  610.39  613.57  626.13  629.43
  635.44  635.67  643.64   646.8  654.87  663.52  665.57  671.88  683.54  689.65
  700.11  705.09  719.79  720.49  722.53  736.89  749.99  752.92  768.76  781.84
  787.74  792.17  801.59  805.75   809.6  820.47  827.94  828.82   833.9  860.27
  879.72  880.05  880.16  880.35  887.56  896.53  900.68  907.24   911.4  921.41
  930.51  944.05  953.33  959.69  967.36  973.45  987.18  995.69 1001.41
  212.03  212.04  212.02  211.91  211.72  211.67  211.56  211.42  211.31  211.05
   210.8   210.7  210.67  210.53  210.49  210.39  210.04  210.04  210.04  209.67
  209.59  209.47  209.37   209.2  209.11  208.97  208.93  208.89  208.57   208.5
   208.3   208.2  208.13  207.96  207.78  207.76  207.72  207.71  207.66  207.55
  207.53  207.48  207.48  207.57  207.45  207.36  207.27  207.31  207.24  207.31
  207.23  207.23  207.23  207.07  207.02     207  207.01     207     207  206.97
  206.99  207.09  207.11  207.25  207.29  207.42  207.48  207.47   207.5   207.6
  207.83  207.88  208.06   208.1  208.13  208.27  208.38  208.47  208.83  208.89
  209.05  209.05  209.12  209.17  209.55  209.62  209.67  209.86  210.17  210.21
  210.13  210.13  210.27  210.29  210.32  210.55  210.68  210.73  210.99  211.11
  211.24   211.3  211.28  211.37  211.38  211.37  211.32  211.33  211.34  211.51
  211.42  211.43  211.43  211.42   211.4  211.29   211.3  211.23  211.15  211.24
  211.27  211.42  211.39  211.32  211.18  211.23  211.41  211.48  211.54
                                                                                
                                                                                
                                                                                
                                                                                
                                                                                
                                                                                
                                                                                
                                                                                
                                                                                
                                                                                
                                                                                
                                                                                
                                                                        
Multiple Barrel Culv=1,4.5,,21,.027,.7,1,2,2,194.48,194.46, 3,Culvert #1  , 0 ,58.57
   509.4   509.4  519.07  519.07  528.74  528.74
BC Design=,, 0 ,, 0 ,,,,,,

Type RM Length L Ch R = 1 ,25390.23,484.75,518.34,560.82
XS GIS Cut Line= 6
     1860759.597      364670.272     1860517.882      364609.505
     1860340.985      364559.542     1860262.664      364546.038
     1860139.781      364543.338     1859773.833      364539.286
#Sta/Elev= 30
   12.19  211.82   41.44   211.4  131.65  209.32  167.67  209.14   281.8  207.31
  335.33  205.33  361.46  204.15  369.12  203.58  381.18   203.3  405.35  203.29
  422.58  202.89  501.33  202.81   509.4  194.75  528.74  194.75   536.9  202.82
  568.61  203.57  606.55  206.06  608.86  206.75  646.04  208.05  658.98  208.03
  681.81  209.05  705.07  209.57  779.96  211.91  838.87  212.51  863.35   211.9
  873.58  211.87  909.69  212.78   946.5  213.19  978.49  213.04  1013.6  212.36
#Mann= 3 , 0 , 0
   12.19     .12       0  501.33    .055       0   536.9     .12       0
Bank Sta=501.33,536.9
Exp/Cntr=.5,.3

Type RM Length L Ch R = 1 ,24871.89,836.59,831.3,824.71
XS GIS Cut Line= 2
     1860953.541        364337.3     1860224.896      363936.211
#Sta/Elev= 30
       0  210.21   40.11  209.73  113.87  209.43  137.18   208.5  148.28  207.42
  168.53  206.89  200.39  206.56  263.57  204.82  296.52  203.17  303.48  202.65
  330.35   201.5  343.28   201.1  380.28  200.77  472.03  200.77  480.09  192.71
  485.09  192.71  493.17  200.79  515.42  200.83  529.35  201.08  597.99  203.35
  613.93  205.77  624.88  206.85  634.83  207.65  659.28  208.53  661.76  208.31
  688.62  208.67  756.25  210.41  773.24   210.7  790.67   211.3  831.74  212.02
#Mann= 3 , 0 , 0
       0     .12       0  472.03    .055       0  493.17     .12       0
Bank Sta=472.03,493.17
Exp/Cntr=.3,.1

Type RM Length L Ch R = 1 ,24040.59,480.14,542.78,613.02
XS GIS Cut Line= 2
     1861291.619      363600.215     1860327.187      363066.147
#Sta/Elev= 30
       0  210.66   44.06  210.06   71.54  209.93  130.95  207.98   134.6  207.69
  199.39  205.39  271.19  204.44  301.58  203.37  308.71  202.85  329.17  202.07
  344.95  201.82  353.98  201.35  363.54   201.2   409.5  199.54  436.84  199.59
  463.27  200.17  514.15  200.06  522.81   191.4  527.81   191.4  536.26  199.85
  597.01  199.94  625.67  200.56  643.62  201.24  696.38  204.43  730.61   205.6
  756.29  207.03  788.06  207.87  916.16  208.32  967.22  209.19 1102.43  210.21
#Mann= 3 , 0 , 0
       0     .12       0  514.15    .055       0  536.26      .1       0
Bank Sta=514.15,536.26
Exp/Cntr=.5,.3