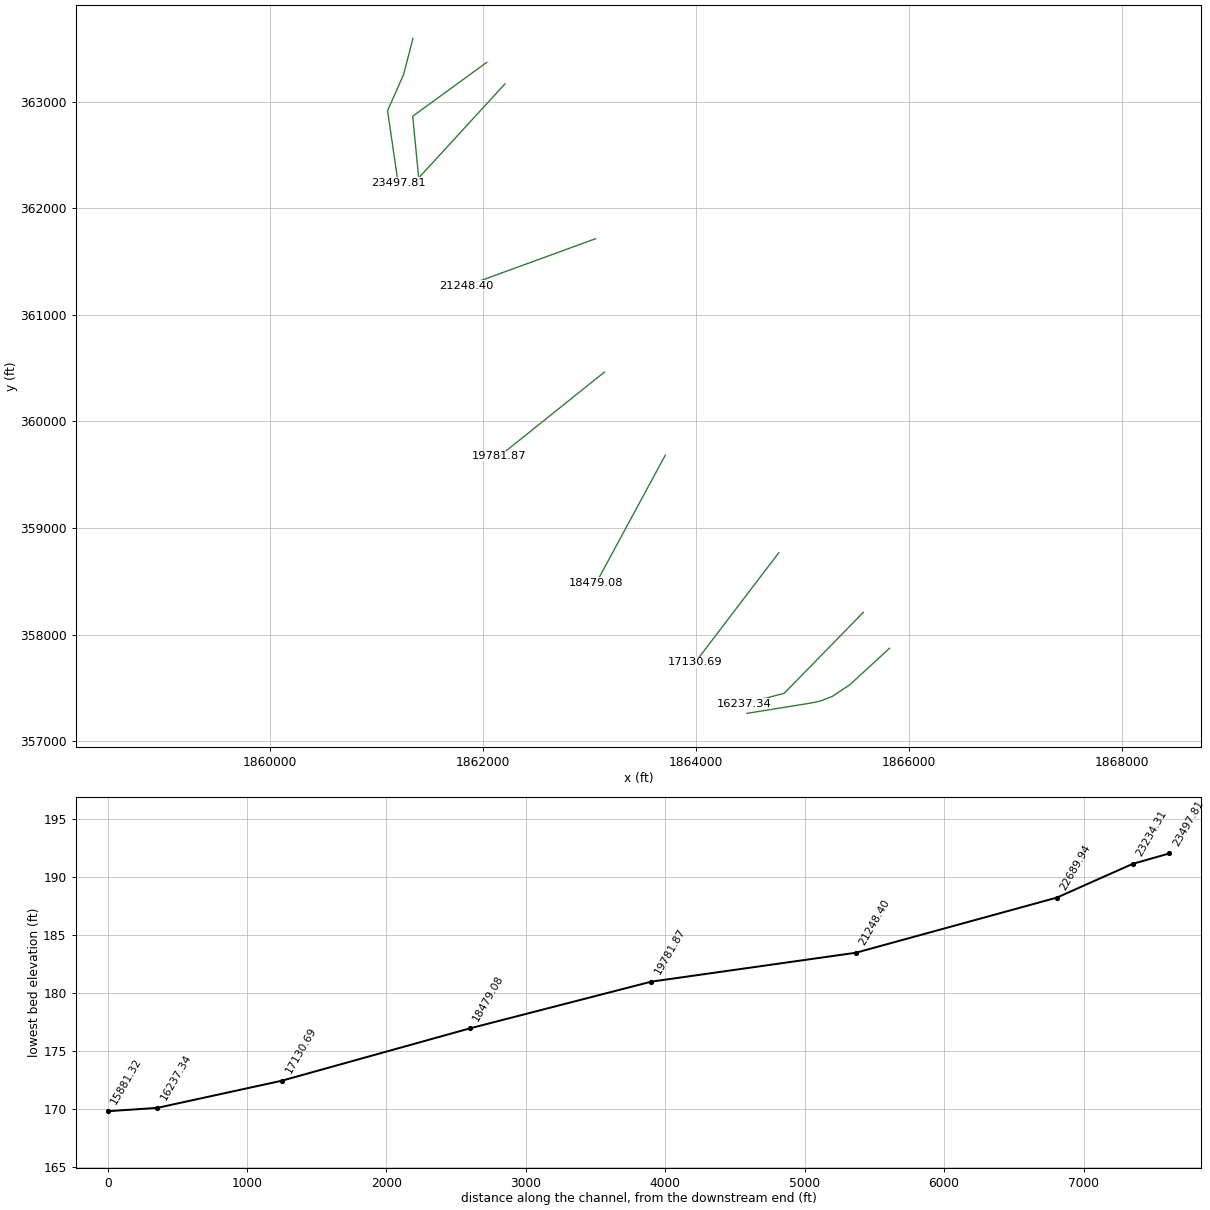
HEC-RAS study bridge.prj: Bridge Creek to Leith Creek

--- bridge.g02 (geometry) --- (continued)

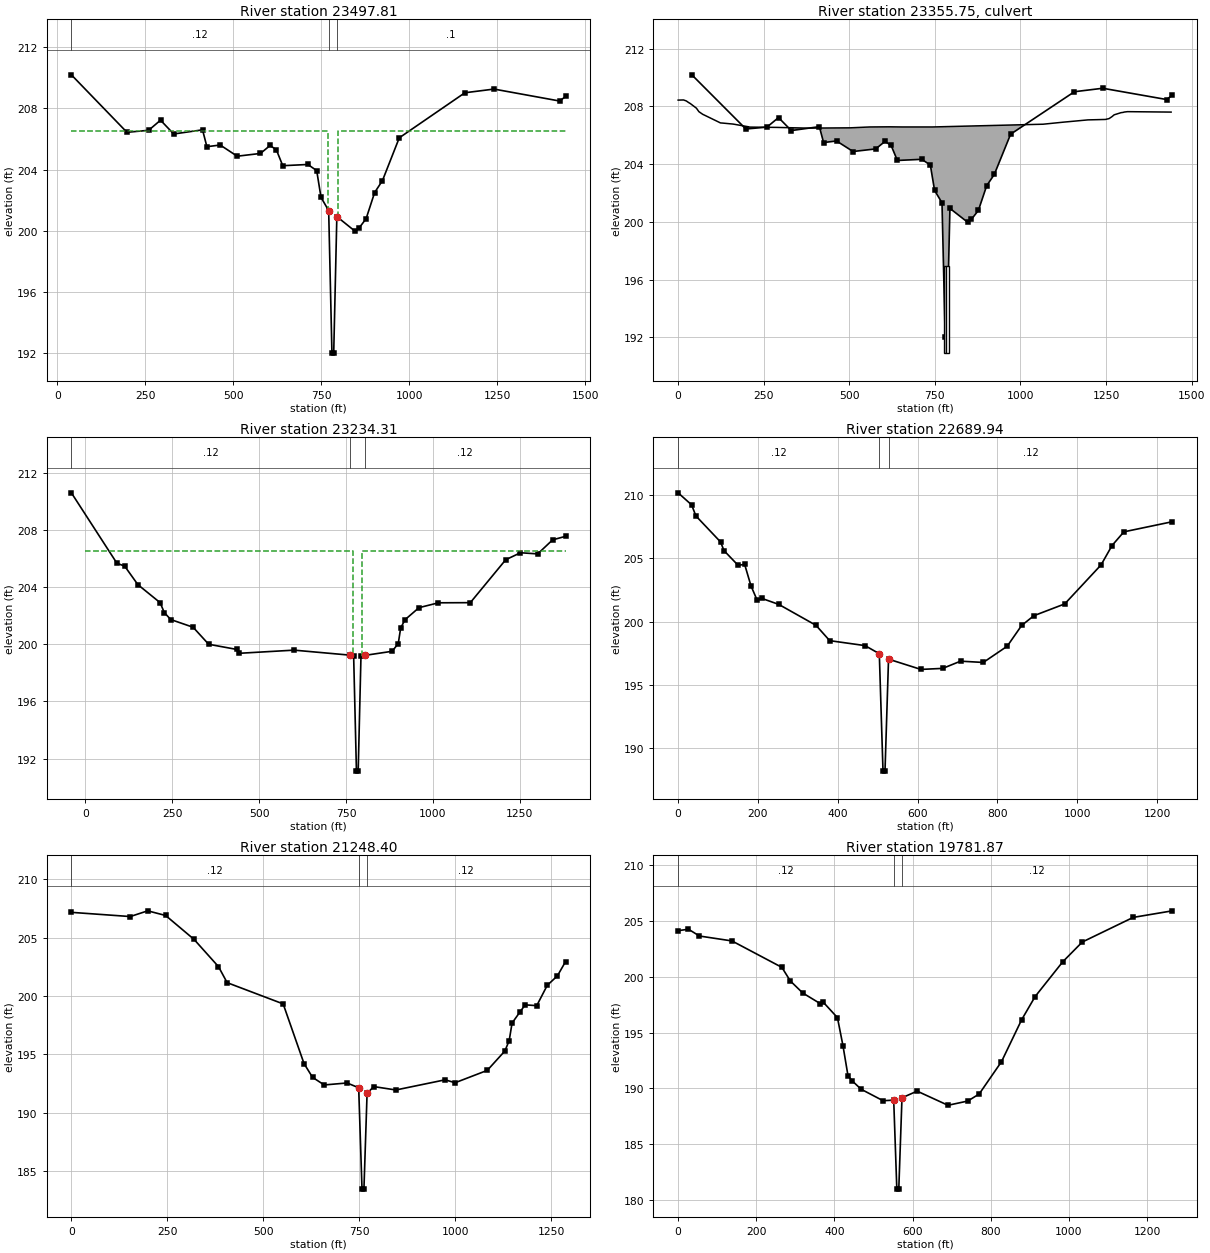
Type RM Length L Ch R = 1 ,23497.81,298.74,263.5,235.62
XS GIS Cut Line= 4
     1861346.063       363595.03     1861257.916      363255.404
     1861107.548      362915.779     1861206.065      362241.713
#Sta/Elev= 30
   40.08  210.18  197.87  206.43  259.47  206.56  293.26  207.22  330.62  206.32
  412.56  206.59   424.9  205.49  462.72   205.6  511.01  204.87   577.1  205.05
  604.35  205.57  622.15  205.29  640.37  204.25  711.72  204.33  736.76  203.93
  749.05  202.18  770.75  201.32  780.05  192.02  785.05  192.02  793.96  200.93
  845.38  199.98  856.54  200.17  877.04  200.79  901.28   202.5  923.51  203.28
  971.25  206.07 1157.58  209.01 1240.32  209.25 1426.81  208.47 1443.61  208.77
#Mann= 3 , 0 , 0
   40.08     .12       0  770.75    .055       0  793.96      .1       0
#XS Ineff= 2 , 0
       0  769.22  206.49  795.89       0  206.49
Bank Sta=770.75,793.96
Exp/Cntr=.5,.3

Type RM Length L Ch R = 2 ,23355.75,,,
BEGIN DESCRIPTION:
US 501 (NCDOT 82 2020)
END DESCRIPTION:
Bridge Culvert--1,0,-1,-1, 0
Deck Dist Width WeirC Skew NumUp NumDn MinLoCord MaxHiCord MaxSubmerge Is_Ogee
112.56,59,2.6,0,34,34,206.49,,.95,0,0,0,,
       0   15.79   23.98   30.04   35.66   53.43   60.65   72.19   73.03   73.37
  123.67  129.56   160.7  206.02  208.86  286.97  377.87  502.55  559.47  617.06
  654.76  742.47 1065.95 1124.14 1197.14 1248.04  1258.8 1267.04 1273.57 1293.75
 1300.24 1302.46 1312.55    1440
  208.43  208.44  208.37  208.27  208.19  207.87  207.63  207.44  207.43  207.43
  206.85  206.84  206.77  206.58  206.56  206.54  206.49  206.51  206.57  206.58
  206.57  206.57  206.76   206.9  207.06  207.09  207.15  207.28  207.41  207.56
  207.58   207.6  207.63   207.6
                                                                                
                                                                                
                                                                                
                                
       0   15.79   23.98   30.04   35.66   53.43   60.65   72.19   73.03   73.37
  123.67  129.56   160.7  206.02  208.86  286.97  377.87  502.55  559.47  617.06
  654.76  742.47 1065.95 1124.14 1197.14 1248.04  1258.8 1267.04 1273.57 1293.75
 1300.24 1302.46 1312.55    1440
  208.43  208.44  208.37  208.27  208.19  207.87  207.63  207.44  207.43  207.43
  206.85  206.84  206.77  206.58  206.56  206.54  206.49  206.51  206.57  206.58
  206.57  206.57  206.76   206.9  207.06  207.09  207.15  207.28  207.41  207.56
  207.58   207.6  207.63   207.6
                                                                                
                                                                                
                                                                                
                                
Multiple Barrel Culv=2,6,7,59,.012,.4,1,8,1,190.91,190.89, 2,Culvert #1  , 0 ,112.56
  778.72  778.72  786.39  786.39
BC Design=,, 0 ,, 0 ,,,,,,

Type RM Length L Ch R = 1 ,23234.31,595.29,544.37,380.39
XS GIS Cut Line= 3
     1862038.277      363369.477     1861343.471      362863.927
     1861397.914      362303.934
#Sta/Elev= 30
  -40.08  210.58   90.83  205.66   113.4  205.45  151.23  204.16  215.23   202.9
  227.17  202.21  245.73  201.72  310.18  201.18  354.93  199.99   435.6  199.63
  443.11  199.36  600.69  199.58  761.58  199.23  772.02  199.16  780.06  191.12
  785.06  191.12   793.1  199.16  803.53  199.21  882.73   199.5  900.35  200.04
  907.32  201.13  919.88  201.71     960  202.55 1015.99  202.89 1107.68   202.9
 1209.45   205.9 1251.99  206.39  1301.6  206.31 1344.35  207.29 1381.82  207.54
#Mann= 3 , 0 , 0
  -40.08     .12       0  761.58    .055       0  803.53     .12       0
#XS Ineff= 2 , 0
       0  769.22  206.49  795.89       0  206.49
Bank Sta=761.58,803.53
Exp/Cntr=.5,.3

Type RM Length L Ch R = 1 ,22689.94,1548.64,1441.54,1330.26
XS GIS Cut Line= 2
     1862209.386      363167.257     1861371.989      362254.676
#Sta/Elev= 30
       0  210.18   33.81  209.23   44.46  208.36  106.41   206.3  114.91  205.62
  150.25  204.46  166.72  204.53  182.65  202.83  198.13   201.7  209.36  201.85
  252.38  201.37  345.55  199.72  379.85  198.51  468.31  198.12  504.18  197.48
  513.45  188.21  518.45  188.21  527.29  197.05  608.36  196.24  663.02  196.32
  707.76  196.89  764.78  196.79  824.68  198.07   860.9  199.71  891.54  200.48
  968.83  201.41 1059.93  204.49 1087.41  206.02 1117.11   207.1 1238.56   207.9
#Mann= 3 , 0 , 0
       0     .12       0  504.18    .055       0  527.29     .12       0
Bank Sta=504.18,527.29
Exp/Cntr=.3,.1

Type RM Length L Ch R = 1 ,21248.40,1392.67,1466.53,1421.83
XS GIS Cut Line= 2
     1863060.296      361714.709     1861850.962      361273.466
#Sta/Elev= 30
       0  207.16  153.31   206.8  198.86  207.29  245.56  206.89  319.64  204.84
  383.19  202.51  405.69  201.14  551.64  199.32  605.97  194.21  628.26  193.03
  658.62  192.38  718.12  192.55  748.33  192.14  757.01  183.46  762.01  183.46
  770.21  191.66  787.61  192.24  845.31  191.95  973.48  192.82  999.49  192.57
 1083.34  193.63 1129.15  195.29 1140.36  196.18 1147.88  197.68 1167.58  198.59
 1182.01  199.24 1212.12  199.17 1239.48  200.91 1265.92  201.72 1287.32  202.95
#Mann= 3 , 0 , 0
       0     .12       0  748.33    .055       0  770.21     .12       0
Bank Sta=748.33,770.21
Exp/Cntr=.3,.1

Type RM Length L Ch R = 1 ,19781.87,1203.37,1302.79,1330.3
XS GIS Cut Line= 2
     1863142.205      360462.301     1862155.335      359671.405
#Sta/Elev= 30
       0  204.15   26.49  204.28   54.58  203.67  137.77  203.23  265.51  200.86
  287.12  199.64  318.96  198.56  364.05   197.6  371.82  197.72  407.69  196.35
  421.76  193.85  434.69  191.14  446.01  190.66  468.26  189.93  524.42   188.9
  551.68  188.95  559.66  180.97  564.66  180.97  572.85  189.16  611.59  189.76
  690.56  188.49  741.09  188.87  770.35   189.5  827.46   192.4  879.01  196.16
  913.51  198.24  984.26  201.36 1034.12  203.13 1164.47  205.34 1264.69  205.93
#Mann= 3 , 0 , 0
       0     .12       0  551.68    .055       0  572.85     .12       0
Bank Sta=551.68,572.85
Exp/Cntr=.3,.1

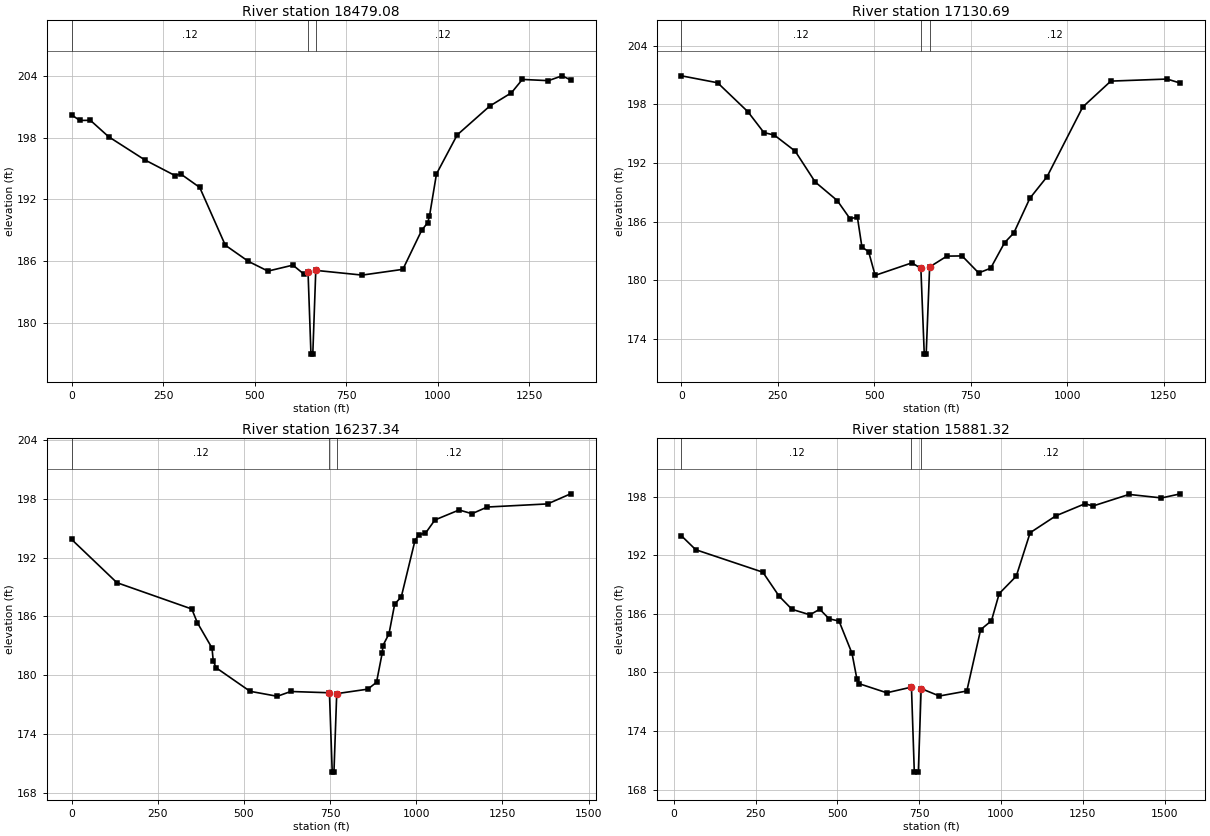
Type RM Length L Ch R = 1 ,18479.08,1334.86,1348.39,1299.99
XS GIS Cut Line= 2
      1863713.99       359682.81     1863065.744      358484.371
#Sta/Elev= 30
       0  200.22   22.26  199.68   51.28  199.69  100.84   198.1  199.38  195.85
  282.04  194.32  298.36  194.46  349.81  193.16  419.62  187.54  482.97  185.96
   536.1  185.02   604.3   185.6  634.12  184.73  645.59   184.9  653.55  176.94
  658.55  176.94   666.7  185.09  793.31  184.63  904.49  185.19  955.77  188.98
  972.21  189.73  977.07  190.35  996.23  194.47 1052.81  198.27 1141.49  201.07
 1200.95  202.37 1230.79  203.67 1301.75  203.55 1339.44  204.02 1362.53  203.62
#Mann= 3 , 0 , 0
       0     .12       0  645.59    .055       0   666.7     .12       0
Bank Sta=645.59,666.7
Exp/Cntr=.3,.1

Type RM Length L Ch R = 1 ,17130.69,917.35,893.34,872.66
XS GIS Cut Line= 2
     1864779.989      358768.524     1863996.092       357739.66
#Sta/Elev= 30
       0  200.91   93.65   200.2   172.3  197.23  213.71   195.1  240.56  194.85
  294.83   193.2  346.52  190.05  403.71  188.15  436.69   186.3   456.1  186.43
  467.81  183.38   485.1  182.92  502.05  180.49  597.29  181.77  620.57  181.21
  629.35  172.43  634.35  172.43  643.27  181.35  688.04  182.46  727.39  182.48
  770.36  180.74  801.45  181.22  837.43  183.83  861.49  184.83  903.09  188.38
  947.72  190.59 1040.17  197.72 1112.95  200.37 1258.86  200.58 1293.47  200.16
#Mann= 3 , 0 , 0
       0     .12       0  620.57    .055       0  643.27     .12       0
Bank Sta=620.57,643.27
Exp/Cntr=.3,.1

Type RM Length L Ch R = 1 ,16237.34,411.58,356.02,309.77
XS GIS Cut Line= 3
     1865572.137      358207.712     1864830.553       357448.61
     1864456.841      357349.342
#Sta/Elev= 30
       0  193.87  131.43  189.45  348.66  186.76  364.87  185.36  407.36  182.77
  410.92  181.47  419.13  180.76   517.7  178.35  596.78  177.84  635.78  178.33
  748.08   178.2  756.19  170.09  761.19  170.09  769.21  178.11  859.49  178.57
  884.68  179.27  901.34  182.29   903.4  183.03  920.92  184.23  937.46  187.27
  956.61     188  996.19  193.74 1007.25  194.37 1026.48  194.49 1054.11  195.86
 1124.33  196.88 1161.73   196.5 1206.01  197.18 1381.16   197.5 1447.89  198.53
#Mann= 3 , 0 , 0
       0     .12       0  748.08    .055       0  769.21     .12       0
Bank Sta=748.08,769.21
Exp/Cntr=.5,.3

Type RM Length L Ch R = 1 ,15881.32,119.65,120.2,111.6
XS GIS Cut Line= 6
     1865818.726      357871.093     1865445.971      357528.349
     1865278.548      357417.786     1865172.723       357376.72
     1865076.376      357356.187     1864479.337      357259.839
#Sta/Elev= 30
   23.74  193.98   67.39  192.56  272.42  190.26  322.03  187.81  361.49  186.46
  416.33   185.9  446.29  186.47   474.9  185.49  505.27  185.26  544.96  181.95
  559.61  179.38  566.65  178.85   651.1  177.92   726.6   178.5   735.3   169.8
  747.64   169.8  756.19  178.35  811.82  177.59  895.73   178.1  938.03  184.38
  971.04  185.29  994.74  188.07 1046.96  189.86 1089.27   194.3 1167.95  196.03
 1257.17  197.27 1280.96  197.03 1391.43  198.22 1490.65  197.86 1548.68  198.28
#Mann= 3 , 0 , 0
   23.74     .12       0   726.6    .055       0  756.19     .12       0
Bank Sta=726.6,756.19
Exp/Cntr=.5,.3