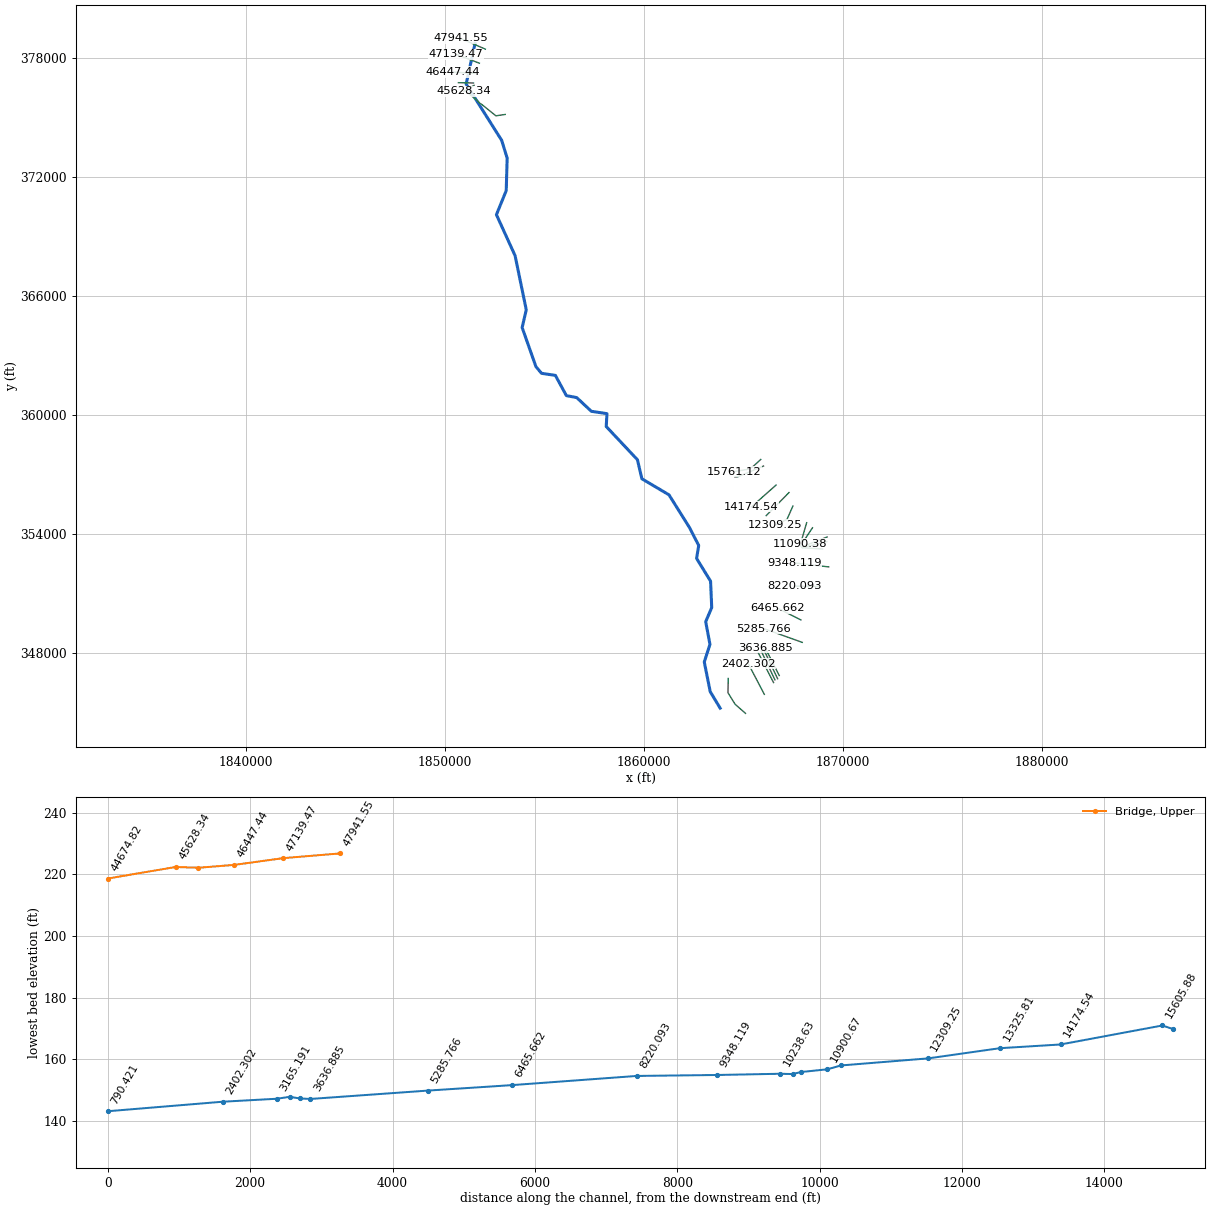
HEC-RAS study bridge.prj: Bridge Creek to Leith Creek

--- bridge.g02 (geometry) --- (continued)

Type RM Length L Ch R = 2 ,15824.28,,,
BEGIN DESCRIPTION:
SR 1614 (NCDOT 82 2066)
END DESCRIPTION:
Bridge Culvert--1,0,-1,-1, 0
Deck Dist Width WeirC Skew NumUp NumDn MinLoCord MaxHiCord MaxSubmerge Is_Ogee
46.54,21,2.6,0, 60, 60,182.1,,.95,0,0,0,,
       0    31.9   99.32  142.23  162.13  178.62  200.26  216.58  260.61  279.59
  300.01   322.7  356.96  373.84  415.01  428.71  429.18  485.05  506.87  516.96
  628.41  655.96  674.02  683.39  717.55   742.3  754.84  761.33  770.57  786.13
  823.27  920.59  960.62  972.04 1008.91 1022.28    1040 1137.74 1155.38 1202.32
 1226.45 1271.52 1312.82 1318.93  1347.1 1358.22 1366.35 1368.84 1372.73 1387.95
  1410.6 1430.95 1437.22 1446.53 1454.52 1456.48 1468.85 1496.81 1514.11 1524.94
  194.26  193.57  192.99  191.65  191.41  191.43  190.98  190.44  189.98  189.93
  189.39  188.52  188.17  187.78  186.37  186.36  186.23  185.78  185.39  184.98
  183.24  183.26   182.6  182.45   182.4   182.1  182.36  182.17  182.27  182.15
  182.83  183.71  184.57     185  185.58  186.17  186.28  188.13  188.76  189.94
  190.88  191.24  192.23  192.52  192.92  192.81  193.11  193.43  193.34  193.92
  194.13  194.51  194.86  194.88  195.32  195.72  195.54  195.85  196.68  196.71
                                                                                
                                                                                
                                                                                
                                                                                
                                                                                
                                                                                
       0    31.9   99.32  142.23  162.13  178.62  200.26  216.58  260.61  279.59
  300.01   322.7  356.96  373.84  415.01  428.71  429.18  485.05  506.87  516.96
  628.41  655.96  674.02  683.39  717.55   742.3  754.84  761.33  770.57  786.13
  823.27  920.59  960.62  972.04 1008.91 1022.28    1040 1137.74 1155.38 1202.32
 1226.45 1271.52 1312.82 1318.93  1347.1 1358.22 1366.35 1368.84 1372.73 1387.95
  1410.6 1430.95 1437.22 1446.53 1454.52 1456.48 1468.85 1496.81 1514.11 1524.94
  194.26  193.57  192.99  191.65  191.41  191.43  190.98  190.44  189.98  189.93
  189.39  188.52  188.17  187.78  186.37  186.36  186.23  185.78  185.39  184.98
  183.24  183.26   182.6  182.45   182.4   182.1  182.36  182.17  182.27  182.15
  182.83  183.71  184.57     185  185.58  186.17  186.28  188.13  188.76  189.94
  190.88  191.24  192.23  192.52  192.92  192.81  193.11  193.43  193.34  193.92
  194.13  194.51  194.86  194.88  195.32  195.72  195.54  195.85  196.68  196.71
                                                                                
                                                                                
                                                                                
                                                                                
                                                                                
                                                                                
Multiple Barrel Culv=1,4.5,,21,.027,.7,1,2,2,169.21,169.19, 3,Culvert #1  , 0 ,46.54
   735.3   735.3  740.47  740.47  747.64  747.64
BC Design=,, 0 ,, 0 ,,,,,,

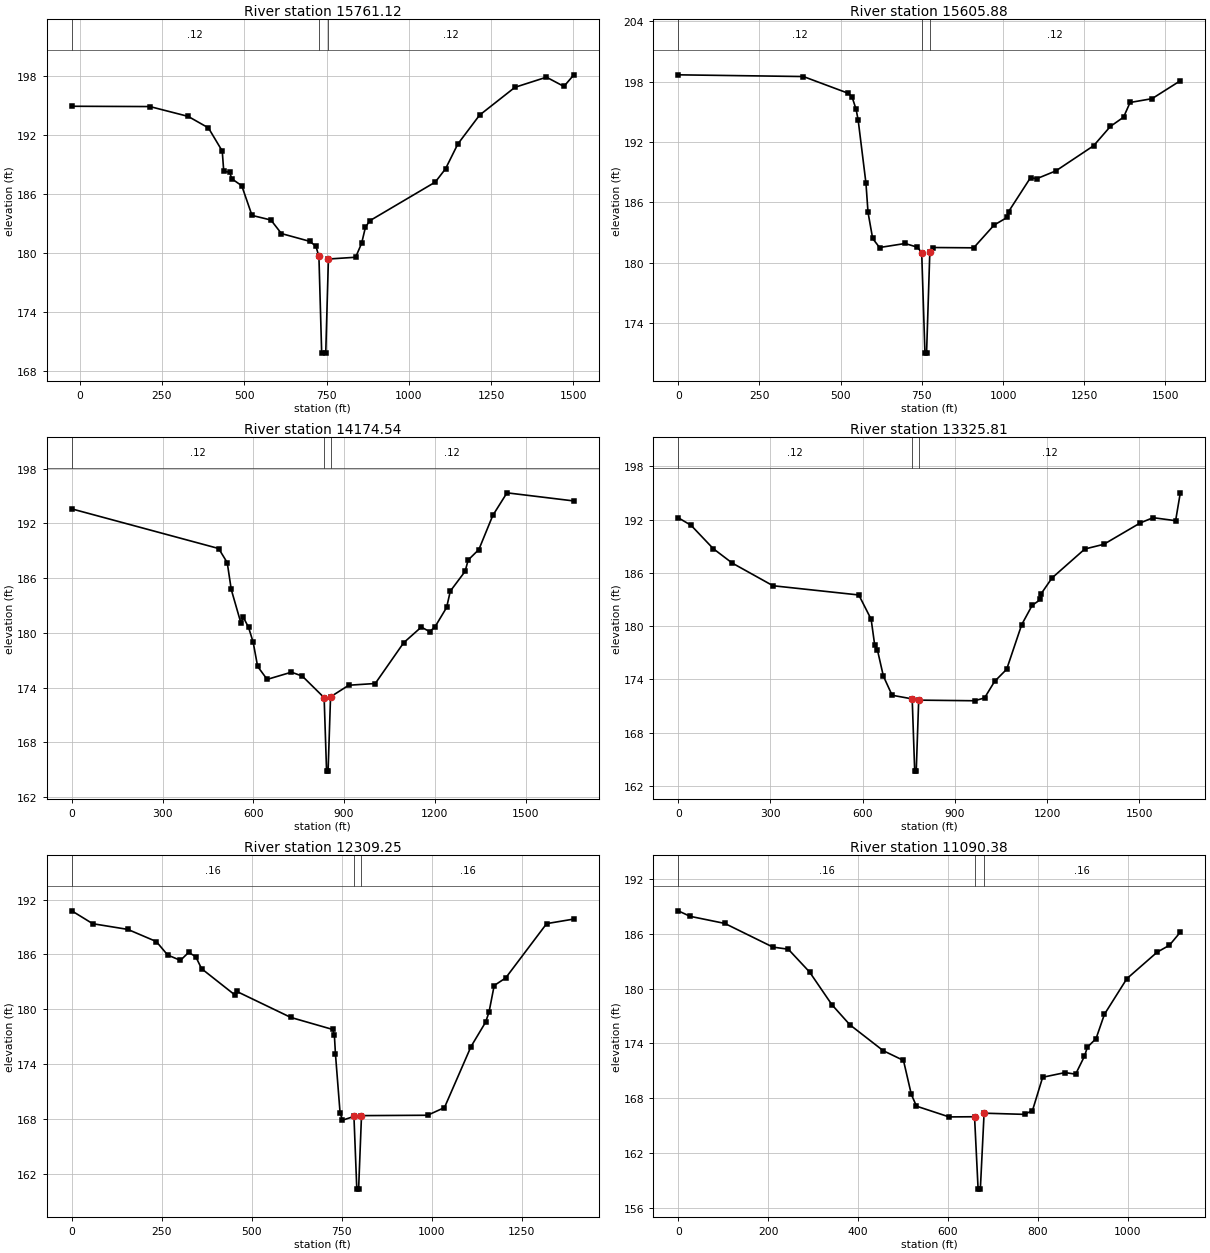
Type RM Length L Ch R = 1 ,15761.12,160.83,155.24,165.96
XS GIS Cut Line= 6
     1865870.848      357768.428     1865498.094      357425.683
      1865330.67      357315.121     1865224.846      357274.054
     1865128.498      357253.521     1864531.459      357157.174
#Sta/Elev= 30
  -23.74  194.93  213.47   194.9  329.69   193.9  391.27  192.73  433.28  190.37
  437.89   188.3  455.83  188.22  462.16  187.55  492.54  186.84  523.65  183.82
  581.15  183.35  613.06  181.97  699.05  181.18  717.75  180.68  726.92  179.64
   735.3   169.8  747.64   169.8  755.76  179.38  838.46  179.56  856.66  180.99
   868.1   182.6  881.07  183.27 1080.24  187.21 1111.42  188.56 1148.87  191.09
 1214.95  194.03 1322.33  196.86 1418.09  197.89 1471.07  196.95  1501.2  198.13
#Mann= 3 , 0 , 0
  -23.74     .12       0  726.92    .055       0  755.76     .12       0
Bank Sta=726.92,755.76
Exp/Cntr=.5,.3

Type RM Length L Ch R = 1 ,15605.88,1412.28,1431.34,1525.89
XS GIS Cut Line= 3
     1866010.081      357436.931     1864713.768      356893.881
     1864573.626      356888.042
#Sta/Elev= 30
       0  198.68  385.27  198.51  523.78  196.84  534.93   196.5  547.66  195.24
  554.03  194.16  577.91  187.91  584.28  185.01  598.57  182.41  619.77  181.51
  698.34  181.91   736.4  181.54  749.53     181  759.52  171.01  764.52  171.01
  774.53  181.02  784.01  181.51  909.51  181.48  972.34  183.74 1012.96  184.51
 1017.05  185.08 1084.64  188.46 1103.51  188.35 1162.64  189.13 1278.84  191.63
 1330.47  193.55 1371.05  194.47 1391.04  195.93 1458.75  196.31 1545.73  198.09
#Mann= 3 , 0 , 0
       0     .12       0  749.53    .055       0  774.53     .12       0
Bank Sta=749.53,774.53
Exp/Cntr=.3,.1

Type RM Length L Ch R = 1 ,14174.54,792.17,848.72,858.24
XS GIS Cut Line= 2
     1866641.995      356479.709     1865399.976      355379.324
#Sta/Elev= 30
       0  193.58  485.37  189.24  513.81  187.69  527.09  184.75  558.94  181.08
  567.07   181.7  584.21   180.6  599.45  178.98  614.26  176.32  645.71   174.9
  725.97  175.69  761.84  175.26  834.06   172.9  842.11  164.85  847.11  164.85
  855.25  172.99  915.37  174.26 1003.04  174.45 1097.05  178.92 1155.16  180.63
 1183.05  180.13 1200.91  180.68 1238.86  182.78 1251.01  184.57 1300.06  186.74
 1310.06  187.98 1345.47  189.13 1391.43  192.86 1438.38  195.34 1659.35  194.45
#Mann= 3 , 0 , 0
       0     .12       0  834.06    .055       0  855.25     .12       0
Bank Sta=834.06,855.25
Exp/Cntr=.3,.1

Type RM Length L Ch R = 1 ,13325.81,963.39,1016.57,873.85
XS GIS Cut Line= 2
     1867292.657      356101.876     1866144.809      354940.029
#Sta/Elev= 30
       0   192.2   41.73  191.35  113.87  188.72  175.86  187.09  308.27  184.54
  587.44   183.5  627.53  180.76  638.84  177.91  647.73  177.34  667.28  174.36
  695.72   172.2  761.05  171.79   769.2  163.65   774.2  163.65   782.2  171.65
  964.13  171.58  996.49   171.9 1029.14  173.76  1068.4  175.13  1117.2  180.15
 1151.07  182.32 1178.34  182.99 1180.94  183.66 1215.97  185.42 1322.58  188.68
 1384.39  189.21 1503.09  191.62 1544.69  192.21 1617.92  191.87 1633.23  195.01
#Mann= 3 , 0 , 0
       0     .12       0  761.05    .055       0   782.2     .12       0
Bank Sta=761.05,782.2
Exp/Cntr=.3,.1

Type RM Length L Ch R = 1 ,12309.25,1110.13,1218.87,1284.36
XS GIS Cut Line= 3
      1867487.41      355422.391     1867189.608      354750.878
     1866594.005      354464.755
#Sta/Elev= 30
       0  190.77    58.3  189.36  155.62  188.74  234.97  187.41   266.4  185.94
  301.93  185.35  324.72  186.22  344.48  185.76  360.78  184.44  453.59  181.56
  458.24  181.96  608.76  179.11  725.45  177.79  729.83  177.17  732.83   175.1
  745.65  168.68  752.38  167.87  784.21  168.28  792.16  160.33  797.16  160.33
   805.2  168.37  988.79  168.41 1035.77  169.25 1109.53  175.92  1150.1  178.59
 1159.57  179.69 1173.99   182.6 1205.96  183.43 1319.76  189.37 1395.35  189.87
#Mann= 3 , 0 , 0
       0     .16       0  784.21    .055       0   805.2     .16       0
Bank Sta=784.21,805.2
Exp/Cntr=.3,.1

Type RM Length L Ch R = 1 ,11090.38,215.4,189.71,146.43
XS GIS Cut Line= 2
     1868178.177      354583.996     1867867.672      353510.848
#Sta/Elev= 30
       0   188.5   26.28   187.9   103.7  187.12  210.73  184.53  244.87   184.3
  292.17  181.81  341.89  178.23  381.93  176.03  456.02   173.2  501.19  172.13
  518.63  168.42     530  167.13  602.84  165.95  659.32  165.97  667.24  158.05
  672.24  158.05  680.55  166.36  770.49  166.23  788.25  166.65  810.87  170.29
  860.64   170.8  884.26  170.63  903.97   172.6  910.43  173.58  929.66  174.52
  948.33  177.18  998.28  181.08  1065.7  183.98 1092.85  184.73 1117.17  186.16
#Mann= 3 , 0 , 0
       0     .16       0  659.32    .055       0  680.55     .16       0
Bank Sta=659.32,680.55
Exp/Cntr=.3,.1

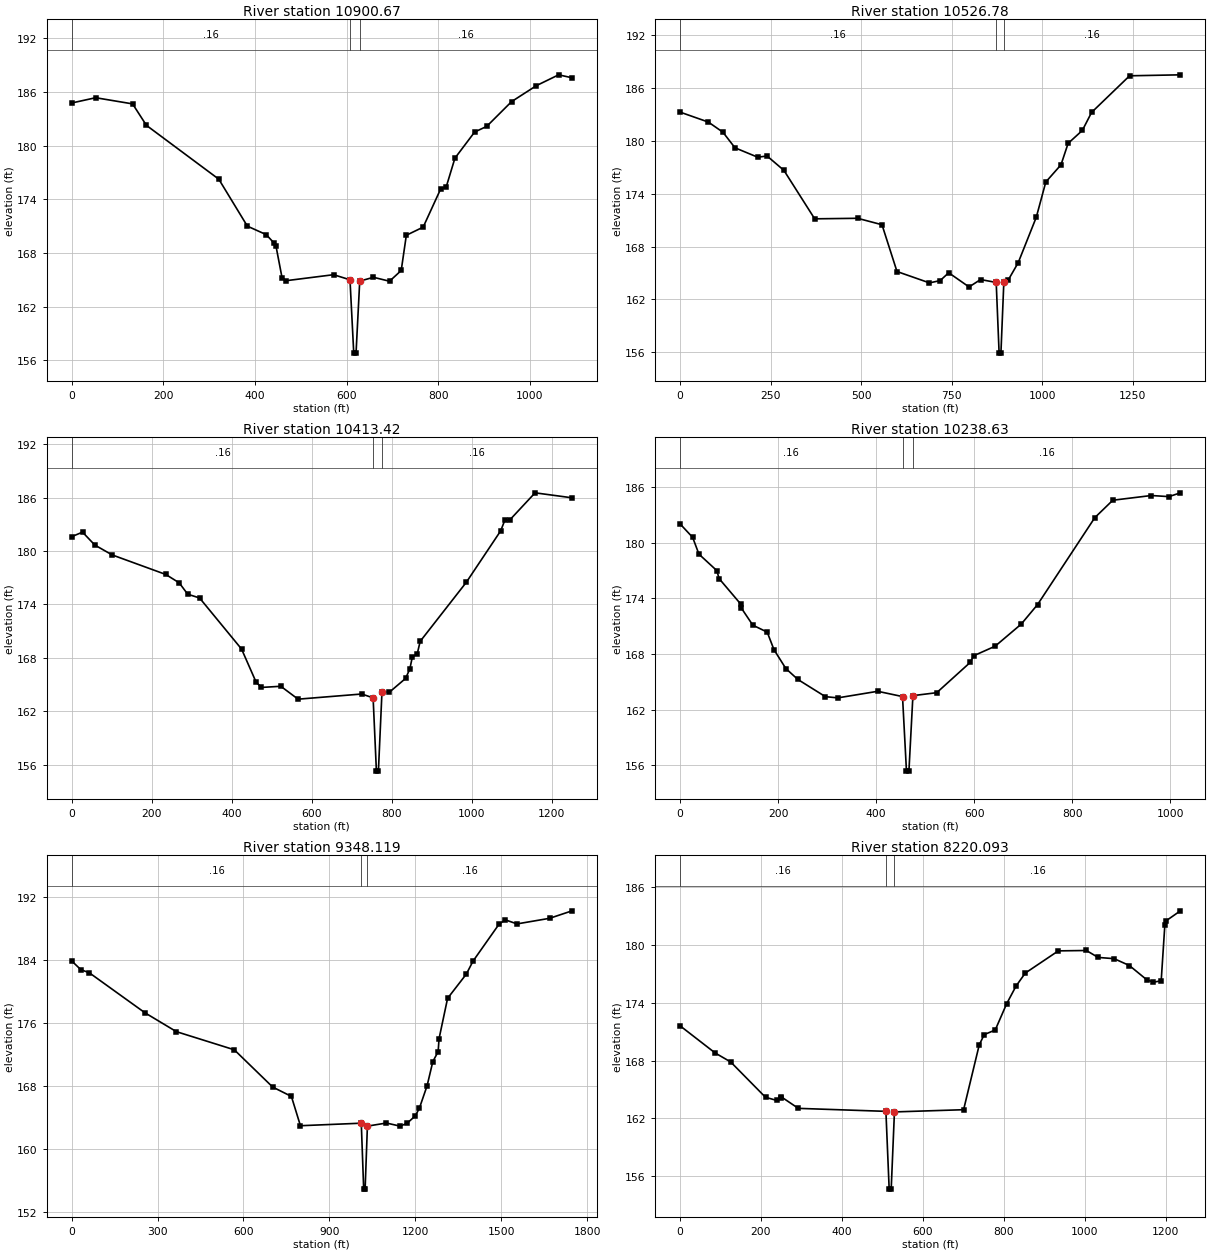
Type RM Length L Ch R = 1 ,10900.67,476.54,373.89,338.6
XS GIS Cut Line= 2
     1868472.339      354327.966     1867867.672      353418.241
#Sta/Elev= 30
       0  184.78   52.37  185.37  132.98  184.68  163.16  182.28  321.15  176.26
  383.52  171.01  424.72  170.06  441.73  169.12  446.01  168.78  459.17  165.26
  468.15  164.91  571.77  165.58  607.57  165.01  615.77  156.81  620.77  156.81
  628.82  164.86  658.78  165.29  693.87  164.85  719.39  166.05  730.56  169.99
  767.33   170.9  805.54  175.17  817.67   175.4  836.64  178.61  879.61  181.53
  906.16  182.17  960.24  184.93 1014.47  186.72 1063.04  187.93 1092.35   187.6
#Mann= 3 , 0 , 0
       0     .16       0  607.57    .055       0  628.82     .16       0
Bank Sta=607.57,628.82
Exp/Cntr=.3,.1

Type RM Length L Ch R = 1 ,10526.78,141.65,113.36,99.09
XS GIS Cut Line= 2
     1869207.745      353864.932     1867922.146      353358.319
#Sta/Elev= 30
       0  183.26   78.16  182.13  118.45  180.98  151.76  179.21  214.62  178.14
  240.35  178.28  286.88  176.65  371.86  171.15  490.35  171.21  557.74  170.48
  599.15  165.17  688.88  163.88  718.36  164.14  741.95  165.03  798.17  163.42
     830  164.26  873.15  163.93  881.17  155.91  886.17  155.91  894.24  163.98
  905.88  164.17  933.88  166.17  983.92  171.34 1010.12  175.33 1052.06  177.28
  1071.7  179.71 1110.98  181.18 1136.66  183.23 1241.53  187.38 1381.82  187.49
#Mann= 3 , 0 , 0
       0     .16       0  873.15    .055       0  894.24     .16       0
Bank Sta=873.15,894.24
Exp/Cntr=.3,.1

Type RM Length L Ch R = 1 ,10413.42,234.7,174.79,137.99
XS GIS Cut Line= 2
     1869191.402      353630.692     1867976.621      353331.082
#Sta/Elev= 30
       0  181.62   27.11  182.13    57.8  180.68  101.17  179.57  235.42  177.37
  268.86  176.43  290.15  175.15  319.76  174.73  424.85  168.98  461.09  165.27
  474.49  164.67  522.91   164.8  566.12  163.35  725.28  163.93  753.73   163.5
  761.97  155.26  766.97  155.26   775.9  164.19  794.08  164.12  834.84  165.68
  845.48  166.74  851.84   168.1  864.01  168.44   871.4  169.85  986.76  176.49
 1072.64  182.27 1083.38   183.5 1094.84  183.47 1158.72  186.55 1251.18  185.99
#Mann= 3 , 0 , 0
       0     .16       0  753.73    .055       0   775.9     .16       0
Bank Sta=753.73,775.9
Exp/Cntr=.3,.1

Type RM Length L Ch R = 1 ,10238.63,877.06,890.51,843.66
XS GIS Cut Line= 2
     1868978.952      353260.265     1867960.278      353320.187
#Sta/Elev= 30
       0  182.06   25.73   180.6   38.54  178.79   75.04  177.01   79.66  176.15
  123.42  173.42  124.39  173.02  148.44  171.12  177.78  170.37  191.55  168.48
  215.74  166.44  240.24  165.26  296.48   163.4  321.82  163.27  403.15  163.98
  453.74  163.41  461.79  155.36  466.79  155.36  474.94  163.51  523.54  163.83
  592.22  167.12  598.57  167.81  642.65  168.85  695.75  171.23   729.1  173.34
   845.9  182.73  882.59  184.61  961.24  185.12  997.04     185 1020.44  185.41
#Mann= 3 , 0 , 0
       0     .16       0  453.74    .055       0  474.94     .16       0
Bank Sta=453.74,474.94
Exp/Cntr=.3,.1

Type RM Length L Ch R = 1 ,9348.119,1106.19,1128.03,1179.63
XS GIS Cut Line= 2
     1869287.394       352357.37     1867551.623      352560.343
#Sta/Elev= 30
       0  183.93      32  182.82   61.31  182.43  256.19  177.34  365.76  174.95
  567.83  172.65  701.95  167.92  767.38  166.73  798.92  163.01 1011.47  163.33
 1019.84  154.96 1024.84  154.96 1032.84  162.96 1099.24  163.35 1146.63  162.96
 1170.93   163.3 1200.37  164.27 1214.72  165.27 1241.29  168.08  1261.4  171.16
 1279.88  172.41 1283.04  174.05 1312.86  179.18 1378.17  182.25 1401.85  183.91
 1492.12  188.57 1513.95  189.15 1555.44  188.63 1669.22  189.34  1747.6  190.29
#Mann= 3 , 0 , 0
       0     .16       0 1011.47    .055       0 1032.84     .16       0
Bank Sta=1011.47,1032.84
Exp/Cntr=.3,.1

Type RM Length L Ch R = 1 ,8220.093,1836.79,1754.43,1679.5
XS GIS Cut Line= 2
     1868788.291         351370.      1867551.72      351391.789
#Sta/Elev= 30
       0  171.62   86.63   168.8  125.22  167.86  211.28  164.19  238.68  163.87
  248.35  164.08  249.08  164.27  292.39  163.04  508.86  162.73  516.94  154.65
  521.94  154.65  529.96  162.67  700.91   162.9  739.55  169.63  751.79   170.7
  779.09  171.18  807.24   173.9  830.49  175.74  853.24  177.09  935.02   179.4
 1004.36  179.44 1033.28  178.72 1072.96  178.59 1110.57  177.88 1153.62   176.4
 1170.27  176.15 1189.29  176.29 1198.31  182.09 1202.01  182.54 1236.76  183.56
#Mann= 3 , 0 , 0
       0     .16       0  508.86    .055       0  529.96     .16       0
Bank Sta=508.86,529.96
Exp/Cntr=.3,.1

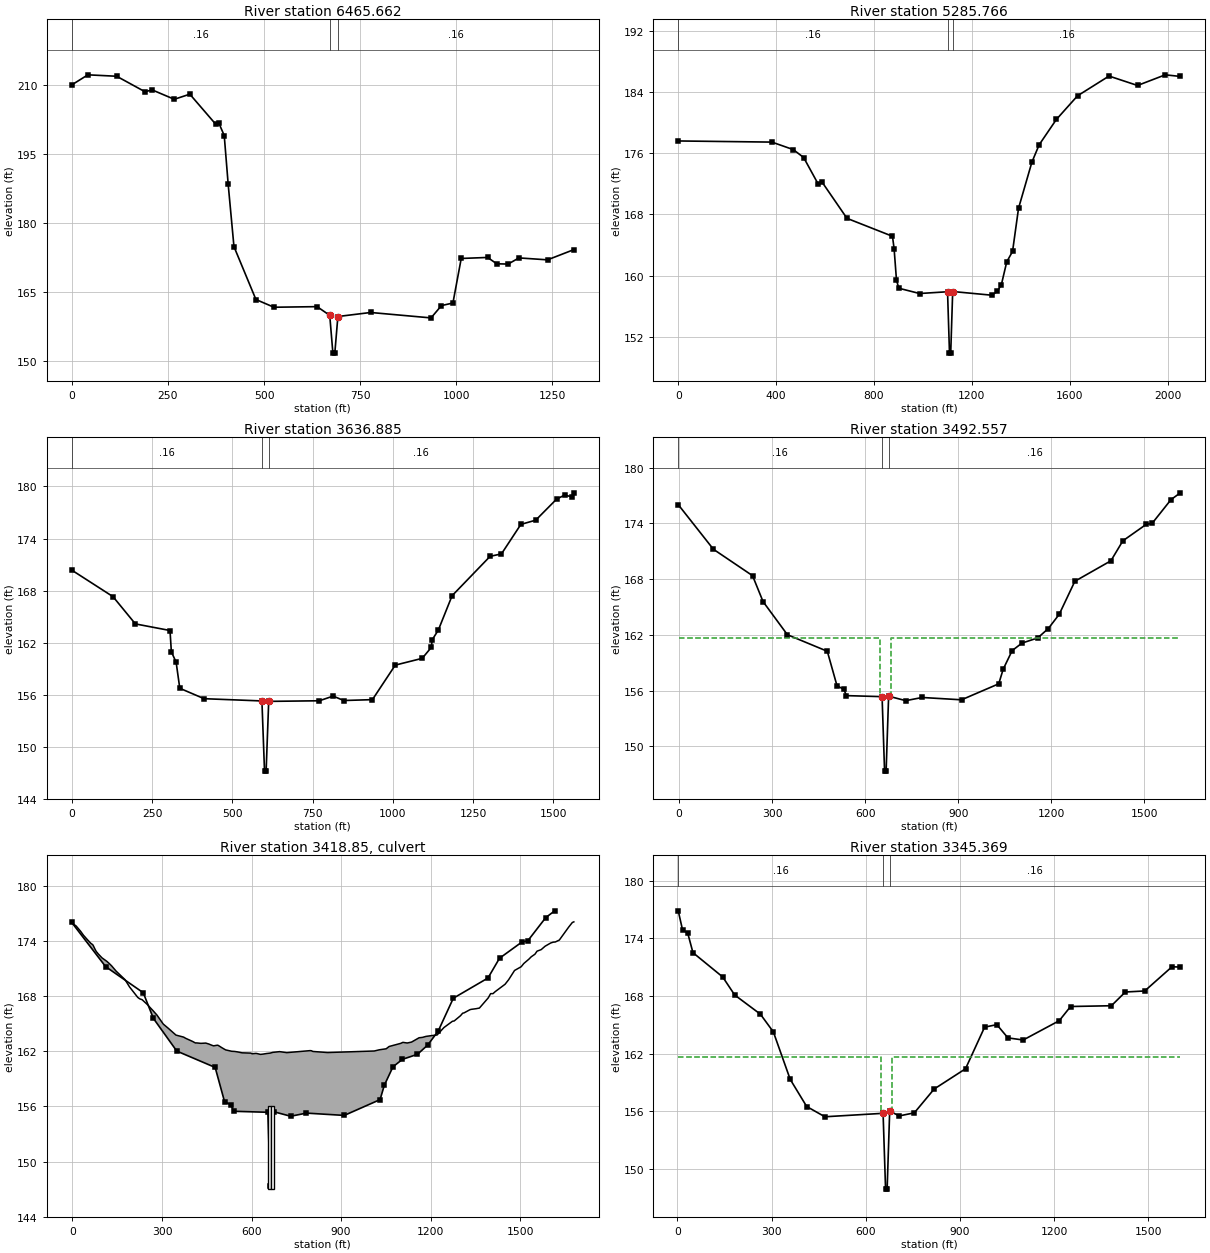
Type RM Length L Ch R = 1 ,6465.662,1128.25,1179.9,1166.59
XS GIS Cut Line= 2
     1867889.462      349686.737     1866723.707      350275.062
#Sta/Elev= 30
       0  210.01   41.92   212.2  116.78  211.89  190.04  208.54  209.69   208.9
  266.58  206.88  307.03  207.99  373.82  201.51  382.85  201.64  396.53  198.99
  406.83  188.35  421.82  174.84  478.94  163.33  525.89  161.65  638.05  161.78
  670.91  159.89  679.13  151.67  684.13  151.67  692.09  159.63  777.32  160.51
  934.34  159.33  961.52  162.01  991.29  162.57  1012.9  172.26 1081.58  172.48
  1105.2   171.1 1134.89  171.04 1162.98  172.38 1237.34  171.96  1305.8  174.18
#Mann= 3 , 0 , 0
       0     .16       0  670.91    .055       0  692.09     .16       0
Bank Sta=670.91,692.09
Exp/Cntr=.3,.1

Type RM Length L Ch R = 1 ,5285.766,1639.96,1648.88,1445.74
XS GIS Cut Line= 2
      1867957.57      348556.871     1866025.825       349249.78
#Sta/Elev= 30
       0  177.59   382.9  177.44  470.35  176.46  512.62  175.43  571.29  172.01
  587.32  172.25  689.76  167.49  875.67  165.15  882.33  163.55   892.1  159.42
  901.59  158.37  986.47  157.68 1100.78  157.91 1108.79   149.9 1113.79   149.9
 1121.83  157.94 1281.56  157.46 1304.28  157.96  1320.9  158.85 1342.87  161.82
 1366.52  163.17 1390.95   168.8 1445.45  174.81 1475.25  177.09 1545.48  180.39
 1632.11  183.48 1760.88  186.06 1877.42  184.83  1990.7  186.22 2052.26  186.01
#Mann= 3 , 0 , 0
       0     .16       0 1100.78    .055       0 1121.83     .16       0
Bank Sta=1100.78,1121.83
Exp/Cntr=.3,.1

Type RM Length L Ch R = 1 ,3636.885,146.64,144.33,190.98
XS GIS Cut Line= 2
     1866799.971      346886.747     1866091.803      348281.295
#Sta/Elev= 30
       0  170.36  128.53   167.3  198.13  164.16  306.03   163.4  310.22  160.95
  325.13  159.74  336.48  156.74  412.24  155.54  592.35  155.28  600.44  147.19
  605.44  147.19  613.48  155.23  771.19   155.3  814.25  155.84  847.14  155.33
  936.59  155.43 1007.73  159.41 1091.63  160.19 1119.95  161.45  1122.8  162.33
 1141.88  163.45 1184.77  167.41  1303.2  171.95 1338.54  172.23 1398.98  175.63
 1445.34  176.12 1510.22  178.54 1535.29  179.01 1558.05  178.81 1564.06  179.27
#Mann= 3 , 0 , 0
       0     .16       0  592.35    .055       0  613.48     .16       0
Bank Sta=592.35,613.48
Exp/Cntr=.5,.3

Type RM Length L Ch R = 1 ,3492.557,149.01,147.19,156.18
XS GIS Cut Line= 2
     1866718.352      346726.319     1866023.387      348188.045
#Sta/Elev= 30
   -2.38  176.01  111.02  171.21  237.17  168.37  271.06  165.58  349.54  162.02
  478.15  160.24  509.46  156.53  531.62  156.14  539.63  155.47  654.75  155.36
  662.76  147.35  667.76  147.35  675.82  155.41  731.03  154.93  784.15  155.27
  910.78  155.02 1030.82  156.74 1045.01   158.3 1074.04  160.31 1105.66  161.12
 1156.11  161.67 1190.53  162.68  1225.7  164.21 1276.21  167.77 1392.37  169.97
 1430.99  172.12 1506.35  173.89 1525.86  174.02 1586.15  176.55 1616.14  177.28
#Mann= 3 , 0 , 0
   -2.38     .16       0  654.75    .055       0  675.82     .16       0
#XS Ineff= 2 , 0
       0  646.93  161.66   683.6       0  161.66
Bank Sta=654.75,675.82
Exp/Cntr=.5,.3

Type RM Length L Ch R = 2 ,3418.85 ,,,
BEGIN DESCRIPTION:
US 501 (NCDOT 82 2021)
END DESCRIPTION:
Bridge Culvert--1,0,-1,-1, 0
Deck Dist Width WeirC Skew NumUp NumDn MinLoCord MaxHiCord MaxSubmerge Is_Ogee
55.71,36,2.6,0,132,132,161.66,,.95,0,0,0,,
       0    3.03   12.25   27.12   32.65   36.89    49.2   61.97   66.06   68.91
    75.6   80.08   82.57   85.83   98.98  109.07  115.33  123.45  130.99   136.4
  146.46  167.59  176.16  188.21  191.21  194.15  206.18  218.97  221.48  223.13
  226.45  233.42  248.07  253.34  255.71  270.14  283.04  304.18  321.21  321.27
  321.32   321.4  346.77  372.42  379.33  401.77  410.77  412.19  415.66  430.45
  446.71  451.41  456.75  468.07  472.88   485.4  487.39  489.31  500.98  513.14
  524.54  533.49  543.44  551.76  568.48  597.56  602.09  614.76  618.71  629.76
   638.1  649.28  662.31  671.28  683.47  694.21  718.21  796.28  800.16  805.81
  854.86 1011.44 1028.13 1051.14 1061.14 1099.89 1107.29 1121.77  1136.2 1161.51
 1172.68  1184.9 1197.57 1204.96 1221.74 1237.48 1244.78 1260.62 1273.14 1279.25
 1300.36 1307.47 1312.46 1331.74 1336.11 1352.28 1363.66 1385.27 1393.32 1401.26
 1409.24 1416.66 1449.63 1461.72 1475.71 1481.38 1499.67 1503.74 1512.43 1529.11
 1537.35 1549.75 1556.75  1570.7 1583.83 1602.56 1610.81 1617.97 1631.46 1662.84
 1675.05 1680.13
  175.92  175.84  175.63  175.06  174.82  174.62  174.17  173.73  173.64  173.55
   173.1  172.83  172.75  172.61  172.16  171.93  171.78  171.54   171.3  171.09
  170.71  170.06  169.79  169.14     169  168.88  168.38  167.85   167.8  167.75
  167.69  167.61  167.18  167.01  166.91  166.41  165.94  164.96  164.49  164.49
  164.49  164.49  163.76  163.54  163.41  163.08  162.93   162.9  162.91  162.86
  162.89  162.84  162.79  162.64  162.59  162.66  162.65  162.62  162.38  162.15
  162.06     162  161.98  161.94  161.83   161.8  161.73  161.77  161.75  161.66
  161.69  161.75   161.8  161.88  161.92  161.96  161.85  162.07  162.06  161.98
  161.86  162.03  162.16  162.27  162.52  162.86  162.97   162.9     163  163.47
  163.51  163.62  163.68  163.71  163.77  164.32  164.58  164.96  165.26   165.3
  165.87  166.14  166.18  166.52  166.56  166.63   166.7  167.51  167.81  168.27
  168.27  168.49  169.29  169.79   170.5  170.79  171.12   171.2  171.55  172.01
  172.28  172.56  172.89  173.06  173.43  173.78  173.87  173.89   174.1  175.51
  176.01  176.08
                                                                                
                                                                                
                                                                                
                                                                                
                                                                                
                                                                                
                                                                                
                                                                                
                                                                                
                                                                                
                                                                                
                                                                                
                                                                                
                
       0    3.03   12.25   27.12   32.65   36.89    49.2   61.97   66.06   68.91
    75.6   80.08   82.57   85.83   98.98  109.07  115.33  123.45  130.99   136.4
  146.46  167.59  176.16  188.21  191.21  194.15  206.18  218.97  221.48  223.13
  226.45  233.42  248.07  253.34  255.71  270.14  283.04  304.18  321.21  321.27
  321.32   321.4  346.77  372.42  379.33  401.77  410.77  412.19  415.66  430.45
  446.71  451.41  456.75  468.07  472.88   485.4  487.39  489.31  500.98  513.14
  524.54  533.49  543.44  551.76  568.48  597.56  602.09  614.76  618.71  629.76
   638.1  649.28  662.31  671.28  683.47  694.21  718.21  796.28  800.16  805.81
  854.86 1011.44 1028.13 1051.14 1061.14 1099.89 1107.29 1121.77  1136.2 1161.51
 1172.68  1184.9 1197.57 1204.96 1221.74 1237.48 1244.78 1260.62 1273.14 1279.25
 1300.36 1307.47 1312.46 1331.74 1336.11 1352.28 1363.66 1385.27 1393.32 1401.26
 1409.24 1416.66 1449.63 1461.72 1475.71 1481.38 1499.67 1503.74 1512.43 1529.11
 1537.35 1549.75 1556.75  1570.7 1583.83 1602.56 1610.81 1617.97 1631.46 1662.84
 1675.05 1680.13
  175.92  175.84  175.63  175.06  174.82  174.62  174.17  173.73  173.64  173.55
   173.1  172.83  172.75  172.61  172.16  171.93  171.78  171.54   171.3  171.09
  170.71  170.06  169.79  169.14     169  168.88  168.38  167.85   167.8  167.75
  167.69  167.61  167.18  167.01  166.91  166.41  165.94  164.96  164.49  164.49
  164.49  164.49  163.76  163.54  163.41  163.08  162.93   162.9  162.91  162.86
  162.89  162.84  162.79  162.64  162.59  162.66  162.65  162.62  162.38  162.15
  162.06     162  161.98  161.94  161.83   161.8  161.73  161.77  161.75  161.66
  161.69  161.75   161.8  161.88  161.92  161.96  161.85  162.07  162.06  161.98
  161.86  162.03  162.16  162.27  162.52  162.86  162.97   162.9     163  163.47
  163.51  163.62  163.68  163.71  163.77  164.32  164.58  164.96  165.26   165.3
  165.87  166.14  166.18  166.52  166.56  166.63   166.7  167.51  167.81  168.27
  168.27  168.49  169.29  169.79   170.5  170.79  171.12   171.2  171.55  172.01
  172.28  172.56  172.89  173.06  173.43  173.78  173.87  173.89   174.1  175.51
  176.01  176.08
                                                                                
                                                                                
                                                                                
                                                                                
                                                                                
                                                                                
                                                                                
                                                                                
                                                                                
                                                                                
                                                                                
                                                                                
                                                                                
                
Multiple Barrel Culv=2,9,9,36,.012,.4,1,8,1,147,146.98, 2,Culvert #1  , 0 ,55.71
  660.43  660.43   670.1   670.1
BC Design=,, 0 ,, 0 ,,,,,,

Type RM Length L Ch R = 1 ,3345.369,156.3,180.18,160.79
XS GIS Cut Line= 2
      1866583.38      346671.756     1865897.029      348116.251
#Sta/Elev= 30
    2.38  176.88   16.01   174.9   32.61  174.56   49.28  172.52  143.94  169.99
  182.19  168.11  264.08  166.11  305.41  164.26     359  159.32  411.53  156.49
  469.54  155.42  654.88  155.78  662.78  147.88  667.78  147.88  675.91  156.01
  706.38  155.51  754.42  155.83   817.5  158.31  917.43  160.42  978.25  164.76
 1017.21  165.02 1052.55  163.64 1101.22  163.42 1215.95  165.43 1252.18  166.91
  1382.1  166.99 1426.48  168.42 1488.29  168.53 1575.08  171.05 1601.64  171.02
#Mann= 3 , 0 , 0
    2.38     .16       0  654.88    .055       0  675.91     .16       0
#XS Ineff= 2 , 0
       0  646.93  161.66   683.6       0  161.66
Bank Sta=654.88,675.91
Exp/Cntr=.5,.3

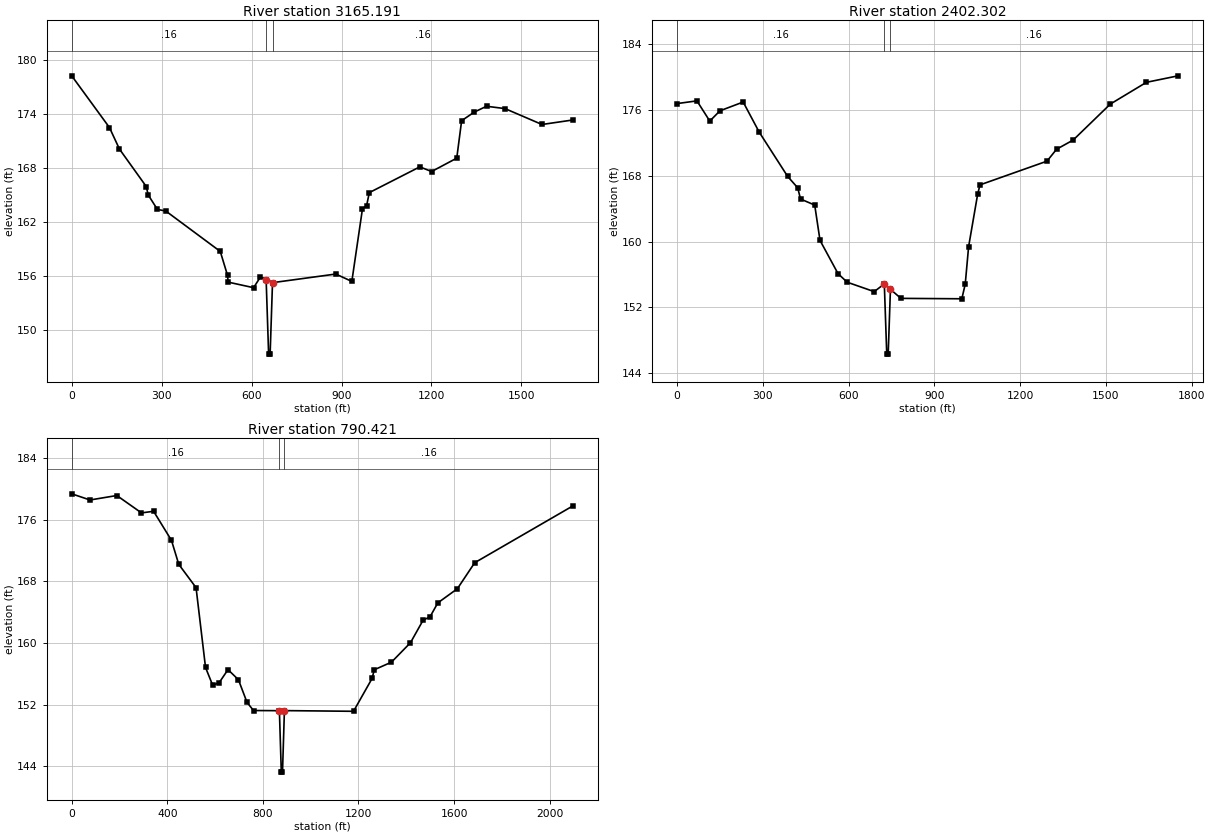
Type RM Length L Ch R = 1 ,3165.191,738.01,762.89,771.44
XS GIS Cut Line= 2
      1866513.98      346532.663     1865751.337      348019.817
#Sta/Elev= 30
       0  178.26  125.86   172.5  159.21   170.1  248.66  165.93  254.98     165
  285.77  163.38  313.83   163.2   495.5   158.7  519.67  156.04  521.87  155.28
  606.68  154.66   629.4  155.85  648.53  155.56  656.83  147.26  661.83  147.26
  669.79  155.22  880.79  156.18  934.41  155.36  969.95  163.47  983.69   163.8
  992.66  165.25 1161.13  168.12 1200.45   167.6 1284.37  169.09 1300.62  173.26
 1342.23  174.21 1383.63  174.87 1445.25  174.61 1568.73  172.84  1671.3  173.34
#Mann= 3 , 0 , 0
       0     .16       0  648.53    .055       0  669.79     .16       0
Bank Sta=648.53,669.79
Exp/Cntr=.3,.1

Type RM Length L Ch R = 1 ,2402.302,1578.27,1611.88,1606.76
XS GIS Cut Line= 2
     1866050.955      345939.457       1865239.3      347492.696
#Sta/Elev= 30
       0   176.8   69.57  177.13  114.59  174.67   150.1  175.92  231.36  176.99
  287.48  173.32  386.94  167.93  422.19  166.54  431.86  165.18  481.58  164.44
  500.11  160.14  563.18  156.09  595.02  155.05  689.67   153.9  725.01  154.84
  733.56  146.29  738.56  146.29  746.45  154.18  783.11  153.08  996.22  153.03
 1008.09  154.82 1019.88  159.38  1051.4  165.74 1059.62   166.9 1294.06  169.79
 1327.54  171.24 1385.64  172.36 1515.51  176.74 1641.88  179.39 1752.52  180.18
#Mann= 3 , 0 , 0
       0     .16       0  725.01    .055       0  746.45     .16       0
Bank Sta=725.01,746.45
Exp/Cntr=.3,.1

Type RM Length L Ch R = 1 ,790.421 ,,,
XS GIS Cut Line= 4
     1865104.998      344981.821     1864579.466      345443.121
     1864223.272      346021.206      1864234.95      346739.434
#Sta/Elev= 30
       0   179.4   76.55   178.6  188.73  179.18  291.99  176.92  342.65  177.13
  417.39  173.35  447.95  170.23   520.3   167.2  559.95  156.82   590.1  154.49
  617.42  154.86  653.93  156.54  697.54  155.23   733.7  152.27  760.92  151.22
  869.04   151.2  877.03  143.21  882.03  143.21  890.03  151.21 1179.22  151.12
 1257.08   155.4  1265.9  156.52 1338.01  157.51 1417.59  160.04 1470.63  162.98
 1499.02  163.39 1532.06  165.22 1613.81  167.06 1686.27  170.44 2096.61  177.82
#Mann= 3 , 0 , 0
       0     .16       0  869.04    .055       0  890.03     .16       0
Bank Sta=869.04,890.03
Exp/Cntr=.3,.1

River Reach=Bridge          ,Upper
Junct Up Dn=                ,2
Reach XY= 30
       1851508.8      378712.669     1851058.707      376672.043
     1852846.058      373836.941     1853122.049      372943.169
     1853075.201      371306.593     1852582.138      370092.409
     1853520.813      368029.583     1854082.152      365302.562
     1853875.504      364411.131     1854568.334      362441.129
     1854849.683      362105.544     1855547.972      362000.461
     1856097.112      360983.536     1856619.892      360882.217
      1857353.38      360192.521     1858138.636       360074.01
     1858102.907      359426.032     1859671.181      357753.461
     1859894.944      356794.802     1861255.231      355987.639
     1862284.108       354346.39     1862751.947      353435.866
     1862644.055      352786.227     1863348.028      351638.431
     1863405.867      350311.108     1863102.769      349599.188
      1863317.58      348457.031     1863031.498      347569.689
     1863330.201      346075.787     1863830.082      345243.287

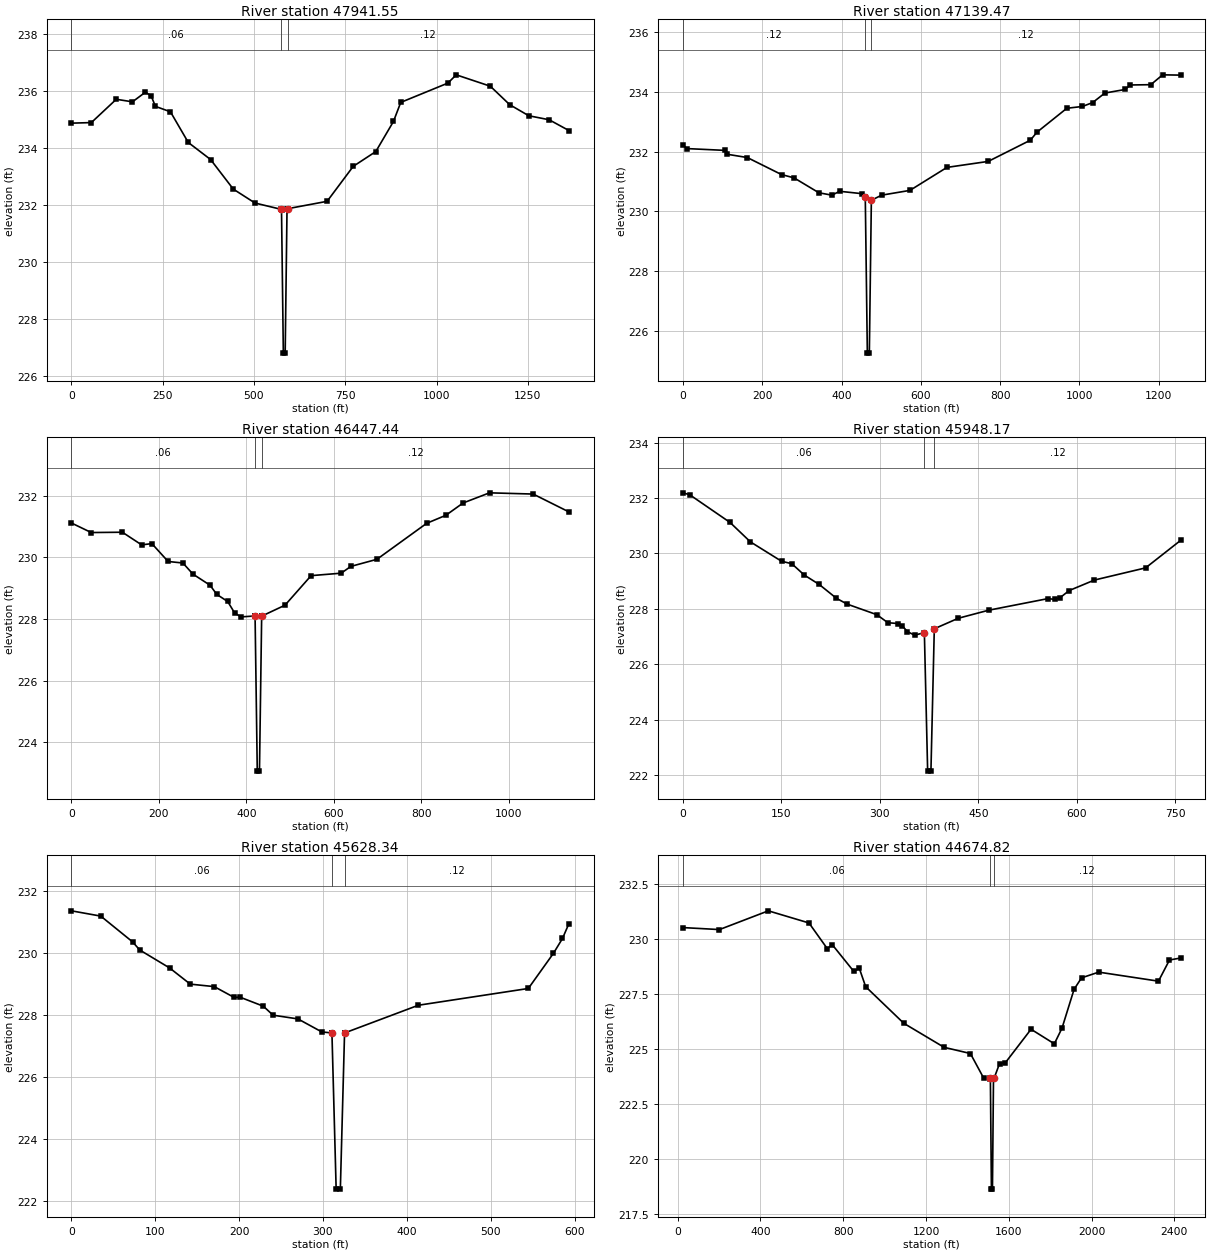
Type RM Length L Ch R = 1 ,47941.55,796.62,802.08,806.57
XS GIS Cut Line= 2
     1852025.145      378428.768     1850775.902       378973.31
#Sta/Elev= 30
       0  234.88   54.61   234.9  122.89  235.72   167.2  235.63  202.74  235.97
  218.35  235.84   230.1  235.47  271.21  235.28  320.11   234.2  381.23   233.6
  443.37  232.56  502.89  232.07  573.93  231.85  575.44  231.84  580.49  226.79
  585.49  226.79  590.56  231.86  592.04  231.87  700.32  232.13  771.89  233.36
  833.67  233.88  882.09  234.94  902.03  235.61 1031.36  236.29 1053.97  236.58
 1147.37  236.18  1200.5  235.53  1252.8  235.14 1308.43     235 1362.77  234.62
#Mann= 3 , 0 , 0
       0     .06       0  573.93    .055       0  592.04     .12       0
Bank Sta=573.93,592.04
Exp/Cntr=.3,.1

Type RM Length L Ch R = 1 ,47139.47,672.81,692.03,711.28
XS GIS Cut Line= 2
     1851726.181      377720.508     1850555.238      378172.513
#Sta/Elev= 30
       0  232.23    9.49   232.1  105.34  232.04  111.43  231.91  162.21   231.8
  248.49  231.23  280.05  231.12   342.8  230.62  375.64  230.54  395.13  230.67
  451.41  230.59  459.82  230.48  465.05  225.25  470.05  225.25  475.17  230.37
  501.16  230.54  572.54   230.7  665.87  231.47  769.89  231.67  876.23  232.38
  893.07  232.65  968.29  233.45 1007.37  233.51 1033.34  233.64  1064.3  233.96
 1115.64  234.08  1128.1  234.23 1180.13  234.24 1210.04  234.57 1255.16  234.56
#Mann= 3 , 0 , 0
       0     .12       0  459.82    .055       0  475.17     .12       0
Bank Sta=459.82,475.17
Exp/Cntr=.3,.1

Type RM Length L Ch R = 1 ,46447.44,497.86,499.28,504.93
XS GIS Cut Line= 2
     1851509.076      377204.439     1850373.724      377275.621
#Sta/Elev= 30
       0  231.12   45.32  230.81  116.53  230.82  160.48  230.41  183.98  230.45
  221.08  229.87  254.92  229.82  277.83  229.46  316.84   229.1  332.47   228.8
  357.28  228.57  373.52  228.19  388.26  228.07   419.1   228.1  419.92   228.1
  424.96  223.06  429.96  223.06     435   228.1  435.82   228.1  488.36  228.45
  548.06  229.41  616.87  229.49  638.86  229.71  698.43  229.94  812.31  231.11
  856.14  231.37  895.53  231.77  955.95   232.1 1055.81  232.06 1137.58  231.48
#Mann= 3 , 0 , 0
       0     .06       0   419.1    .055       0  435.82     .12       0
Bank Sta=419.1,435.82
Exp/Cntr=.3,.1

Type RM Length L Ch R = 1 ,45948.17,276.65,319.83,349.74
XS GIS Cut Line= 2
     1851430.776      376723.961     1850672.688      376741.756
#Sta/Elev= 29
       0  232.19   10.27  232.12   71.71  231.12  102.66  230.42  150.13  229.72
  165.82  229.63  184.88  229.22  207.65  228.88  233.92  228.38  250.29  228.17
  295.41  227.79  312.19   227.5  327.49  227.47  334.53  227.38  341.89  227.18
   352.9  227.05  367.86  227.14  372.86  222.14  377.86  222.14     383  227.28
   419.5  227.66  465.67  227.95  556.26  228.37  567.05  228.34  575.09  228.41
  588.49  228.66  627.01  229.04  705.08  229.48   758.3  230.47
#Mann= 3 , 0 , 0
       0     .06       0  367.86    .055       0     383     .12       0
Bank Sta=367.86,383
Exp/Cntr=.3,.1

Type RM Length L Ch R = 1 ,45628.34,1148.76,953.52,751.24
XS GIS Cut Line= 2
     1851459.249       376606.51     1850946.739      376307.546
#Sta/Elev= 24
       0  231.35   35.01  231.18   72.95  230.35   81.45  230.09  117.14  229.51
  141.71  228.99  170.33  228.91   194.2  228.56  201.06  228.57  228.82  228.28
   240.5  227.99  270.16  227.87  298.67  227.45  310.45  227.42  310.68  227.42
  315.71  222.39  320.71  222.39  325.74  227.42  325.97  227.42  413.73  228.31
  544.89  228.85  574.79  229.98  585.63  230.46  593.33  230.94
#Mann= 3 , 0 , 0
       0     .06       0  310.45    .055       0  325.97     .12       0
#XS Ineff= 1 ,-1
  298.22  331.42  227.45
Bank Sta=310.45,325.97
Exp/Cntr=.5,.3

Type RM Length L Ch R = 1 ,44674.82,377.01,98.81,217.76
XS GIS Cut Line= 6
     1853020.421      375141.107     1852556.618      375071.496
     1851821.536      375664.304     1851778.152      375676.912
      1851610.28      375851.847     1851064.896      376293.759
#Sta/Elev= 30
   25.88  230.51  201.99  230.42  438.23  231.27  634.59  230.72  723.51  229.55
  746.71  229.74   850.6  228.53  877.98  228.66  908.55  227.83 1092.85  226.17
  1287.7  225.08 1414.58   224.8  1479.1  223.68 1508.61  223.67 1511.24  223.66
 1516.25  218.65 1521.25  218.65 1526.26  223.66 1528.89  223.67 1555.44  224.34
 1583.44  224.38 1707.72   225.9 1820.33  225.24 1857.41  225.95 1915.71  227.71
 1951.69  228.23 2034.81  228.49 2323.49  228.08 2376.75  229.04 2430.19  229.13
#Mann= 3 , 0 , 0
   25.88     .06       0 1508.61    .055       0 1528.89     .12       0
Bank Sta=1508.61,1528.89
Exp/Cntr=.5,.3