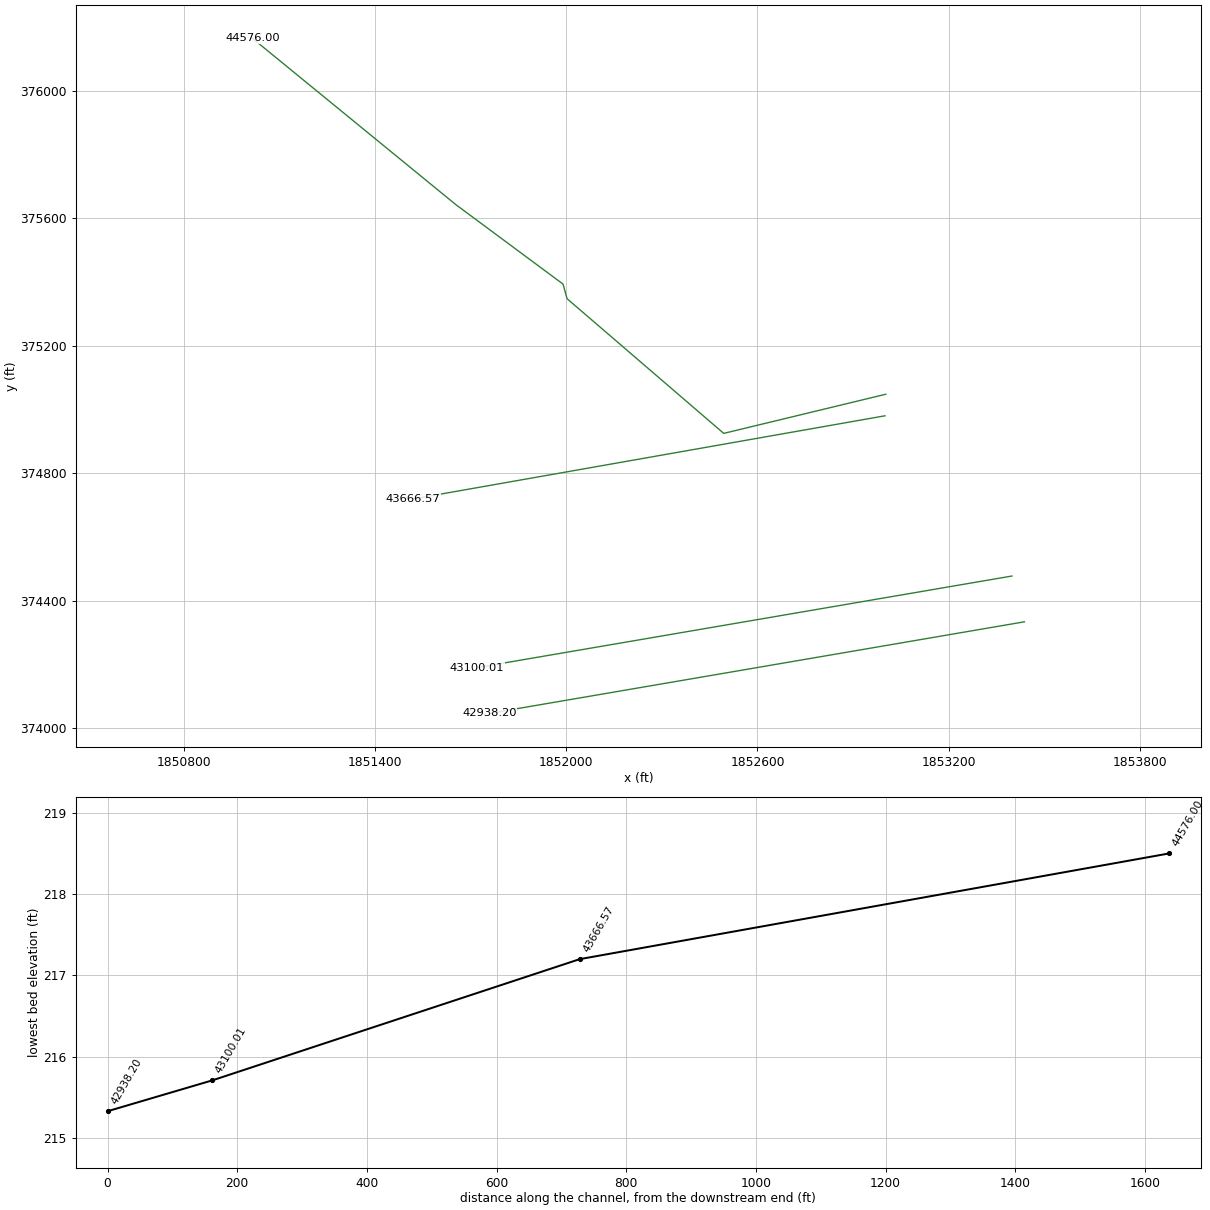
HEC-RAS study bridge.prj: Bridge Creek to Leith Creek

--- bridge.g02 (geometry) --- (continued)

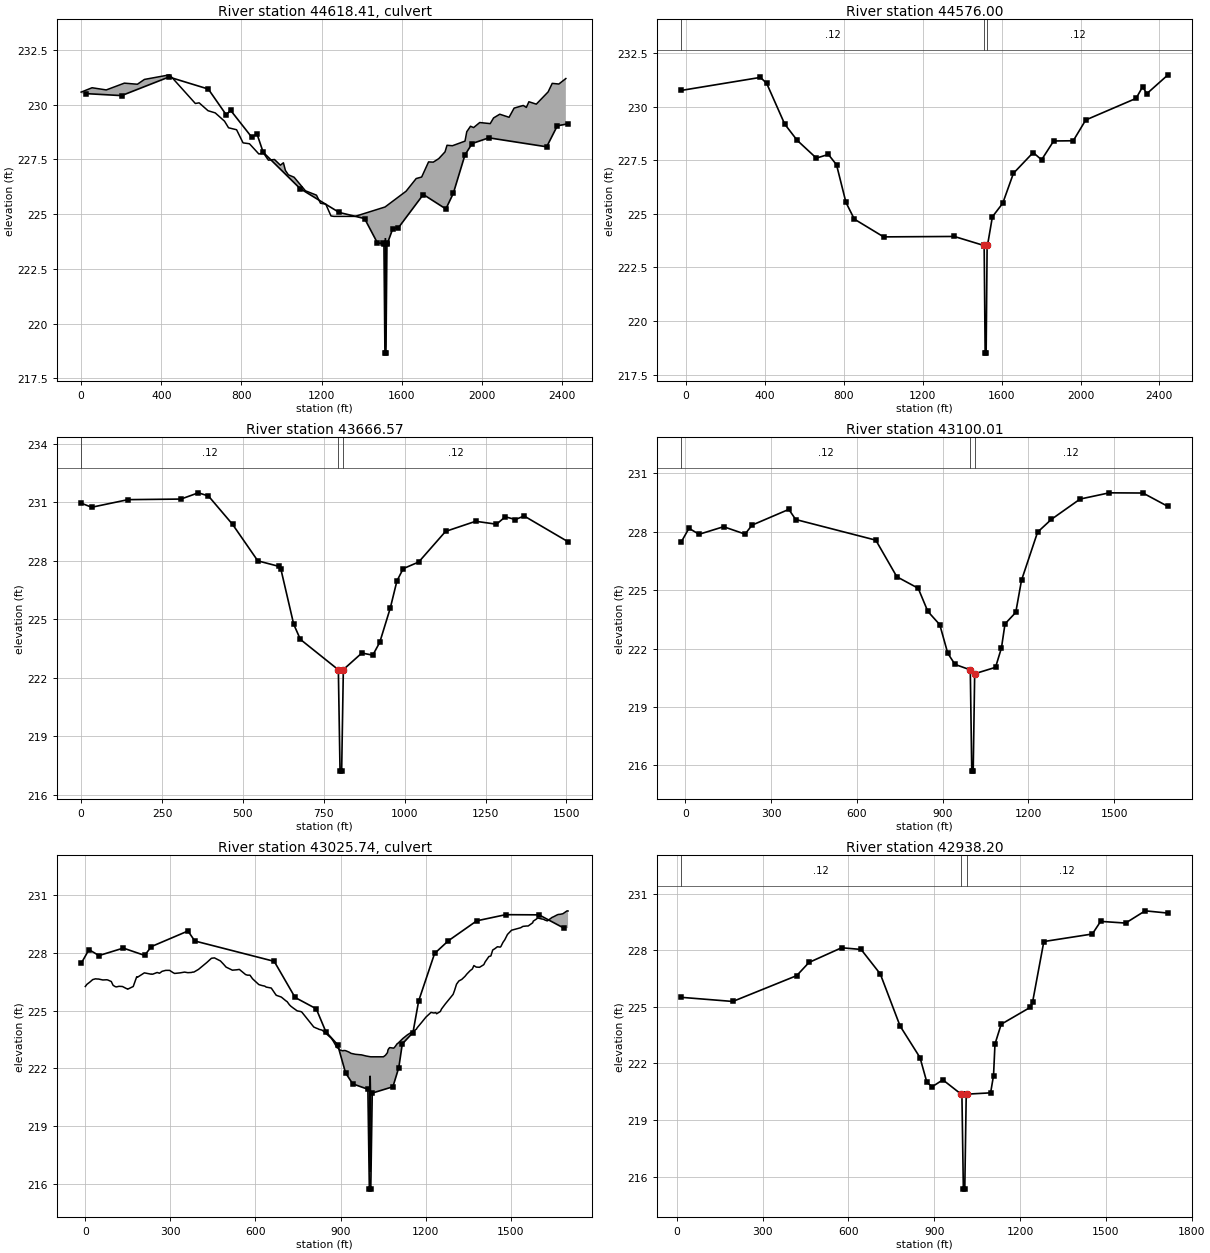
Type RM Length L Ch R = 2 ,44618.41,,,
BEGIN DESCRIPTION:
US Bus 74 (NCDOT 82 2009)
END DESCRIPTION:
Bridge Culvert--1,0,-1,-1, 0
Deck Dist Width WeirC Skew NumUp NumDn MinLoCord MaxHiCord MaxSubmerge Is_Ogee
39.91,33,2.6,0, 60, 60,224.9,,.95,0,0,0,,
       0   54.52  125.26  215.62  280.73  315.78  441.37  569.97  588.86  633.31
  669.32  715.71  735.67  775.78  808.07  840.08  887.14  909.76  934.49  965.11
   994.3  1009.6 1019.51 1034.19 1062.86  1119.4 1174.56 1194.64 1220.92 1246.97
 1261.57  1366.9 1516.83 1621.62 1672.14 1699.52  1733.9 1757.56 1784.81 1816.17
 1826.03 1853.17 1915.79 1924.62 1943.24 1958.78 1989.28 2041.65 2058.41 2089.25
 2135.74 2160.96 2206.67 2221.99 2234.66 2271.64 2330.69  2351.1 2384.06 2419.18
  230.58  230.78  230.68  230.99  230.94  231.16  231.37  230.06  230.09  229.73
  229.63  229.25  228.95  228.86  228.26  228.22  227.75   227.8  227.47   227.5
  227.24  227.35     227   226.8  226.69  226.07  225.87   225.5  225.46  224.92
   224.9   224.9  225.33  226.05  226.63   226.7  227.39  227.38  227.54  227.85
  228.15  228.13  228.34  228.77  229.02  228.96  229.19  229.14   229.4  229.57
  229.43  229.85  229.97  229.88  230.14  230.03  230.59  230.98  230.95   231.2
                                                                                
                                                                                
                                                                                
                                                                                
                                                                                
                                                                                
       0   54.52  125.26  215.62  280.73  315.78  441.37  569.97  588.86  633.31
  669.32  715.71  735.67  775.78  808.07  840.08  887.14  909.76  934.49  965.11
   994.3  1009.6 1019.51 1034.19 1062.86  1119.4 1174.56 1194.64 1220.92 1246.97
 1261.57  1366.9 1516.83 1621.62 1672.14 1699.52  1733.9 1757.56 1784.81 1816.17
 1826.03 1853.17 1915.79 1924.62 1943.24 1958.78 1989.28 2041.65 2058.41 2089.25
 2135.74 2160.96 2206.67 2221.99 2234.66 2271.64 2330.69  2351.1 2384.06 2419.18
  230.58  230.78  230.68  230.99  230.94  231.16  231.37  230.06  230.09  229.73
  229.63  229.25  228.95  228.86  228.26  228.22  227.75   227.8  227.47   227.5
  227.24  227.35     227   226.8  226.69  226.07  225.87   225.5  225.46  224.92
   224.9   224.9  225.33  226.05  226.63   226.7  227.39  227.38  227.54  227.85
  228.15  228.13  228.34  228.77  229.02  228.96  229.19  229.14   229.4  229.57
  229.43  229.85  229.97  229.88  230.14  230.03  230.59  230.98  230.95   231.2
                                                                                
                                                                                
                                                                                
                                                                                
                                                                                
                                                                                
Culvert=1,5,,33,.012,.5,1,1,1,218.91,1518.75,218.89,1518.75,Culvert #1  , 0 ,39.91
BC Design=,, 0 ,, 0 ,,,,,,

Type RM Length L Ch R = 1 ,44576.00,427.66,909.43,962.03
XS GIS Cut Line= 6
     1853002.625      375047.717     1852494.104       374924.91
     1852002.612      375347.421     1851989.852      375393.346
     1851653.393      375642.747     1851015.316      376164.419
#Sta/Elev= 30
  -25.88  230.77  376.74  231.38   408.4   231.1  499.67   229.2  562.98  228.44
  660.22  227.61  721.08  227.78  762.52   227.3   810.3  225.54  852.79  224.76
 1001.48  223.93 1359.69  223.95 1509.35  223.53 1511.23  223.52 1516.25   218.5
 1521.25   218.5 1526.27  223.52 1528.15  223.53 1553.01  224.87 1605.42   225.5
  1659.7   226.9 1759.81  227.87 1802.52  227.53 1863.74  228.41 1963.07  228.42
 2026.32  229.39 2281.66   230.4 2314.76  230.94 2336.39  230.62 2443.49   231.5
#Mann= 3 , 0 , 0
  -25.88     .12       0 1509.35    .055       0 1528.15     .12       0
Bank Sta=1509.35,1528.15
Exp/Cntr=.5,.3

Type RM Length L Ch R = 1 ,43666.57,567.81,566.55,565.45
XS GIS Cut Line= 2
     1853000.083      374980.083     1851517.893      374718.905
#Sta/Elev= 30
       0  230.95   32.63  230.74  144.95  231.13  308.61  231.16   362.1  231.48
  393.34  231.32  468.12  229.86  546.04  227.99  612.75   227.7  617.19  227.58
  656.95  224.74  677.61  223.96  795.03   222.4  800.23   217.2  805.23   217.2
  810.44  222.41  867.66  223.26  901.44  223.15  923.01  223.81  955.58  225.57
  976.11  226.96  995.53  227.59 1043.41  227.93 1126.39   229.5 1219.46  230.02
 1283.69  229.87  1311.1  230.25 1342.07  230.11 1369.41  230.29 1505.03  228.97
#Mann= 3 , 0 , 0
       0     .12       0  795.03    .055       0  810.44     .12       0
Bank Sta=795.03,810.44
Exp/Cntr=.5,.3

Type RM Length L Ch R = 1 ,43100.01,156.66,161.81,154.75
XS GIS Cut Line= 2
     1853398.381      374477.314     1851720.307      374190.018
#Sta/Elev= 30
  -14.71  227.46   12.94  228.18   48.12  227.87  133.97  228.26  209.12  227.88
  233.26  228.34  362.03  229.15  386.06  228.63  666.17  227.57  739.76  225.69
  814.38   225.1  848.17  223.91  889.84  223.23  917.84  221.76  943.05  221.19
  996.53  220.91 1001.73  215.71 1006.73  215.71 1011.89  220.71 1084.85  221.04
 1105.56  222.04 1117.93  223.27 1155.51  223.86 1175.64  225.51 1231.82  227.98
 1280.22  228.64 1380.51  229.68  1482.6     230 1600.21  229.99 1687.78   229.3
#Mann= 3 , 0 , 0
  -14.71     .12       0  996.53    .055       0 1011.89     .12       0
Bank Sta=996.53,1011.89
Exp/Cntr=.5,.3

Type RM Length L Ch R = 2 ,43025.74,,,
BEGIN DESCRIPTION:
NC 79 (assumed same as US Bus 74)
END DESCRIPTION:
Bridge Culvert--1,0,-1,-1, 0
Deck Dist Width WeirC Skew NumUp NumDn MinLoCord MaxHiCord MaxSubmerge Is_Ogee
57.77,33,2.6,0,193,193,222.6,,.95,0,0,0,,
       0    5.48   16.01   26.14   36.03   41.38   46.27   61.79   75.37   79.15
   91.57   98.07     106  110.07  118.77  130.97  145.33  147.76  149.41  169.02
  178.54  181.32  183.86  207.16  208.21  232.51   233.5  237.46  253.33  261.64
  265.24  270.66  283.52  297.29  309.61  312.41  314.99   334.6  349.96   361.6
   374.1  378.68  380.84  382.73  387.45  399.07  428.49  428.52  428.54  444.87
  455.42  476.62  487.55  496.43  516.86  518.63  534.35  543.18  560.56  562.33
   565.4  572.29  580.66  589.86  611.92   623.3  632.83  637.82   655.8  673.31
  673.79  673.96  691.26  706.85  711.83  719.69  725.14  733.18  747.32  758.32
  762.87  782.17  785.67  791.64  805.71   816.4  818.92  824.12  834.76  841.59
   856.3  861.91  867.28  875.06  882.65  887.74  889.93  898.35  908.48  911.99
  917.82  930.61  937.04  952.84  974.33  990.74 1006.26 1051.34 1058.51 1065.67
 1067.25 1069.83 1073.45 1087.68 1092.61 1099.75 1103.01 1118.88  1120.1 1120.31
 1125.48 1135.08 1135.36 1135.67 1167.76 1170.28  1187.2 1197.33 1201.49 1216.02
 1219.04 1229.36 1236.07 1238.87 1245.75 1252.12 1256.27 1269.51 1291.29  1297.1
 1301.86 1309.14 1317.57 1327.68 1339.09 1345.63 1357.52 1364.84 1370.42 1378.68
 1390.32 1404.69 1406.58  1409.6 1423.28 1430.26 1436.77 1444.44  1453.4 1463.24
 1465.59    1473 1479.24 1488.78 1499.27 1503.17 1521.28 1521.33  1535.5 1543.34
  1555.8 1561.74 1577.92 1579.52 1591.76 1594.81 1611.43 1614.52 1620.96 1628.54
 1629.87 1645.88 1646.27 1651.17  1664.1 1667.56  1675.1 1683.62 1684.27 1692.37
 1698.12  1699.2 1702.49
  226.26  226.37  226.49  226.62  226.66  226.65  226.65   226.6  226.61   226.6
  226.52  226.32  226.25  226.24  226.27  226.26  226.15  226.14  226.12  226.26
  226.65  226.77  226.74  226.96  226.97   226.9  226.91   226.9  226.99  226.95
  226.99  227.05   227.1   227.1  226.98  226.96  226.94  226.97  227.01  226.98
  226.99  227.01  227.01  227.01  227.05  227.15  227.51  227.51  227.51  227.73
  227.75  227.59  227.42  227.27  227.12  227.11  227.13  227.15  226.94  226.92
  226.88  226.85  226.85  226.66  226.36  226.31  226.28  226.23  226.18   225.8
   225.8   225.8  225.71  225.52  225.47  225.31  225.23  225.14  224.99  224.96
  224.94  224.59  224.53  224.41  224.15  224.08  224.07  224.03  223.99  223.91
  223.72  223.64  223.57   223.4   223.2  223.07  223.08  222.95  222.91  222.93
  222.92  222.84  222.78  222.73   222.7  222.64   222.6   222.6  222.68  222.82
  222.95  223.02  223.08  223.05  223.13  223.28  223.31  223.54  223.56  223.56
  223.62  223.74  223.74  223.74  224.04  224.11  224.41   224.6  224.67  224.87
  224.91  224.88   224.9  224.84   224.9  224.96  225.09  225.35  225.74  225.85
  226.04  226.38  226.55  226.63  226.79  226.91  227.09  227.17  227.35  227.27
  227.26  227.39  227.43  227.53  227.82  227.85  228.16  228.23  228.33  228.31
  228.34  228.56  228.69  228.97  229.13  229.19  229.26  229.26  229.32  229.39
  229.41  229.41  229.58  229.66  229.78  229.83  229.77  229.77  229.72  229.68
  229.68  229.85  229.86  229.89  229.99  230.01  230.02  230.05  230.05  230.13
  230.19   230.2  230.19
                                                                                
                                                                                
                                                                                
                                                                                
                                                                                
                                                                                
                                                                                
                                                                                
                                                                                
                                                                                
                                                                                
                                                                                
                                                                                
                                                                                
                                                                                
                                                                                
                                                                                
                                                                                
                                                                                
                        
       0    5.48   16.01   26.14   36.03   41.38   46.27   61.79   75.37   79.15
   91.57   98.07     106  110.07  118.77  130.97  145.33  147.76  149.41  169.02
  178.54  181.32  183.86  207.16  208.21  232.51   233.5  237.46  253.33  261.64
  265.24  270.66  283.52  297.29  309.61  312.41  314.99   334.6  349.96   361.6
   374.1  378.68  380.84  382.73  387.45  399.07  428.49  428.52  428.54  444.87
  455.42  476.62  487.55  496.43  516.86  518.63  534.35  543.18  560.56  562.33
   565.4  572.29  580.66  589.86  611.92   623.3  632.83  637.82   655.8  673.31
  673.79  673.96  691.26  706.85  711.83  719.69  725.14  733.18  747.32  758.32
  762.87  782.17  785.67  791.64  805.71   816.4  818.92  824.12  834.76  841.59
   856.3  861.91  867.28  875.06  882.65  887.74  889.93  898.35  908.48  911.99
  917.82  930.61  937.04  952.84  974.33  990.74 1006.26 1051.34 1058.51 1065.67
 1067.25 1069.83 1073.45 1087.68 1092.61 1099.75 1103.01 1118.88  1120.1 1120.31
 1125.48 1135.08 1135.36 1135.67 1167.76 1170.28  1187.2 1197.33 1201.49 1216.02
 1219.04 1229.36 1236.07 1238.87 1245.75 1252.12 1256.27 1269.51 1291.29  1297.1
 1301.86 1309.14 1317.57 1327.68 1339.09 1345.63 1357.52 1364.84 1370.42 1378.68
 1390.32 1404.69 1406.58  1409.6 1423.28 1430.26 1436.77 1444.44  1453.4 1463.24
 1465.59    1473 1479.24 1488.78 1499.27 1503.17 1521.28 1521.33  1535.5 1543.34
  1555.8 1561.74 1577.92 1579.52 1591.76 1594.81 1611.43 1614.52 1620.96 1628.54
 1629.87 1645.88 1646.27 1651.17  1664.1 1667.56  1675.1 1683.62 1684.27 1692.37
 1698.12  1699.2 1702.49
  226.26  226.37  226.49  226.62  226.66  226.65  226.65   226.6  226.61   226.6
  226.52  226.32  226.25  226.24  226.27  226.26  226.15  226.14  226.12  226.26
  226.65  226.77  226.74  226.96  226.97   226.9  226.91   226.9  226.99  226.95
  226.99  227.05   227.1   227.1  226.98  226.96  226.94  226.97  227.01  226.98
  226.99  227.01  227.01  227.01  227.05  227.15  227.51  227.51  227.51  227.73
  227.75  227.59  227.42  227.27  227.12  227.11  227.13  227.15  226.94  226.92
  226.88  226.85  226.85  226.66  226.36  226.31  226.28  226.23  226.18   225.8
   225.8   225.8  225.71  225.52  225.47  225.31  225.23  225.14  224.99  224.96
  224.94  224.59  224.53  224.41  224.15  224.08  224.07  224.03  223.99  223.91
  223.72  223.64  223.57   223.4   223.2  223.07  223.08  222.95  222.91  222.93
  222.92  222.84  222.78  222.73   222.7  222.64   222.6   222.6  222.68  222.82
  222.95  223.02  223.08  223.05  223.13  223.28  223.31  223.54  223.56  223.56
  223.62  223.74  223.74  223.74  224.04  224.11  224.41   224.6  224.67  224.87
  224.91  224.88   224.9  224.84   224.9  224.96  225.09  225.35  225.74  225.85
  226.04  226.38  226.55  226.63  226.79  226.91  227.09  227.17  227.35  227.27
  227.26  227.39  227.43  227.53  227.82  227.85  228.16  228.23  228.33  228.31
  228.34  228.56  228.69  228.97  229.13  229.19  229.26  229.26  229.32  229.39
  229.41  229.41  229.58  229.66  229.78  229.83  229.77  229.77  229.72  229.68
  229.68  229.85  229.86  229.89  229.99  230.01  230.02  230.05  230.05  230.13
  230.19   230.2  230.19
                                                                                
                                                                                
                                                                                
                                                                                
                                                                                
                                                                                
                                                                                
                                                                                
                                                                                
                                                                                
                                                                                
                                                                                
                                                                                
                                                                                
                                                                                
                                                                                
                                                                                
                                                                                
                                                                                
                        
Culvert=1,5,,33,.012,.5,1,1,1,216.61,1004.23,216.59,1004.23,Culvert #1  , 0 ,57.77
BC Design=,, 0 ,, 0 ,,,,,,

Type RM Length L Ch R = 1 ,42938.20,684.27,707.65,687.36
XS GIS Cut Line= 2
     1853437.558      374333.666     1851759.484      374046.369
#Sta/Elev= 30
   14.71  225.51  195.61  225.29  419.01  226.66     462  227.36   576.1  228.14
  644.22  228.05  711.29  226.75  780.41  223.99   850.2  222.31  874.13     221
  892.31  220.76  930.05  221.13  994.83  220.36  996.71  220.35 1001.73  215.33
 1006.73  215.33 1011.76  220.36 1013.63  220.37 1097.01  220.44 1107.25  221.36
 1112.29  223.03    1134  224.08  1235.9  224.98 1243.59  225.24 1283.11  228.47
 1452.71  228.87 1481.73  229.54 1569.01  229.45 1637.43   230.1  1717.2  229.98
#Mann= 3 , 0 , 0
   14.71     .12       0  994.83    .055       0 1013.63     .12       0
Bank Sta=994.83,1013.63
Exp/Cntr=.5,.3