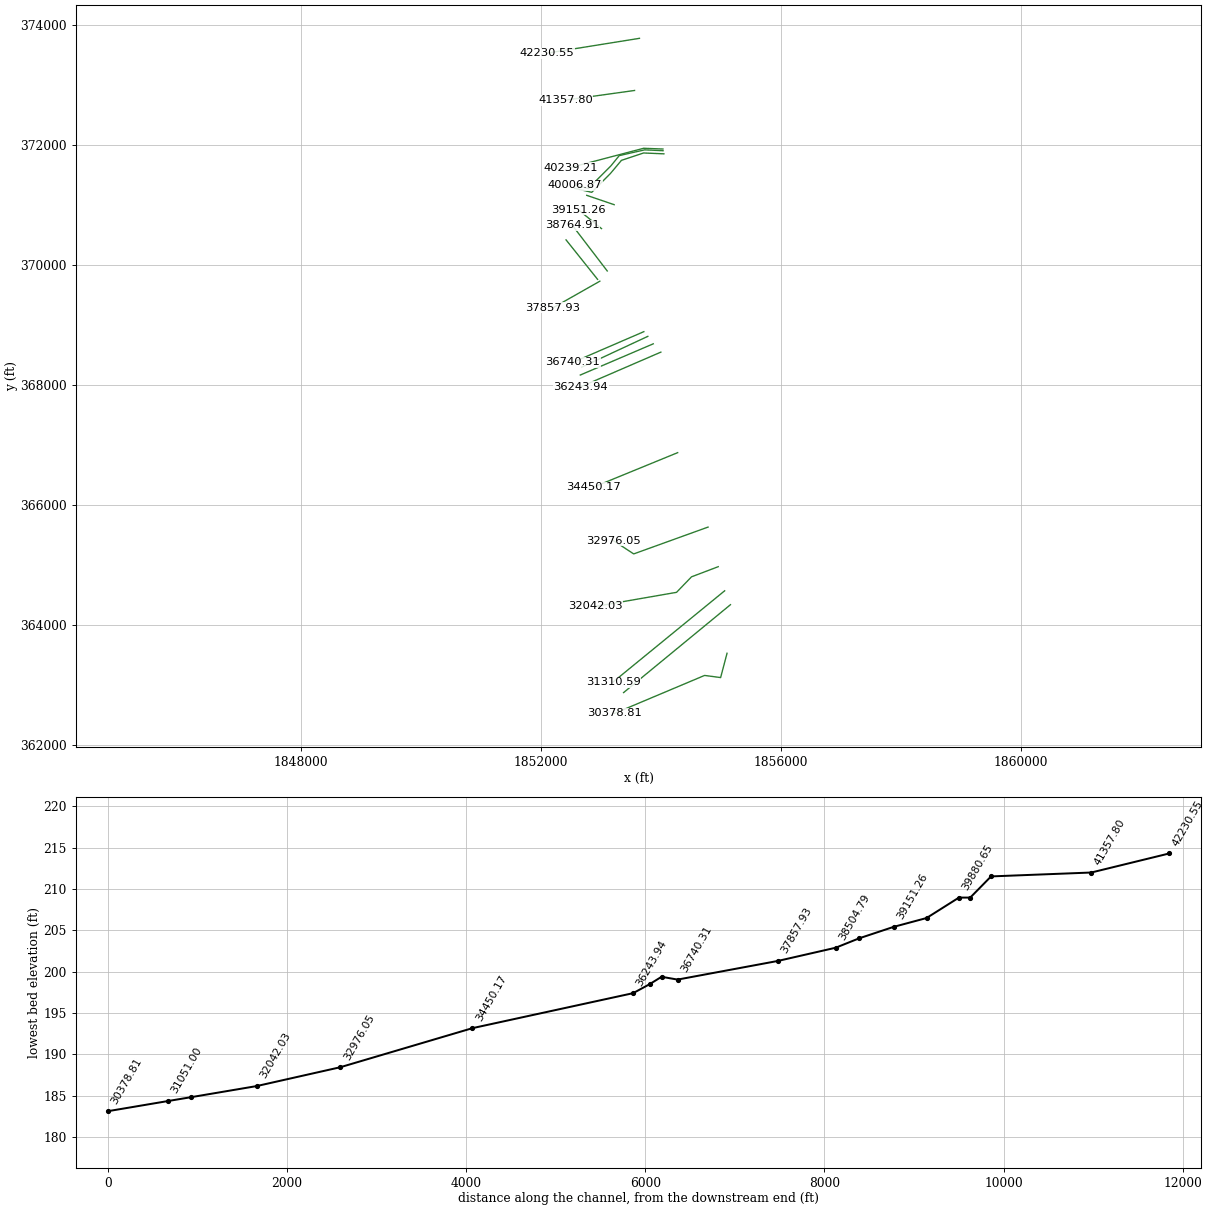
HEC-RAS study bridge.prj: Bridge Creek to Leith Creek

--- bridge.g02 (geometry) --- (continued)

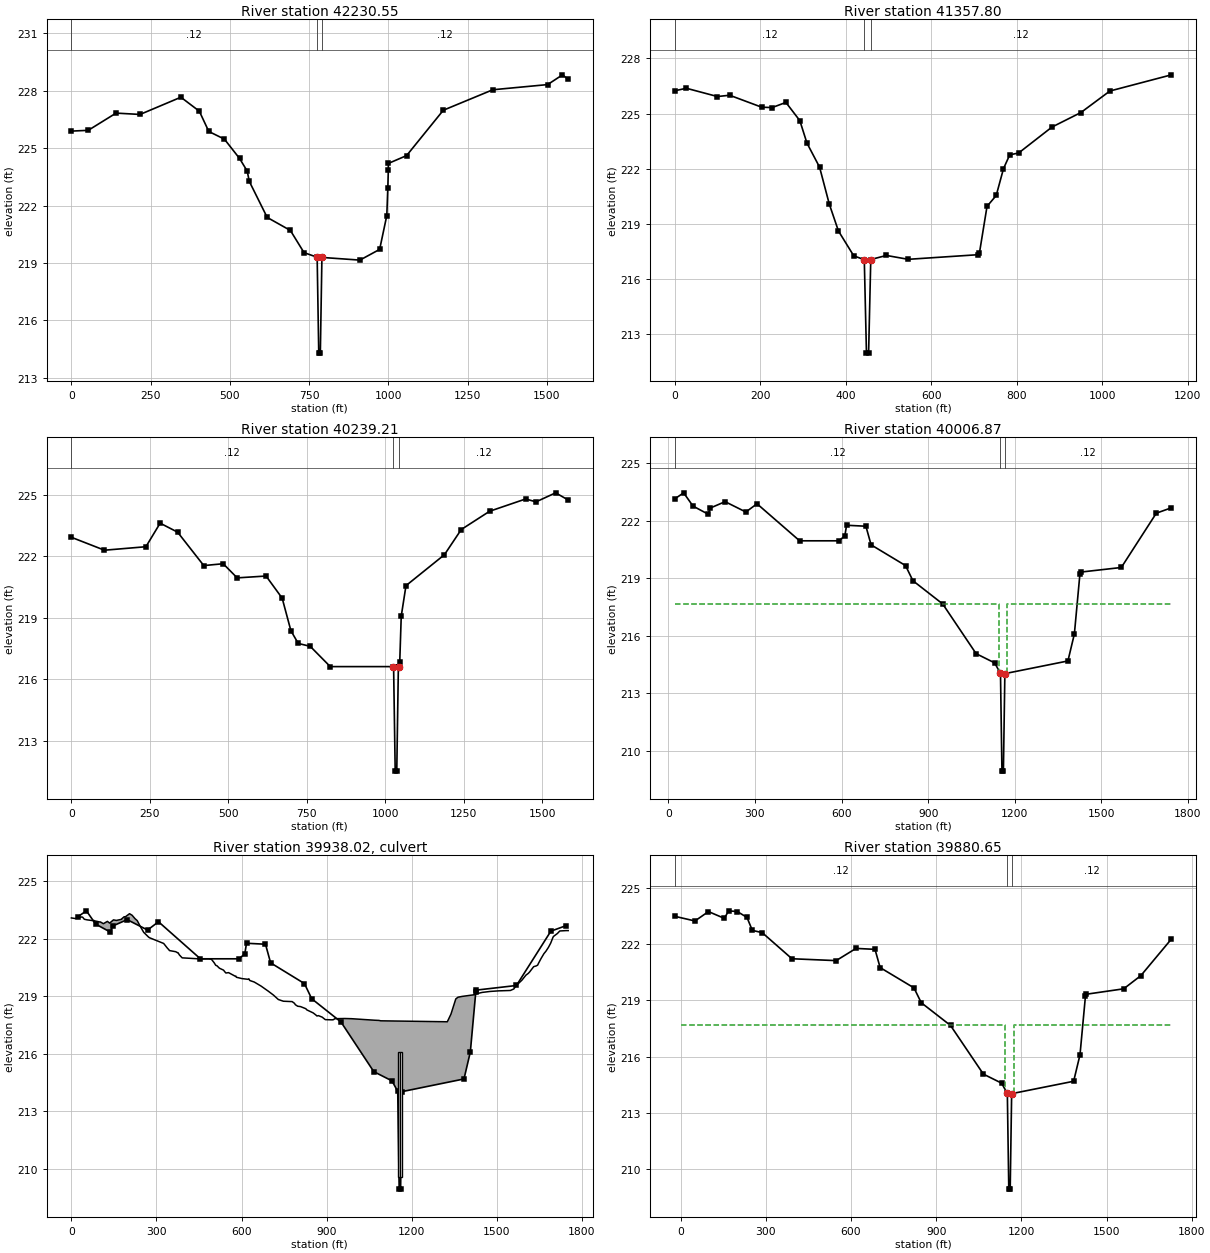
Type RM Length L Ch R = 1 ,42230.55,843.07,872.74,863.22
XS GIS Cut Line= 2
     1853646.501      373772.131     1852099.016      373524.012
#Sta/Elev= 30
       0  225.89   53.14  225.93  140.93  226.83   216.6  226.76  345.42  227.66
  403.59  226.93  433.49  225.87  482.71  225.47  530.56  224.46  554.73   223.8
  561.03  223.27  617.71  221.38  690.83   220.7  733.93  219.54  775.33   219.3
  780.34  214.29  785.34  214.29  790.34  219.29  910.16  219.15  972.44  219.71
  995.02  221.48  998.21  222.91   999.8  223.84   999.8   224.2 1057.39  224.61
 1173.26  226.98 1329.47  228.05 1502.41  228.32 1549.26  228.83 1567.25  228.59
#Mann= 3 , 0 , 0
       0     .12       0  775.33    .055       0  790.34     .12       0
Bank Sta=775.33,790.34
Exp/Cntr=.3,.1

Type RM Length L Ch R = 1 ,41357.80,1032.99,1118.59,1114.4
XS GIS Cut Line= 2
     1853564.847      372902.948     1852413.718      372742.325
#Sta/Elev= 30
       0  226.24   27.45  226.38  100.16  225.93  128.78     226  203.74  225.35
  228.17  225.33  260.39  225.61  292.96  224.62   309.6   223.4  339.17  222.09
  361.79  220.09  383.28  218.62   419.1  217.27  443.76  217.06  448.84  211.98
  453.84  211.98  458.93  217.07  495.52  217.29   546.5  217.08  709.34  217.33
  713.11  217.42   730.9  219.96  752.41  220.55  769.42  222.01  784.02  222.76
  804.82  222.86   882.8  224.27  950.52  225.06 1018.33  226.23 1162.28  227.11
#Mann= 3 , 0 , 0
       0     .12       0  443.76    .055       0  458.93     .12       0
Bank Sta=443.76,458.93
Exp/Cntr=.3,.1

Type RM Length L Ch R = 1 ,40239.21,18.12,232.34,278.27
XS GIS Cut Line= 3
     1854038.469      371927.053     1853715.927      371939.351
     1852497.527      371618.865
#Sta/Elev= 30
       0  222.92  105.49  222.29  237.43  222.46  282.74  223.61  338.42  223.17
  421.74  221.54  483.62  221.63  528.15  220.94  620.16  221.03  671.47  219.95
   699.3  218.36  722.71  217.74   760.8   217.6  824.68  216.61 1025.27  216.61
 1026.44   216.6 1031.53  211.51 1036.53  211.51 1041.62   216.6 1042.79  216.61
 1045.97  216.82 1050.75  219.07 1065.86  220.56 1188.33  222.07 1242.01   223.3
 1332.21  224.19 1446.92  224.79  1480.2  224.65 1542.62  225.09 1582.62  224.74
#Mann= 3 , 0 , 0
       0     .12       0 1025.27    .055       0 1042.79     .12       0
Bank Sta=1025.27,1042.79
Exp/Cntr=.5,.3

Type RM Length L Ch R = 1 ,40006.87,89.71,126.22,162.8
XS GIS Cut Line= 6
     1854039.475      371898.874     1853734.126      371913.077
     1853308.999      371817.069     1853172.836      371648.928
     1852796.777      371271.608     1852571.908      371318.948
#Sta/Elev= 30
   21.69  223.13   53.01  223.45   85.43  222.76  137.51  222.34  145.69  222.66
   196.7  222.99  268.58  222.45  307.14  222.88  454.85  220.95  591.15  220.95
  611.45  221.21  617.44  221.76  684.37  221.71   702.4  220.74  821.66  219.66
  847.29  218.87  950.42  217.66 1066.23  215.07 1130.35  214.59 1150.62  214.04
 1155.71  208.95 1160.71  208.95 1165.79  214.03 1384.23  214.69 1406.62   216.1
 1425.73  219.21 1428.18  219.32 1569.17  219.56 1690.45  222.39 1742.78  222.67
#Mann= 3 , 0 , 0
   21.69     .12       0 1150.62    .055       0 1165.79     .12       0
#XS Ineff= 2 , 0
       0 1143.96  217.67 1172.46       0  217.67
Bank Sta=1150.62,1165.79
Exp/Cntr=.5,.3

Type RM Length L Ch R = 2 ,39938.02,,,
BEGIN DESCRIPTION:
SR 1105 (NCDOT 82 2027)
END DESCRIPTION:
Bridge Culvert--1,0,-1,-1, 0
Deck Dist Width WeirC Skew NumUp NumDn MinLoCord MaxHiCord MaxSubmerge Is_Ogee
54.85,28,2.6,0,132,132,217.67,,.95,0,0,0,,
       0      13   35.15   39.53   45.67   55.42   75.37   79.49   80.94   99.83
  102.39  112.79  126.97  134.92  148.43  158.43  175.57  177.25  178.15  185.89
  190.41  204.97  214.02  224.45   232.2  242.82  254.98  271.55  275.04  325.38
  338.59  338.78  343.01  343.98  345.39  367.94  373.84  375.93  380.88  387.67
   390.6  459.37   482.6  493.55  503.59  509.02  513.07  522.03  536.45  540.02
  544.73  554.14  577.98  579.89  581.45  592.07  601.27  623.64  625.74  626.78
   627.6  628.97  644.78  668.66  694.53  712.44  729.57  747.44  778.37  786.61
  789.56  797.79  807.96  826.53  830.04  849.65  852.64  863.04  865.57  870.97
  884.35  893.22  894.29  895.96  919.71   924.3  928.42  963.46  987.86 1035.63
 1069.69 1084.52 1090.65  1325.4  1338.3 1355.27 1363.18 1377.11 1400.99 1421.44
 1422.18 1448.76 1476.62 1506.47 1529.74 1536.45 1547.74 1559.93  1567.4  1580.4
 1588.59 1602.69    1608 1610.79 1615.36  1626.3 1629.82 1638.82 1643.92 1646.67
  1655.7 1661.26 1666.11 1672.84 1682.09 1690.01 1697.92 1700.07 1713.64 1721.96
 1744.26 1751.62
  223.08  223.05  223.13  223.12  223.01  222.98  222.94  222.95  222.93  222.87
  222.87  222.78   222.9  222.81  222.98  222.95     223  223.01  223.04  223.14
  223.14   223.3  223.22  223.04  222.94  222.64  222.33  222.09  222.05  221.75
   221.5   221.5  221.43  221.42  221.38  221.32  221.27  221.27  221.15  221.05
     221  220.94  220.95  220.93  220.74  220.61  220.59  220.46  220.36  220.29
  220.21  220.23  220.04  220.05  219.99  219.95  219.92  219.88  219.91  219.87
  219.86  219.82  219.74  219.53  219.26  219.06  218.83  218.74  218.72  218.63
  218.56  218.48  218.46  218.35  218.29  218.15  218.13  218.01  217.97  217.99
  217.91   217.8  217.79  217.78  217.77  217.78  217.83  217.84  217.83  217.78
  217.75  217.74  217.72  217.67  218.07  218.86  218.95  218.99  219.04  219.08
  219.11   219.2  219.25  219.28  219.29  219.29   219.3  219.38  219.54  219.72
  219.84   220.1  220.16  220.19  220.26  220.47  220.54  220.58  220.62  220.71
  220.96   221.1  221.22  221.34  221.55  221.77  222.07  222.12  222.27   222.4
  222.42  222.42
                                                                                
                                                                                
                                                                                
                                                                                
                                                                                
                                                                                
                                                                                
                                                                                
                                                                                
                                                                                
                                                                                
                                                                                
                                                                                
                
       0      13   35.15   39.53   45.67   55.42   75.37   79.49   80.94   99.83
  102.39  112.79  126.97  134.92  148.43  158.43  175.57  177.25  178.15  185.89
  190.41  204.97  214.02  224.45   232.2  242.82  254.98  271.55  275.04  325.38
  338.59  338.78  343.01  343.98  345.39  367.94  373.84  375.93  380.88  387.67
   390.6  459.37   482.6  493.55  503.59  509.02  513.07  522.03  536.45  540.02
  544.73  554.14  577.98  579.89  581.45  592.07  601.27  623.64  625.74  626.78
   627.6  628.97  644.78  668.66  694.53  712.44  729.57  747.44  778.37  786.61
  789.56  797.79  807.96  826.53  830.04  849.65  852.64  863.04  865.57  870.97
  884.35  893.22  894.29  895.96  919.71   924.3  928.42  963.46  987.86 1035.63
 1069.69 1084.52 1090.65  1325.4  1338.3 1355.27 1363.18 1377.11 1400.99 1421.44
 1422.18 1448.76 1476.62 1506.47 1529.74 1536.45 1547.74 1559.93  1567.4  1580.4
 1588.59 1602.69    1608 1610.79 1615.36  1626.3 1629.82 1638.82 1643.92 1646.67
  1655.7 1661.26 1666.11 1672.84 1682.09 1690.01 1697.92 1700.07 1713.64 1721.96
 1744.26 1751.62
  223.08  223.05  223.13  223.12  223.01  222.98  222.94  222.95  222.93  222.87
  222.87  222.78   222.9  222.81  222.98  222.95     223  223.01  223.04  223.14
  223.14   223.3  223.22  223.04  222.94  222.64  222.33  222.09  222.05  221.75
   221.5   221.5  221.43  221.42  221.38  221.32  221.27  221.27  221.15  221.05
     221  220.94  220.95  220.93  220.74  220.61  220.59  220.46  220.36  220.29
  220.21  220.23  220.04  220.05  219.99  219.95  219.92  219.88  219.91  219.87
  219.86  219.82  219.74  219.53  219.26  219.06  218.83  218.74  218.72  218.63
  218.56  218.48  218.46  218.35  218.29  218.15  218.13  218.01  217.97  217.99
  217.91   217.8  217.79  217.78  217.77  217.78  217.83  217.84  217.83  217.78
  217.75  217.74  217.72  217.67  218.07  218.86  218.95  218.99  219.04  219.08
  219.11   219.2  219.25  219.28  219.29  219.29   219.3  219.38  219.54  219.72
  219.84   220.1  220.16  220.19  220.26  220.47  220.54  220.58  220.62  220.71
  220.96   221.1  221.22  221.34  221.55  221.77  222.07  222.12  222.27   222.4
  222.42  222.42
                                                                                
                                                                                
                                                                                
                                                                                
                                                                                
                                                                                
                                                                                
                                                                                
                                                                                
                                                                                
                                                                                
                                                                                
                                                                                
                
Multiple Barrel Culv=2,6.5,8,28,.012,.4,1,8,1,209.58,209.56, 2,Culvert #1  , 0 ,54.85
 1153.96 1153.96 1162.46 1162.46
BC Design=,, 0 ,, 0 ,,,,,,

Type RM Length L Ch R = 1 ,39880.65,777.1,361.35,219.26
XS GIS Cut Line= 6
     1854053.677      371846.799      1853715.19      371861.002
     1853345.931      371737.915     1853161.302       371517.78
     1852851.219       371205.33     1852564.806      371271.608
#Sta/Elev= 30
  -21.69  223.47   49.99  223.22   97.54  223.72  153.42  223.36   168.9  223.76
  199.29  223.72  233.33  223.41  252.11  222.72  286.83   222.6  391.75  221.21
  547.48  221.11  617.44  221.76  684.37  221.71   702.4  220.74  821.66  219.66
  847.29  218.87  950.42  217.66 1066.23  215.07 1130.35  214.59 1150.62  214.04
 1155.71  208.95 1160.71  208.95 1165.79  214.03 1384.23  214.69 1406.62   216.1
 1425.73  219.21 1428.18  219.32 1560.57  219.61  1620.9  220.31 1728.72  222.26
#Mann= 3 , 0 , 0
  -21.69     .12       0 1150.62    .055       0 1165.79     .12       0
#XS Ineff= 2 , 0
       0 1143.96  217.67 1172.46       0  217.67
Bank Sta=1150.62,1165.79
Exp/Cntr=.5,.3

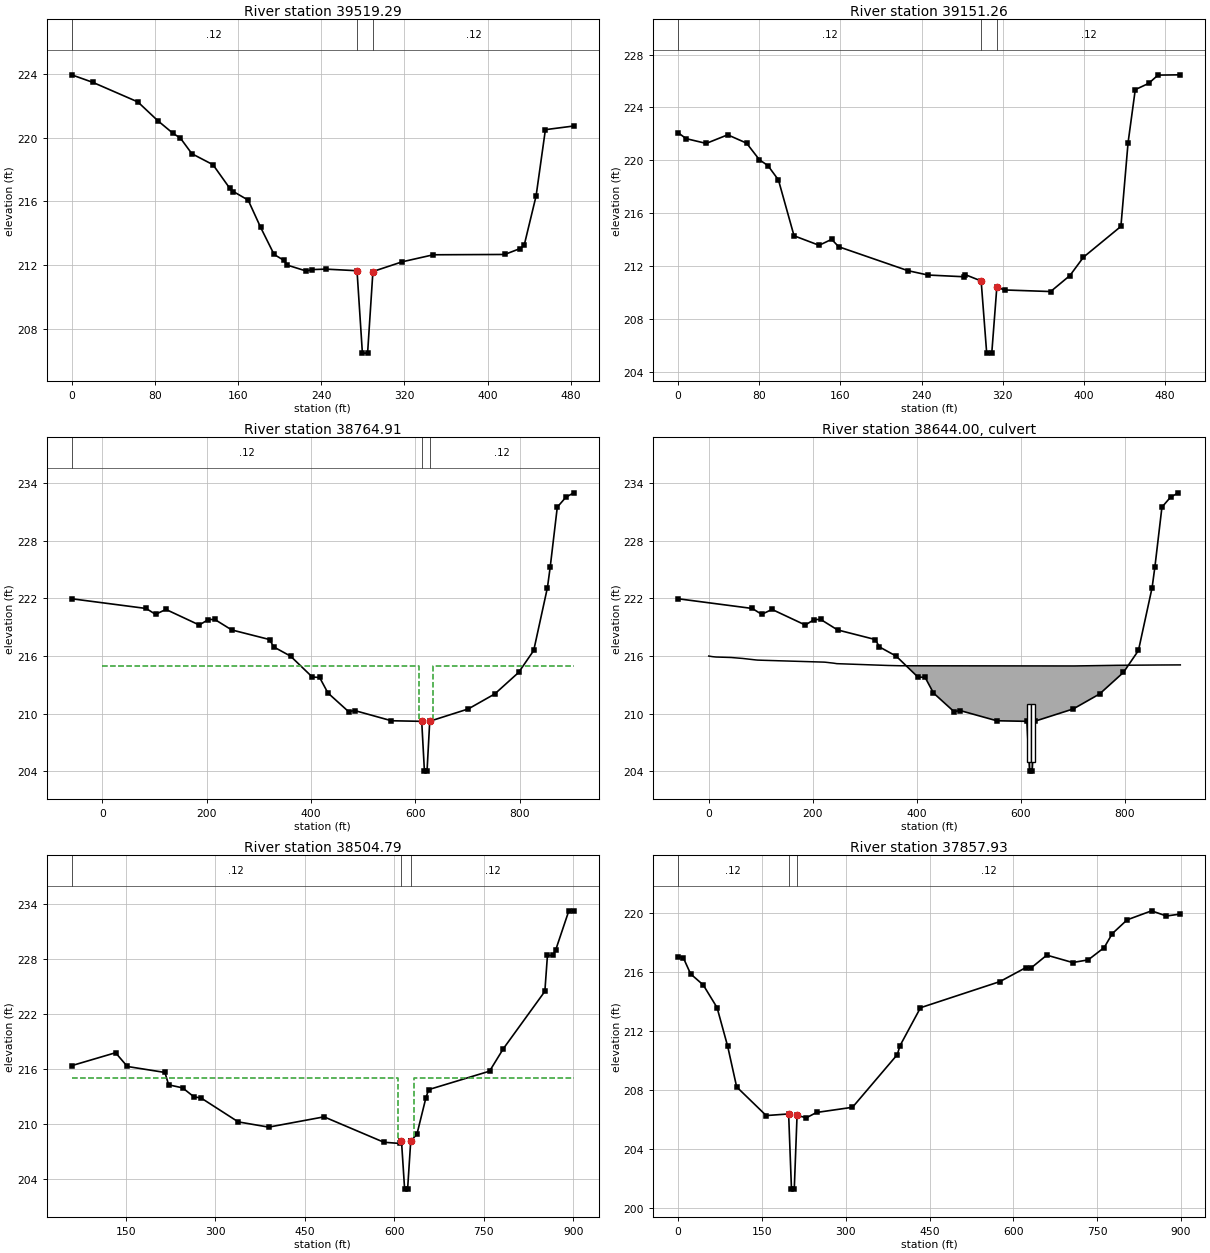
Type RM Length L Ch R = 1 ,39519.29,380.01,368.03,315.83
XS GIS Cut Line= 2
     1853224.713      370999.025     1852767.625      371154.851
#Sta/Elev= 30
       0  223.94   20.29  223.47   63.65  222.24   82.89  221.06   97.44  220.27
  104.57  219.97  115.62  218.99  135.93   218.3  152.17  216.81  155.41  216.62
  169.74  216.08  181.65  214.38  194.68  212.67  204.14   212.3  207.47     212
  225.61  211.63  230.85  211.72  244.28  211.75  274.42  211.65  279.59  206.48
  284.59  206.48  289.71   211.6  317.91  212.21  347.76  212.65  416.46  212.67
  431.21  213.04  435.14  213.24  446.62  216.34  455.57   220.5  482.92  220.73
#Mann= 3 , 0 , 0
       0     .12       0  274.42    .055       0  289.71     .12       0
Bank Sta=274.42,289.71
Exp/Cntr=.3,.1

Type RM Length L Ch R = 1 ,39151.26,402.78,386.35,313.21
XS GIS Cut Line= 2
     1853013.483      370600.804     1852629.113      370912.455
#Sta/Elev= 30
       0  222.09    7.91  221.64   27.69  221.28   48.87  221.93   67.46   221.3
   80.14  220.04   88.48   219.6   98.83  218.52  114.22  214.29  138.91  213.57
   151.3  214.02  158.22  213.46  226.44  211.65  246.13  211.32  281.45  211.19
  282.59  211.36   298.6  210.87  304.06  205.41  309.06  205.41  314.05   210.4
  321.74  210.19  367.08  210.07  386.05  211.28  399.41  212.67  436.31     215
  443.36  221.33  450.46  225.35  463.58  225.82  472.89  226.45  494.84  226.47
#Mann= 3 , 0 , 0
       0     .12       0   298.6    .055       0  314.05     .12       0
Bank Sta=298.6,314.05
Exp/Cntr=.5,.3

Type RM Length L Ch R = 1 ,38764.91,329.77,260.12,282.99
XS GIS Cut Line= 2
     1853109.227      369893.988     1852524.567      370658.543
#Sta/Elev= 30
  -58.88  221.95   83.86  220.94  101.87  220.33  121.81  220.84   185.7  219.22
  203.16  219.79   215.4   219.8  247.78  218.71  320.36  217.71  328.42  216.94
  360.71  215.98  402.28  213.81   416.4  213.76   432.3  212.15  471.85  210.21
  483.71  210.32   554.1  209.26  612.05   209.2  617.23  204.02  622.23  204.02
  627.42  209.21  701.32  210.49  752.07  212.05  797.84  214.29  826.69  216.57
  852.98  223.11  858.36  225.27  871.89  231.48  888.45  232.52   903.6  232.97
#Mann= 3 , 0 , 0
  -58.88     .12       0  612.05    .055       0  627.42     .12       0
#XS Ineff= 2 , 0
       0  606.48  214.96  632.98       0  214.96
Bank Sta=612.05,627.42
Exp/Cntr=.5,.3

Type RM Length L Ch R = 2 ,38644.00,,,
BEGIN DESCRIPTION:
US 74 (NCDOT # 37)
END DESCRIPTION:
Bridge Culvert--1,0,-1,-1, 0
Deck Dist Width WeirC Skew NumUp NumDn MinLoCord MaxHiCord MaxSubmerge Is_Ogee
20.08,201.67,2.6,0,19,19,214.96,,.95,0,0,0,,
       0    6.87   14.03   43.05    65.6   90.01      94  110.61  221.14  224.26
  240.46  246.24  344.94  369.84  373.09  703.02   786.8   867.2  907.23
  215.99  215.93  215.89  215.84  215.74  215.59  215.57  215.54  215.36  215.35
  215.25   215.2  215.01  214.98  214.98  214.96  215.03  215.06  215.07
                                                                                
                                                                        
       0    6.87   14.03   43.05    65.6   90.01      94  110.61  221.14  224.26
  240.46  246.24  344.94  369.84  373.09  703.02   786.8   867.2  907.23
  215.99  215.93  215.89  215.84  215.74  215.59  215.57  215.54  215.36  215.35
  215.25   215.2  215.01  214.98  214.98  214.96  215.03  215.06  215.07
                                                                                
                                                                        
Multiple Barrel Culv=2,6,7,201.67,.012,.4,1,8,1,204.97,204.95, 2,Culvert #1  , 0 ,20.08
  615.98  615.98  623.48  623.48
BC Design=,, 0 ,, 0 ,,,,,,

Type RM Length L Ch R = 1 ,38504.79,392.17,646.86,789.76
XS GIS Cut Line= 2
     1852948.268      369754.332     1852422.784      370412.371
#Sta/Elev= 30
   58.88  216.35  132.51  217.76  152.26  216.26  215.27  215.61   221.5  214.26
  244.92  213.93  263.95  212.95  275.81  212.83  338.24  210.22  389.32  209.65
  482.12  210.77  582.44     208  609.42  207.87   611.3  208.14  611.97  208.15
  617.23  202.89  622.23  202.89  627.46  208.12  628.15  208.13  638.06  208.93
  653.02  212.87   657.6  213.74  759.67  215.75  782.77   218.2  852.38  224.45
  856.74  228.37  866.01  228.36  870.54  228.96  892.54  233.22  900.99  233.23
#Mann= 3 , 0 , 0
   58.88     .12       0   611.3    .055       0  628.15     .12       0
#XS Ineff= 2 , 0
       0  606.48  214.96  632.98       0  214.96
Bank Sta=611.3,628.15
Exp/Cntr=.5,.3

Type RM Length L Ch R = 1 ,37857.93,1084.85,1117.61,1053.47
XS GIS Cut Line= 2
      1852986.14      369723.561     1852204.274      369280.086
#Sta/Elev= 30
       0  217.03    9.35  216.95   22.35  215.86   45.01  215.11   69.69  213.58
    88.7  210.96  104.78  208.21  157.69  206.27  197.81  206.38   202.9  201.29
   207.9  201.29  212.89  206.28  229.56  206.12   247.8  206.48  312.13  206.83
   392.4   210.4  396.88  210.98  433.81  213.57  576.01  215.34  622.53  216.29
  631.67  216.26  659.93  217.13  706.16  216.63  734.06  216.81  762.59  217.64
  777.21  218.59  803.71  219.52  847.46  220.13   873.9  219.78  898.88  219.91
#Mann= 3 , 0 , 0
       0     .12       0  197.81    .055       0  212.89     .12       0
Bank Sta=197.81,212.89
Exp/Cntr=.3,.1

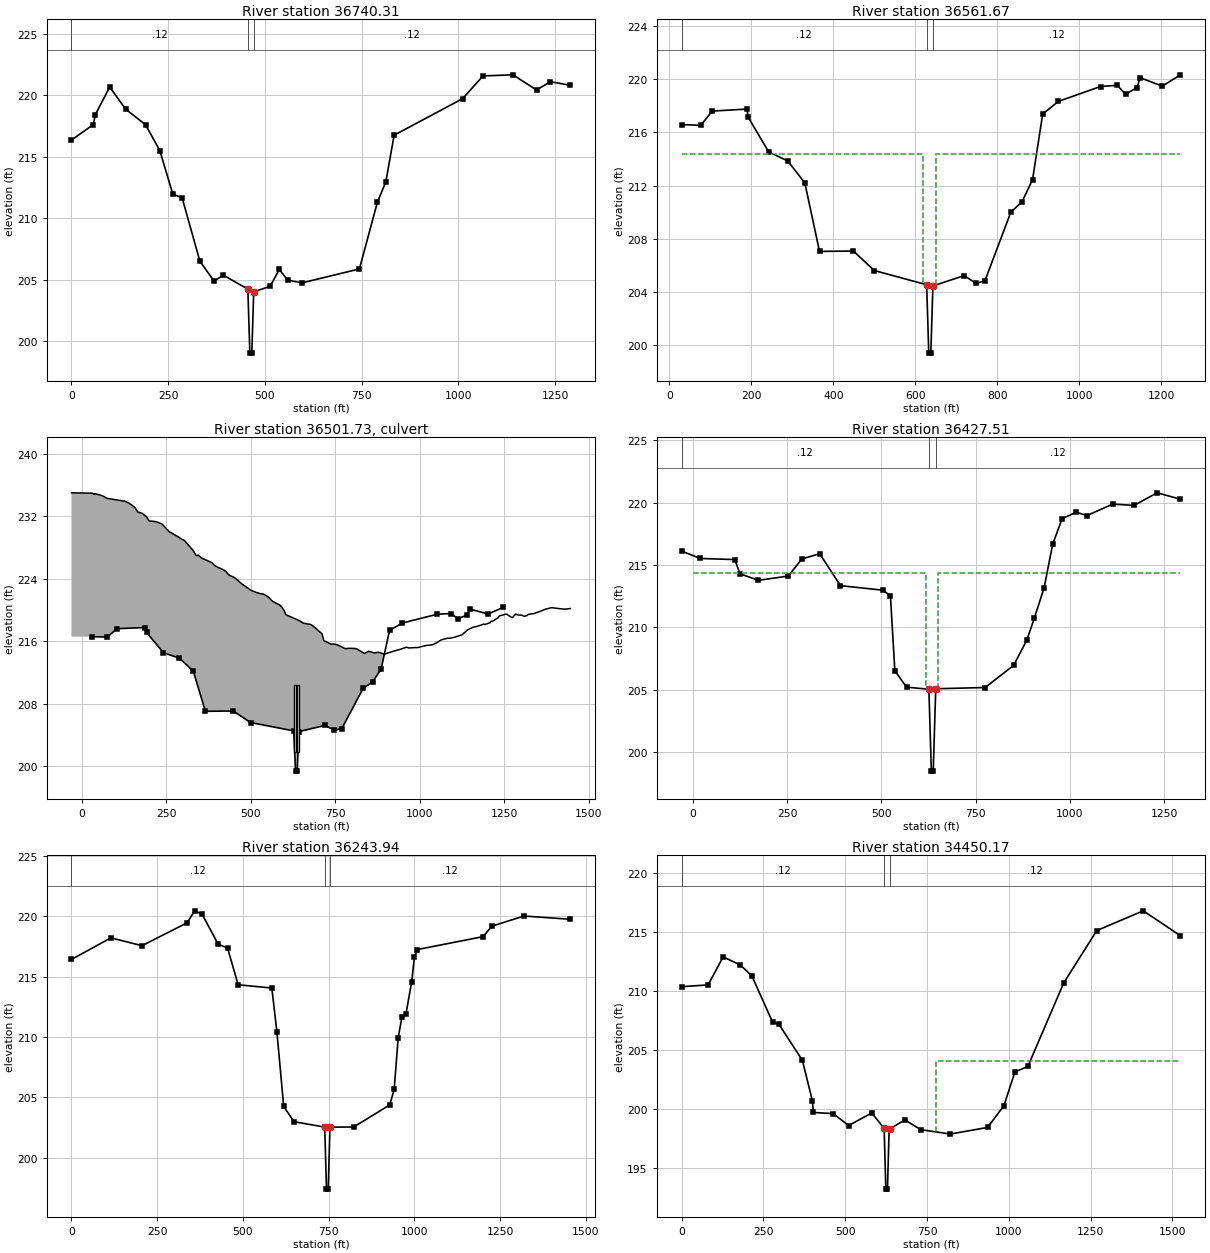
Type RM Length L Ch R = 1 ,36740.31,133.66,178.64,124.38
XS GIS Cut Line= 2
     1853719.512      368882.335     1852535.732      368370.943
#Sta/Elev= 30
       0  216.38   56.13  217.62   61.85  218.45   98.82  220.69  139.91  218.89
  191.45  217.62  228.55   215.5  261.98  211.97  285.91  211.68  331.91  206.52
  368.47   204.9  392.64  205.38  455.87  204.25  461.08  199.04  466.08  199.04
  471.07  204.03   513.5  204.47   537.3  205.85  558.84  204.97  596.59  204.76
  744.29  205.89   790.8  211.32  812.62  212.98     834  216.77 1011.02  219.74
 1063.67  221.59 1141.14  221.68 1202.04  220.45 1238.07  221.12 1289.52  220.83
#Mann= 3 , 0 , 0
       0     .12       0  455.87    .055       0  471.07     .12       0
Bank Sta=455.87,471.07
Exp/Cntr=.5,.3

Type RM Length L Ch R = 1 ,36561.67,140.83,134.16,135.72
XS GIS Cut Line= 2
     1853785.842       368804.01     1852682.447      368290.513
#Sta/Elev= 30
    29.7  216.59   76.59  216.54  104.24  217.61  189.02  217.76  192.39  217.13
  242.25  214.53  288.43  213.86   330.3   212.2  366.14  207.04  448.74  207.07
  499.79   205.6  627.53  204.53  632.68  199.38  637.68  199.38  642.74  204.44
  719.09  205.22  747.85  204.63  769.69  204.83  832.83  209.99  860.34  210.79
  885.85  212.45   910.6  217.39  948.92  218.34 1051.67  219.46 1092.25  219.55
 1112.85  218.89 1140.62  219.37 1148.14  220.12  1202.4  219.49 1246.73  220.34
#Mann= 3 , 0 , 0
    29.7     .12       0  627.53    .055       0  642.74     .12       0
#XS Ineff= 2 , 0
       0  619.03  214.35  651.33       0  214.35
Bank Sta=627.53,642.74
Exp/Cntr=.5,.3

Type RM Length L Ch R = 2 ,36501.73,,,
BEGIN DESCRIPTION:
SR 1108 (NCDOT 82 2028)
END DESCRIPTION:
Bridge Culvert--1,0,-1,-1, 0
Deck Dist Width WeirC Skew NumUp NumDn MinLoCord MaxHiCord MaxSubmerge Is_Ogee
36.44,47,2.6,0,168,168,214.35,,.95,0,0,0,,
   -29.7   31.84   37.65   38.41   58.24    65.3   74.73   97.11  126.84   126.9
  139.89  148.87  158.82  166.61  180.25  187.39  189.75  190.69  200.27  206.32
  219.06  224.17  236.22  240.08  258.11  259.51  262.06  285.33  296.01  304.74
  308.68  314.42  325.56  327.97  339.43  345.16  355.18  385.12  393.18  404.92
  409.08  421.14  427.47  432.57   438.7  448.53  454.15  464.11  470.47   474.4
  490.99     497  500.37   516.5   528.3  537.05  538.76  539.83  553.14  558.78
  564.51  572.83  586.68  591.69  599.33  604.25  606.03  634.48  645.07  653.57
  658.74  668.68  677.71  682.47  695.23  700.81  711.05  716.32   736.9  745.64
     755  766.04  779.62  792.18  810.06  811.99  814.58  836.09  842.57  848.85
  855.65  866.23  877.43  878.82  885.45  895.18   896.6  898.52  917.93  918.67
  927.99  940.92  942.36  943.39  960.74   968.3  973.38  986.65  993.85  999.33
 1005.16 1019.55 1024.46 1030.51 1038.09 1041.06 1049.89 1058.66 1060.94 1063.71
 1082.28 1087.81 1104.26 1113.56 1125.39 1138.01  1139.4 1140.25  1155.9 1165.67
 1166.52 1185.37 1187.83 1193.28 1207.38 1211.02 1218.11 1231.75 1235.65 1253.91
 1257.82 1260.51 1272.68 1274.46 1283.65 1290.34 1301.75 1309.05 1317.51 1319.13
 1321.03  1327.2 1335.55 1339.49 1358.42  1359.4 1360.88 1372.89 1376.88 1388.61
 1388.95 1390.31 1411.82 1422.42 1428.37 1431.76 1439.83 1445.26
     235  234.96  234.79   234.9  234.68  234.54   234.3  234.14  233.93  233.95
  233.69  233.43  233.06  232.54  232.36  232.08  232.01  232.01  231.39  231.38
  231.31  231.25  231.05  230.92  230.07  230.01  229.96  229.38  229.07  228.89
  228.68   228.4  227.83  227.75  226.95  227.03  226.65  226.07  225.71  225.42
  225.36  225.11  224.92  224.62  224.41  224.23  224.09  223.72  223.47  223.33
  222.83  222.63  222.55  222.25  222.11  222.04  222.04     222  221.64  221.36
  221.12  220.93  220.62  220.42   219.9   219.4  219.37  218.82  218.62  218.38
  218.29  218.21  218.15  218.01  217.57  217.34  216.96  216.09  215.65  215.64
  215.56  215.35  215.06   215.1  215.08  215.05     215  214.45  214.56  214.72
  214.64  214.51   214.6  214.58   214.5  214.35  214.37  214.41  214.67  214.69
   214.8  214.94  214.96  214.98  215.24  215.14  215.16  215.19   215.2  215.24
  215.32  215.46  215.49  215.51  215.56  215.61  215.81  216.04  216.09  216.18
  216.39  216.38  216.53  216.67  216.83  217.34  217.39  217.43  217.77  217.88
  217.87  218.13   218.2  218.16  218.37  218.54  218.63  219.02  219.25  219.46
  219.46  219.37  219.02  219.05  219.49  219.36  219.34  219.19   219.3   219.4
  219.43  219.49  219.53  219.58  219.87  219.89  219.91  220.13  220.16   220.3
   220.3   220.3  220.18  220.13  220.11  220.12  220.17  220.19
                                                                                
                                                                                
                                                                                
                                                                                
                                                                                
                                                                                
                                                                                
                                                                                
                                                                                
                                                                                
                                                                                
                                                                                
                                                                                
                                                                                
                                                                                
                                                                                
                                                                
   -29.7   31.84   37.65   38.41   58.24    65.3   74.73   97.11  126.84   126.9
  139.89  148.87  158.82  166.61  180.25  187.39  189.75  190.69  200.27  206.32
  219.06  224.17  236.22  240.08  258.11  259.51  262.06  285.33  296.01  304.74
  308.68  314.42  325.56  327.97  339.43  345.16  355.18  385.12  393.18  404.92
  409.08  421.14  427.47  432.57   438.7  448.53  454.15  464.11  470.47   474.4
  490.99     497  500.37   516.5   528.3  537.05  538.76  539.83  553.14  558.78
  564.51  572.83  586.68  591.69  599.33  604.25  606.03  634.48  645.07  653.57
  658.74  668.68  677.71  682.47  695.23  700.81  711.05  716.32   736.9  745.64
     755  766.04  779.62  792.18  810.06  811.99  814.58  836.09  842.57  848.85
  855.65  866.23  877.43  878.82  885.45  895.18   896.6  898.52  917.93  918.67
  927.99  940.92  942.36  943.39  960.74   968.3  973.38  986.65  993.85  999.33
 1005.16 1019.55 1024.46 1030.51 1038.09 1041.06 1049.89 1058.66 1060.94 1063.71
 1082.28 1087.81 1104.26 1113.56 1125.39 1138.01  1139.4 1140.25  1155.9 1165.67
 1166.52 1185.37 1187.83 1193.28 1207.38 1211.02 1218.11 1231.75 1235.65 1253.91
 1257.82 1260.51 1272.68 1274.46 1283.65 1290.34 1301.75 1309.05 1317.51 1319.13
 1321.03  1327.2 1335.55 1339.49 1358.42  1359.4 1360.88 1372.89 1376.88 1388.61
 1388.95 1390.31 1411.82 1422.42 1428.37 1431.76 1439.83 1445.26
     235  234.96  234.79   234.9  234.68  234.54   234.3  234.14  233.93  233.95
  233.69  233.43  233.06  232.54  232.36  232.08  232.01  232.01  231.39  231.38
  231.31  231.25  231.05  230.92  230.07  230.01  229.96  229.38  229.07  228.89
  228.68   228.4  227.83  227.75  226.95  227.03  226.65  226.07  225.71  225.42
  225.36  225.11  224.92  224.62  224.41  224.23  224.09  223.72  223.47  223.33
  222.83  222.63  222.55  222.25  222.11  222.04  222.04     222  221.64  221.36
  221.12  220.93  220.62  220.42   219.9   219.4  219.37  218.82  218.62  218.38
  218.29  218.21  218.15  218.01  217.57  217.34  216.96  216.09  215.65  215.64
  215.56  215.35  215.06   215.1  215.08  215.05     215  214.45  214.56  214.72
  214.64  214.51   214.6  214.58   214.5  214.35  214.37  214.41  214.67  214.69
   214.8  214.94  214.96  214.98  215.24  215.14  215.16  215.19   215.2  215.24
  215.32  215.46  215.49  215.51  215.56  215.61  215.81  216.04  216.09  216.18
  216.39  216.38  216.53  216.67  216.83  217.34  217.39  217.43  217.77  217.88
  217.87  218.13   218.2  218.16  218.37  218.54  218.63  219.02  219.25  219.46
  219.46  219.37  219.02  219.05  219.49  219.36  219.34  219.19   219.3   219.4
  219.43  219.49  219.53  219.58  219.87  219.89  219.91  220.13  220.16   220.3
   220.3   220.3  220.18  220.13  220.11  220.12  220.17  220.19
                                                                                
                                                                                
                                                                                
                                                                                
                                                                                
                                                                                
                                                                                
                                                                                
                                                                                
                                                                                
                                                                                
                                                                                
                                                                                
                                                                                
                                                                                
                                                                                
                                                                
Multiple Barrel Culv=2,8.6,6,47,.012,.4,1,8,1,201.86,201.84, 2,Culvert #1  , 0 ,36.44
  630.63  630.63  639.73  639.73
BC Design=,, 0 ,, 0 ,,,,,,

Type RM Length L Ch R = 1 ,36427.51,180.7,183.57,182.86
XS GIS Cut Line= 2
     1853876.459      368679.634     1852659.969      368159.226
#Sta/Elev= 30
   -29.7  216.11   19.97  215.52   111.5  215.43  125.09  214.29  174.09  213.77
  253.11  214.11  289.23  215.48  336.53   215.9  391.68  213.34  503.83  212.98
  524.11  212.53  535.83  206.53  566.78  205.21  626.12  205.04  632.68  198.48
  637.68  198.48  644.28  205.08  775.47  205.18  851.07  206.96  886.07  208.99
  906.15  210.77  931.66  213.16  954.55  216.67  979.32   218.7 1016.79  219.23
 1045.44  218.96 1113.96  219.88 1170.09  219.77 1231.36  220.78 1293.43  220.27
#Mann= 3 , 0 , 0
   -29.7     .12       0  626.12    .055       0  644.28     .12       0
#XS Ineff= 2 , 0
       0  619.03  214.35  651.33       0  214.35
Bank Sta=626.12,644.28
Exp/Cntr=.5,.3

Type RM Length L Ch R = 1 ,36243.94,1684.85,1793.77,1761.67
XS GIS Cut Line= 2
      1854003.62      368541.407     1852668.316      367963.722
#Sta/Elev= 30
       0  216.44  114.99  218.23  205.54  217.58  336.89  219.47  359.42  220.47
  381.03  220.19  427.86   217.7   455.2  217.39     486  214.34  584.29  214.07
  599.18  210.41  618.96  204.25  648.87  202.99  738.56  202.54   743.7   197.4
   748.7   197.4  753.84  202.54  823.23  202.55  928.08  204.38  941.13  205.66
  952.74  209.92  963.72  211.67  975.37   211.9  992.27   214.6 1000.13  216.62
 1008.73  217.26 1200.26  218.33  1226.4   219.2 1319.66  220.04 1454.91  219.77
#Mann= 3 , 0 , 0
       0     .12       0  738.56    .055       0  753.84     .12       0
Bank Sta=738.56,753.84
Exp/Cntr=.3,.1

Type RM Length L Ch R = 1 ,34450.17,1440.37,1474.12,1316
XS GIS Cut Line= 2
     1854282.992      366865.174     1852871.926       366287.49
#Sta/Elev= 30
       0  210.33   80.96  210.48  126.76  212.85  178.38  212.19  214.65  211.25
  278.45   207.3   296.8  207.17  369.07  204.09  399.79  200.65  402.93  199.67
  463.24  199.57  510.68  198.56  581.22  199.63  617.52  198.37     619  198.34
  624.17  193.17  629.17  193.17  634.23  198.23  635.82  198.26  682.05  199.04
  730.98  198.21  821.79  197.84  935.05   198.4  985.11  200.24 1018.67   203.1
  1058.3  203.57 1167.71  210.64 1269.11  215.09 1410.99  216.76 1524.74  214.65
#Mann= 3 , 0 , 0
       0     .12       0  617.52    .055       0  635.82     .12       0
#XS Ineff= 2 , 0
       0                     777       0     204
Bank Sta=617.52,635.82
Exp/Cntr=.3,.1

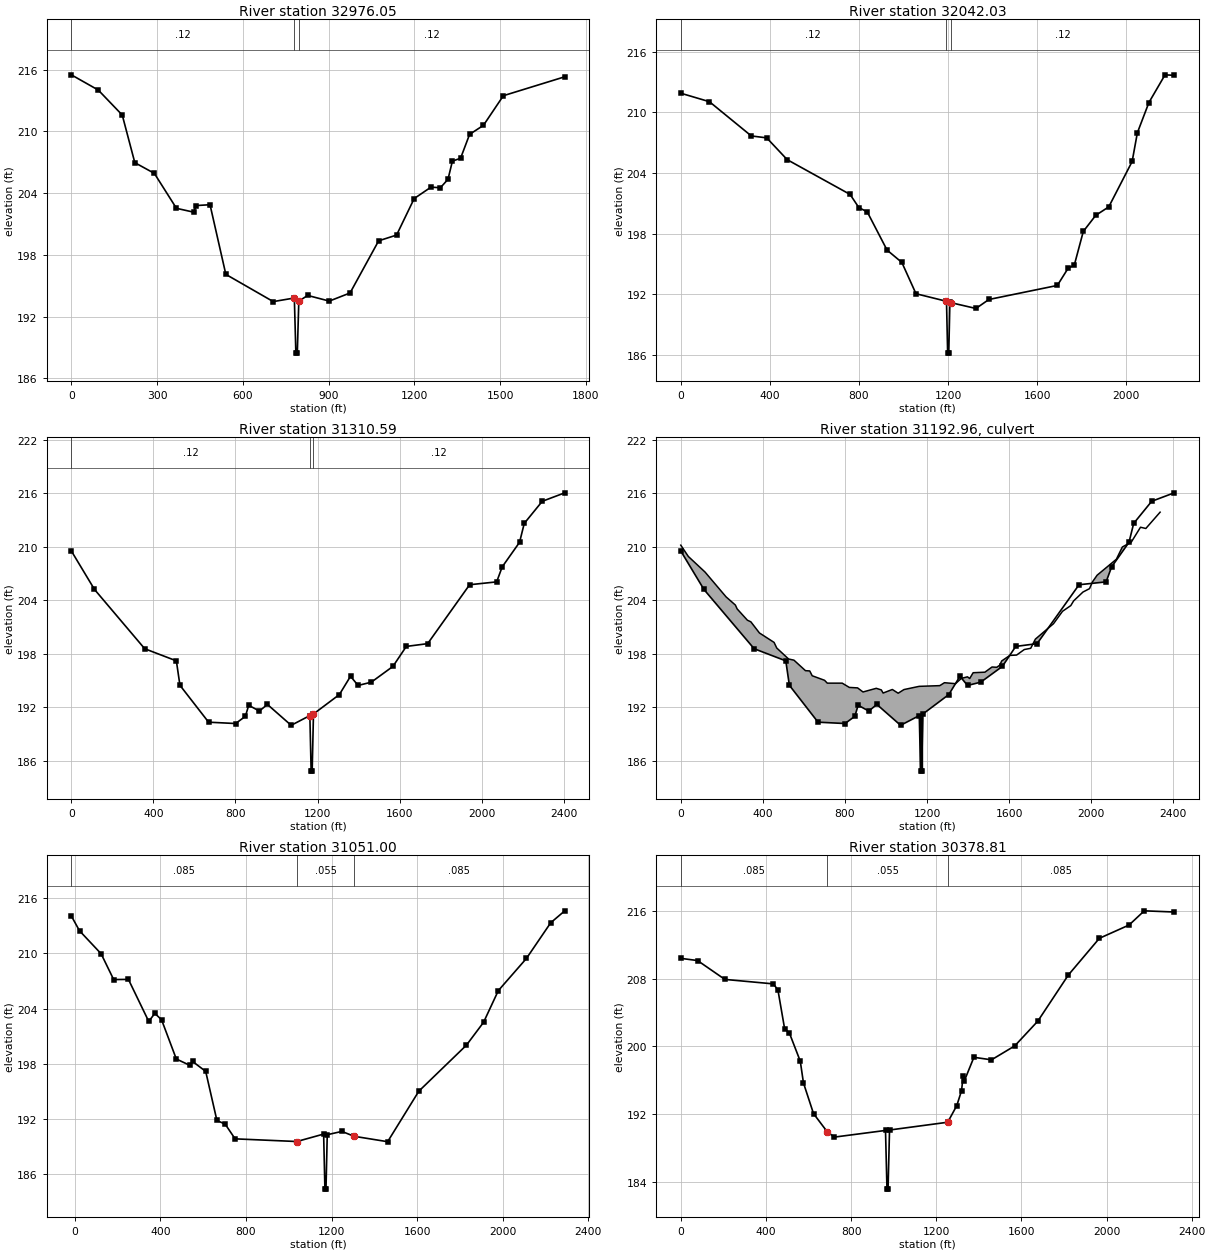
Type RM Length L Ch R = 1 ,32976.05,971.31,934.02,890.73
XS GIS Cut Line= 3
      1854789.65      365624.573     1853550.538      365177.284
     1853208.831      365400.943
#Sta/Elev= 30
       0  215.51   94.21  214.03  178.06   211.6  222.02  206.97  290.27  205.93
  367.65  202.53   427.3  202.16  437.56   202.8  485.08  202.88  540.33  196.11
  706.22  193.46  779.96  193.81  785.32  188.45  790.32  188.45  795.58   193.5
  826.46  194.06  902.25  193.51  974.83   194.3 1074.83  199.37 1137.57  199.93
 1199.12  203.48 1257.94  204.59  1290.7  204.53 1317.37  205.35  1332.8  207.12
 1361.42   207.4 1392.91  209.72 1441.39   210.6 1511.04  213.48 1725.77  215.32
#Mann= 3 , 0 , 0
       0     .12       0  779.96    .055       0  795.58     .12       0
Bank Sta=779.96,795.58
Exp/Cntr=.3,.1

Type RM Length L Ch R = 1 ,32042.03,656.05,731.44,813.23
XS GIS Cut Line= 4
     1854959.324      364964.433     1854513.906      364795.174
     1854264.472      364536.832     1852905.947       364300.76
#Sta/Elev= 30
       0   211.9  128.59  211.06  316.62  207.67  385.72  207.48  477.76  205.32
  759.88  201.88  799.14  200.58  836.97  200.15  925.83  196.37  992.14  195.15
 1055.67  192.05 1189.18  191.32 1192.64  191.28 1197.75  186.17 1202.75  186.17
 1207.79  191.21 1211.32  191.17 1324.75  190.59 1382.85  191.48 1690.01  192.87
 1738.62  194.58 1766.01  194.87  1806.6  198.22 1862.42  199.81 1920.91  200.65
 2025.76  205.14 2049.19  207.98 2101.08  210.98 2173.39  213.72 2214.48  213.67
#Mann= 3 , 0 , 0
       0     .12       0 1189.18    .055       0 1211.32     .12       0
Bank Sta=1189.18,1211.32
Exp/Cntr=.5,.3

Type RM Length L Ch R = 1 ,31310.59,273.96,259.59,346.44
XS GIS Cut Line= 2
     1855066.534      364562.261     1853204.377      363040.227
#Sta/Elev= 30
       0  209.53  112.89  205.21  357.62  198.56  511.92   197.2  529.33  194.46
  669.02  190.32  800.72  190.17  848.43  190.98   864.5  192.22   916.3  191.57
  955.81  192.31 1071.49  189.97 1162.61  191.06 1168.84  184.83 1173.84  184.83
 1180.25  191.24 1306.52  193.42 1360.79  195.47 1397.76  194.44 1462.16  194.81
 1567.63  196.58 1632.71  198.82 1736.77  199.13 1941.31  205.74 2073.18  206.06
 2100.02  207.74 2184.74   210.5 2207.58  212.62 2295.34   215.1 2405.04  216.05
#Mann= 3 , 0 , 0
       0     .12       0 1162.61    .055       0 1180.25     .12       0
Bank Sta=1162.61,1180.25
Exp/Cntr=.5,.3

Type RM Length L Ch R = 2 ,31192.96,,,
BEGIN DESCRIPTION:
US 15-401 (NCDOT 82 2013)
END DESCRIPTION:
Bridge Culvert--1,0,-1,-1, 0
Deck Dist Width WeirC Skew NumUp NumDn MinLoCord MaxHiCord MaxSubmerge Is_Ogee
81.88,71.5,2.6,0, 60, 60,193.57,,.95,0,0,0,,
       0   36.91  118.38  220.77  266.19  274.72  324.76  341.61  383.42  454.81
  467.88  525.39  551.58  607.77  628.63  640.56  700.84  714.16  786.84  821.65
  861.69  888.23  952.92  977.55  986.23 1031.22  1059.6 1087.83 1161.89 1262.46
 1285.24 1339.15 1367.24 1397.42 1408.34 1425.02 1482.33 1517.04 1540.07 1554.73
 1564.27 1604.02 1636.93 1674.35 1705.69 1728.49  1816.8  1860.7 1901.04 1914.63
 1960.38 1992.25 2006.91 2029.41 2123.23 2152.23 2196.35 2240.86 2266.81 2336.43
  210.18  208.91  207.16  204.38  203.46  203.03  201.76  201.58  200.33  199.27
  198.64  197.41  197.28   196.1  196.07  195.53  195.02   194.7   194.7  194.22
  194.17  193.71  194.12  193.94  193.59  193.99  193.57  193.98  194.34  194.42
  194.75  194.64  195.23  195.41  195.22  195.87  195.93  196.51  196.48  196.71
  197.19  197.81  197.85  198.47  198.61  199.64  201.37  202.76   203.4  203.92
  204.92   205.3  206.07  206.81   208.6  209.97  210.54  212.19  212.05  213.88
                                                                                
                                                                                
                                                                                
                                                                                
                                                                                
                                                                                
       0   36.91  118.38  220.77  266.19  274.72  324.76  341.61  383.42  454.81
  467.88  525.39  551.58  607.77  628.63  640.56  700.84  714.16  786.84  821.65
  861.69  888.23  952.92  977.55  986.23 1031.22  1059.6 1087.83 1161.89 1262.46
 1285.24 1339.15 1367.24 1397.42 1408.34 1425.02 1482.33 1517.04 1540.07 1554.73
 1564.27 1604.02 1636.93 1674.35 1705.69 1728.49  1816.8  1860.7 1901.04 1914.63
 1960.38 1992.25 2006.91 2029.41 2123.23 2152.23 2196.35 2240.86 2266.81 2336.43
  210.18  208.91  207.16  204.38  203.46  203.03  201.76  201.58  200.33  199.27
  198.64  197.41  197.28   196.1  196.07  195.53  195.02   194.7   194.7  194.22
  194.17  193.71  194.12  193.94  193.59  193.99  193.57  193.98  194.34  194.42
  194.75  194.64  195.23  195.41  195.22  195.87  195.93  196.51  196.48  196.71
  197.19  197.81  197.85  198.47  198.61  199.64  201.37  202.76   203.4  203.92
  204.92   205.3  206.07  206.81   208.6  209.97  210.54  212.19  212.05  213.88
                                                                                
                                                                                
                                                                                
                                                                                
                                                                                
                                                                                
Multiple Barrel Culv=2,6,6,71.5,.012,.4,1,8,1,184.91,184.89, 2,Culvert #1  , 0 ,81.88
 1167.92 1167.92 1174.59 1174.59
BC Design=,, 0 ,, 0 ,,,,,,

Type RM Length L Ch R = 1 ,31051.00,679.09,672.19,650.71
XS GIS Cut Line= 2
     1855163.371      364330.868     1853381.698      362865.443
#Sta/Elev= 30
  -16.63  214.08   21.54  212.47  122.55  209.97  181.28  207.16  250.26  207.18
  345.17  202.61  373.79  203.48  405.18  202.79  474.14  198.52  537.22  197.83
  550.24  198.25  611.55  197.17  663.95  191.83  702.65  191.43  749.06  189.83
 1037.63  189.54 1162.94  190.35 1168.93  184.36 1173.93  184.36 1179.85  190.28
 1248.28  190.64 1305.23  190.11 1462.14  189.52 1608.12  195.02 1830.43  200.02
 1910.66  202.51 1979.71  205.96  2111.1  209.46  2224.6  213.34 2290.28  214.64
#Mann= 3 , 0 , 0
  -16.63    .085       0 1037.63    .055       0 1305.23    .085       0
Bank Sta=1037.63,1305.23
Exp/Cntr=.5,.3

Type RM Length L Ch R = 1 ,30378.81,509.54,439.3,418.84
XS GIS Cut Line= 4
     1855106.312      363521.279     1854999.412      363115.948
     1854732.161      363151.582     1853231.102      362519.088
#Sta/Elev= 30
       0  210.42   78.89  210.16  207.07  207.93  435.37   207.4  456.49  206.66
  487.73  202.11  509.77  201.62  561.43  198.25  576.28  195.69  623.52  192.06
  688.35   189.9  721.09  189.28  961.66  190.07   968.6  183.13   973.6  183.13
  980.59  190.12 1253.86  191.04 1296.57  193.01 1318.86  194.78 1326.38  196.49
 1331.62  195.91 1376.88  198.72 1459.54  198.42 1568.86  200.07 1677.23     203
 1820.79  208.46 1966.23  212.79 2105.61  214.36 2177.18  216.04 2317.68   215.9
#Mann= 3 , 0 , 0
       0    .085       0  688.35    .055       0 1253.86    .085       0
Bank Sta=688.35,1253.86
Exp/Cntr=.5,.3