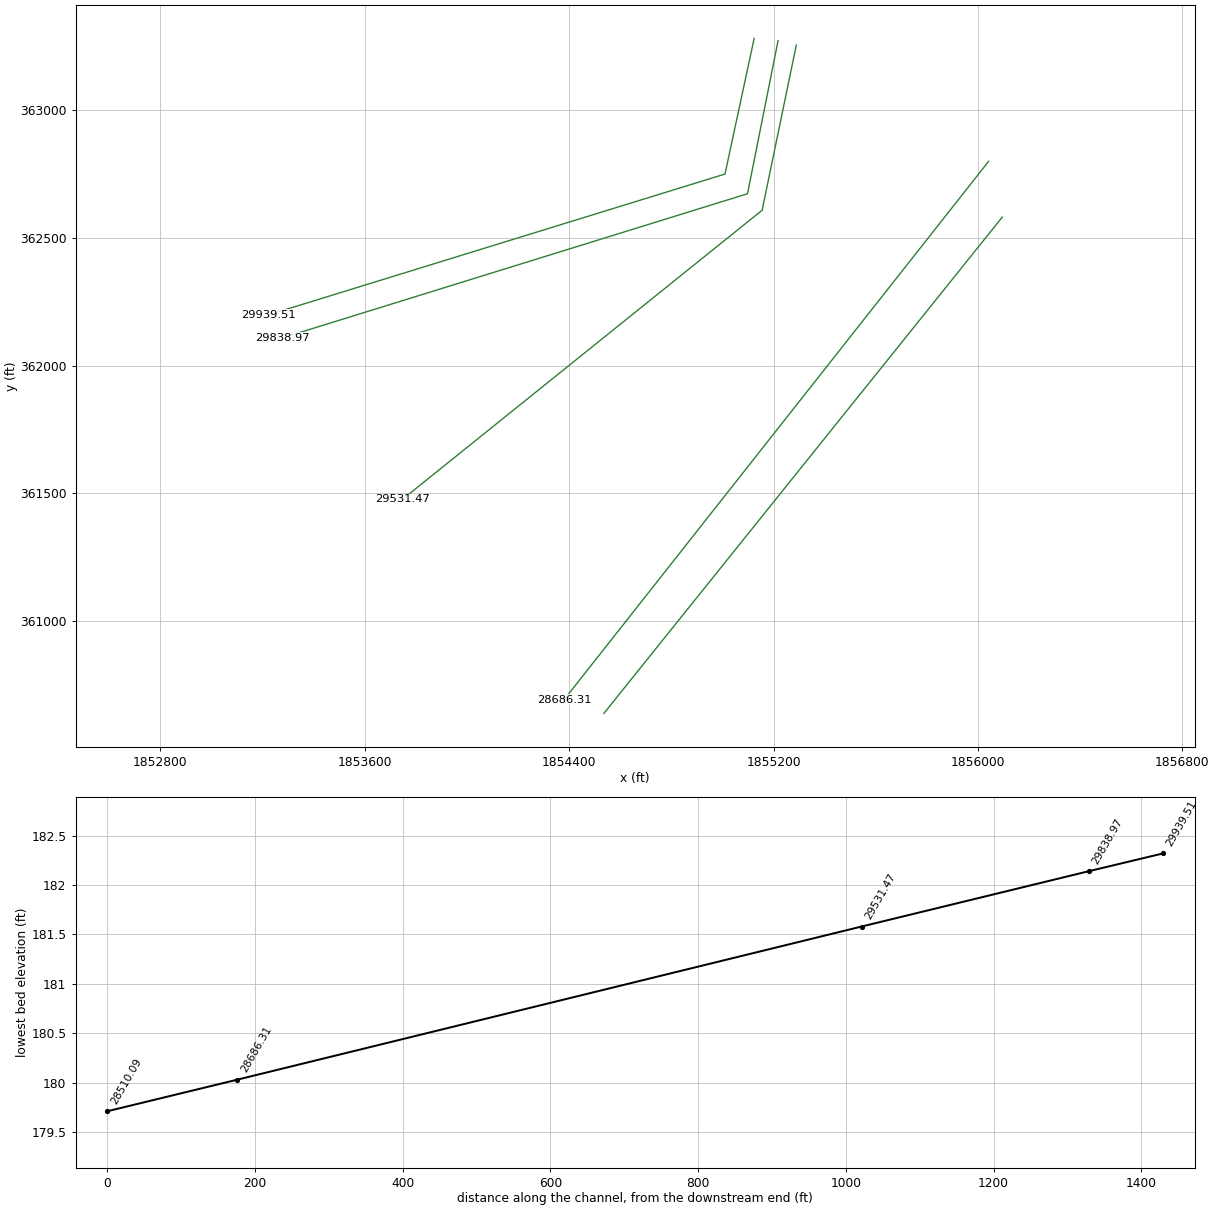
HEC-RAS study bridge.prj: Bridge Creek to Leith Creek

--- bridge.g02 (geometry) --- (continued)

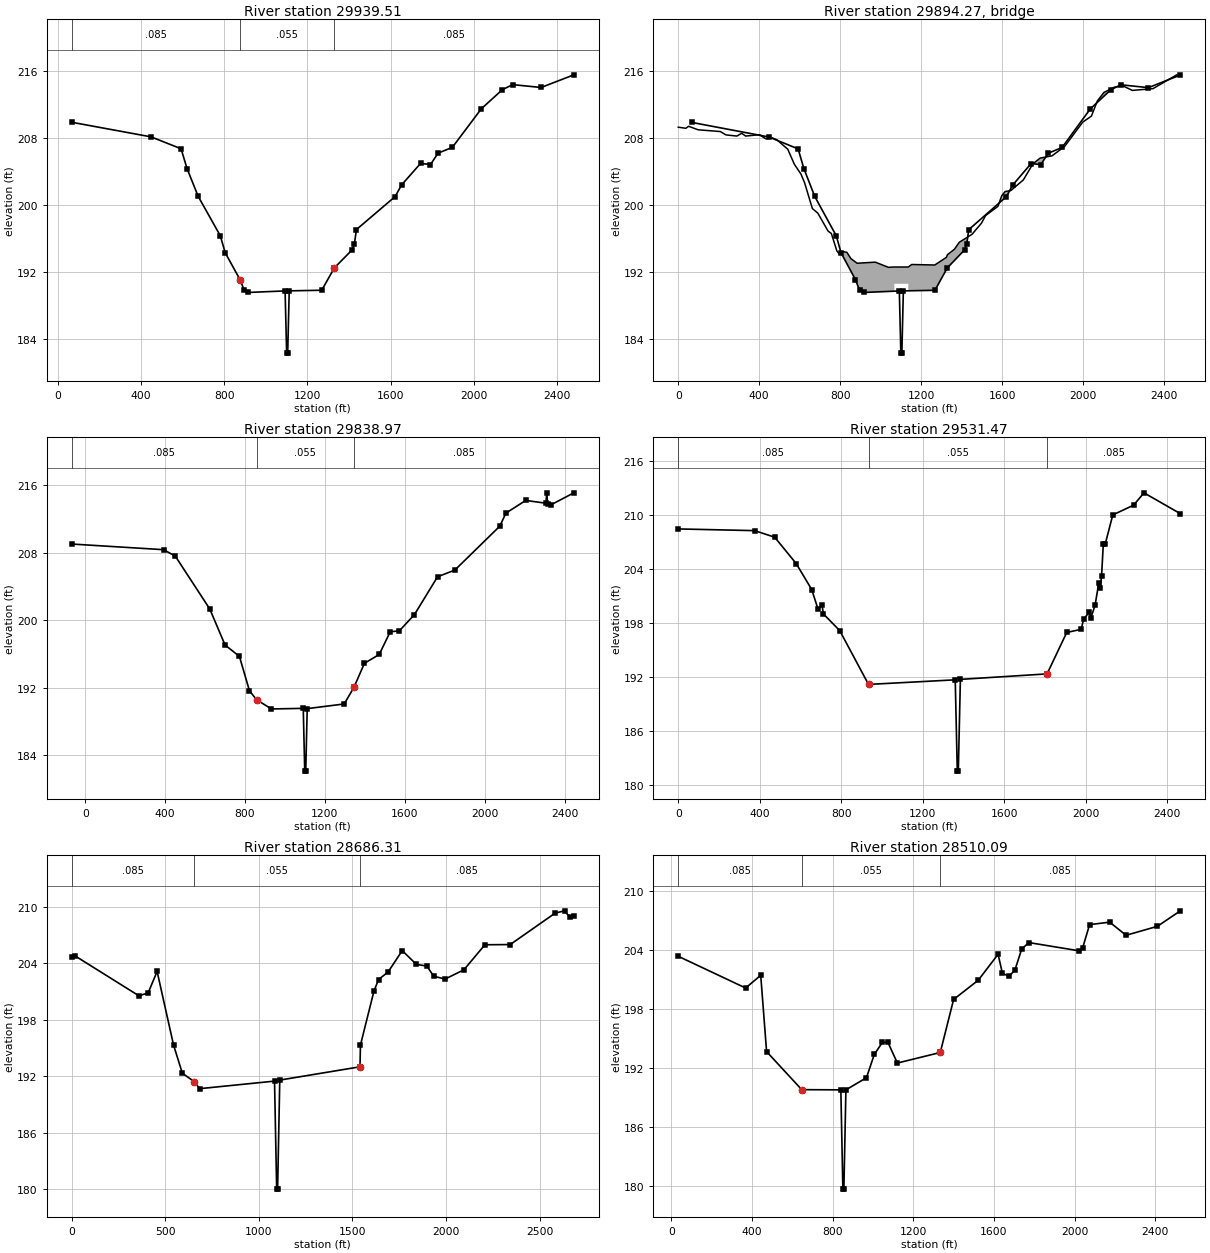
Type RM Length L Ch R = 1 ,29939.51,136.26,100.54,108.29
XS GIS Cut Line= 3
     1855124.129      363280.753     1855009.985      362749.762
     1853222.194      362198.387
#Sta/Elev= 30
   66.76  209.86  447.88  208.12  592.28   206.7  620.96  204.34  674.57  201.02
  780.91  196.32  804.58  194.29  875.45   191.1  896.16   189.8  916.09  189.56
 1092.45  189.74 1099.87  182.32 1104.87  182.32  1112.3  189.75 1268.49  189.82
 1329.29  192.49 1415.26  194.65 1425.44  195.32 1435.43  197.06 1621.56     201
 1652.47  202.38 1743.66  204.95 1791.53  204.82 1828.22  206.18 1896.71  206.87
 2035.97  211.47 2137.68  213.76  2186.8  214.35 2323.35  214.01 2480.77  215.52
#Mann= 3 , 0 , 0
   66.76    .085       0  875.45    .055       0 1329.29    .085       0
Bank Sta=875.45,1329.29
Exp/Cntr=.5,.3

Type RM Length L Ch R = 3 ,29894.27,,,
BEGIN DESCRIPTION:
Dogwood Lane (NCDOT # 78)
END DESCRIPTION:
Bridge Culvert--1,0,-1,-1, 0
Deck Dist Width WeirC Skew NumUp NumDn MinLoCord MaxHiCord MaxSubmerge Is_Ogee
28.99,32.5,2.6,0, 60, 60,192.56,,.95,0,0,0,,
       0   37.64   51.47   98.12  207.95  235.61  289.84  313.43  333.17  401.48
  431.97  467.18  487.51  540.94  573.64  606.68  624.44  662.72     690  740.21
  756.59  784.02   797.8  815.75  833.32  853.31  883.73  973.82 1038.63 1065.05
 1067.87 1136.87 1143.74 1153.85  1267.5 1324.76 1330.11 1364.18 1388.98 1451.91
 1498.45 1518.67 1579.44  1598.4 1615.05 1642.96 1704.96 1752.98 1788.04 1846.68
 1908.14 1998.87 2041.55 2070.75 2103.45  2152.8 2196.98 2243.95 2345.81 2463.02
  209.29  209.16   209.4  208.98  208.77  208.37  208.23  208.56  208.23  208.39
  207.91  207.99  207.78  206.67  204.87  203.68  202.65  199.58  199.02  196.89
   196.6   194.5  194.12  194.43  194.35   193.6  193.05  193.18  192.56   192.6
   192.6   192.6  192.73   192.9  192.84  193.75  194.07  194.71  195.56  196.51
  197.84  198.74  199.84  201.11  201.61  201.72  202.99  204.93   205.6  205.87
  206.96   209.9  210.61  212.42  213.44  214.05  214.22  213.68  213.89  215.54
                                                                                
                                                                                
                                                                                
   190.6   190.6
                                                                                
                                                                                
       0   37.64   51.47   98.12  207.95  235.61  289.84  313.43  333.17  401.48
  431.97  467.18  487.51  540.94  573.64  606.68  624.44  662.72     690  740.21
  756.59  784.02   797.8  815.75  833.32  853.31  883.73  973.82 1038.63 1065.05
 1067.87 1136.87 1143.74 1153.85  1267.5 1324.76 1330.11 1364.18 1388.98 1451.91
 1498.45 1518.67 1579.44  1598.4 1615.05 1642.96 1704.96 1752.98 1788.04 1846.68
 1908.14 1998.87 2041.55 2070.75 2103.45  2152.8 2196.98 2243.95 2345.81 2463.02
  209.29  209.16   209.4  208.98  208.77  208.37  208.23  208.56  208.23  208.39
  207.91  207.99  207.78  206.67  204.87  203.68  202.65  199.58  199.02  196.89
   196.6   194.5  194.12  194.43  194.35   193.6  193.05  193.18  192.56   192.6
   192.6   192.6  192.73   192.9  192.84  193.75  194.07  194.71  195.56  196.51
  197.84  198.74  199.84  201.11  201.61  201.72  202.99  204.93   205.6  205.87
  206.96   209.9  210.61  212.42  213.44  214.05  214.22  213.68  213.89  215.54
                                                                                
                                                                                
                                                                                
   190.6   190.6
                                                                                
                                                                                
BR Coef=-1 , 1 , 0 ,, 0 ,,,.8,0,1.2,0,
WSPro=,,,, 1 ,,,, 0 ,,,, 0 ,,,,-1 ,-1 ,-1 , 0 , 0 , 0 , 0 , 0
BC Design=,, 0 ,, 0 ,,,,,,

Type RM Length L Ch R = 1 ,29838.97,228.08,307.5,662.64
XS GIS Cut Line= 3
     1855217.667      363271.844     1855098.117      362672.702
     1853280.098      362109.303
#Sta/Elev= 30
  -67.76  209.06  391.71  208.39  450.59  207.63  623.34  201.36  699.86  197.09
  771.86  195.74  821.94  191.67  857.49  190.61     932  189.51 1091.44  189.58
 1098.88  182.14 1103.88  182.14 1111.29  189.55 1296.49   190.1 1345.26  192.07
 1397.71  194.92 1471.94  195.97 1526.97  198.66 1572.72  198.77 1648.09  200.69
 1764.05  205.18 1850.51  205.97 2076.28  211.19 2106.06  212.72 2205.72  214.23
 2305.84   213.9 2311.64  215.12 2314.62  213.79 2334.36  213.74 2446.51  215.13
#Mann= 3 , 0 , 0
  -67.76    .085       0  857.49    .055       0 1345.26    .085       0
Bank Sta=857.49,1345.26
Exp/Cntr=.5,.3

Type RM Length L Ch R = 1 ,29531.47,930.84,845.16,1390.46
XS GIS Cut Line= 3
     1855288.933      363254.028     1855155.308      362608.172
     1853747.787       361476.81
#Sta/Elev= 30
       0  208.48   375.3  208.29  473.75  207.56  579.33  204.63  655.41  201.75
  686.24  199.59  706.14  200.01  712.82  199.04  793.18  197.18  934.38  191.21
 1360.14  191.72 1370.28  181.58 1375.28  181.58 1385.47  191.77 1811.18  192.38
 1907.67  196.98 1978.55  197.33 1990.32  198.44 2017.56  199.22 2026.37  198.62
 2046.66  199.98 2065.46  202.53 2071.39  201.94 2078.65  203.21 2087.27   206.8
 2096.89  206.82 2133.87  210.04 2236.24  211.12 2286.78  212.49 2465.39  210.18
#Mann= 3 , 0 , 0
       0    .085       0  934.38    .055       0 1811.18    .085       0
Bank Sta=934.38,1811.18
Exp/Cntr=.3,.1

Type RM Length L Ch R = 1 ,28686.31,210.76,176.21,180.31
XS GIS Cut Line= 2
      1856041.69      362799.701     1854380.281      360692.874
#Sta/Elev= 30
       0  204.61   19.91  204.75  358.34  200.55  407.87  200.84  456.05  203.13
  544.04  195.31  590.91  192.33  654.67  191.43   683.3  190.69 1083.52  191.49
 1094.98  180.03 1099.98  180.03 1111.55   191.6  1540.3  193.01 1542.64  195.31
 1614.42  201.01 1639.41  202.27 1690.37  203.07 1766.03  205.34 1841.29  203.88
 1897.47   203.7 1934.29  202.62 1995.05  202.32 2095.45   203.3 2207.92  205.96
 2342.89  205.98 2583.49  209.32 2633.19  209.56 2661.07   208.9 2683.09  209.04
#Mann= 3 , 0 , 0
       0    .085       0  654.67    .055       0  1540.3    .085       0
Bank Sta=654.67,1540.3
Exp/Cntr=.5,.3

Type RM Length L Ch R = 1 ,28510.09,562.65,286.88,451.86
XS GIS Cut Line= 2
      1856095.14      362581.447     1854536.177      360639.424
#Sta/Elev= 30
    33.9  203.33  368.26  200.11  443.02   201.4  472.15  193.66  646.53   189.8
  840.43  189.78   850.5  179.71   855.5  179.71  865.57  189.78  967.57  191.01
 1006.23  193.37  1046.3  194.59 1074.17  194.59 1120.92   192.5 1333.61  193.57
  1399.8  198.95 1521.99   200.9 1620.35  203.53 1641.92   201.6 1675.51   201.3
 1704.25  201.96 1737.55  204.06  1772.8  204.72 2023.61  203.88 2039.95  204.18
 2074.11  206.54 2173.98  206.79 2255.31  205.46 2410.83  206.37 2524.25  207.94
#Mann= 3 , 0 , 0
    33.9    .085       0  646.53    .055       0 1333.61    .085       0
Bank Sta=646.53,1333.61
Exp/Cntr=.5,.3