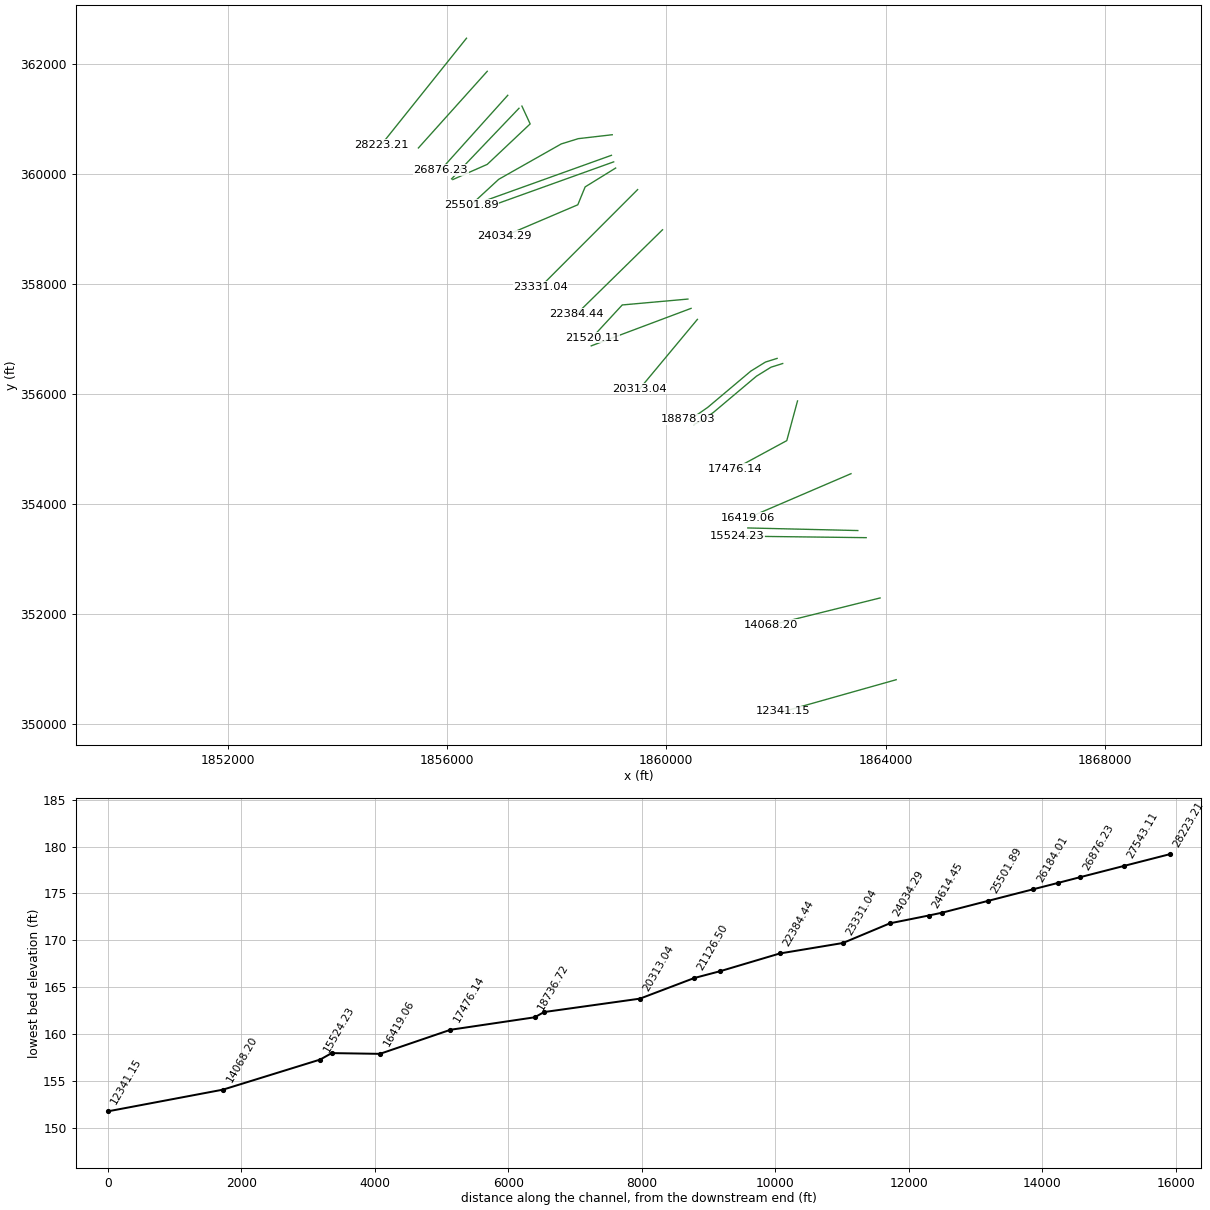
HEC-RAS study bridge.prj: Bridge Creek to Leith Creek

--- bridge.g02 (geometry) --- (continued)

Type RM Length L Ch R = 2 ,28386.74,,,
BEGIN DESCRIPTION:
Unknown Dam (assumed same as Berwick Drive)
END DESCRIPTION:
Bridge Culvert--1,0,-1,-1, 0
Deck Dist Width WeirC Skew NumUp NumDn MinLoCord MaxHiCord MaxSubmerge Is_Ogee
107.1,32.5,2.6,0, 60, 60,194.84,,.95,0,0,0,,
       0   18.18   38.96   97.55  118.11  183.67   251.5  289.13  330.38  352.66
  361.89  383.99  387.93  407.76  414.23   445.1  463.39  471.97  490.03  502.62
  621.11  668.32  721.66  758.73  806.37  850.21  876.45  883.24  910.94  946.66
 1152.79 1198.81 1255.25 1266.69 1276.55 1289.77 1310.17 1379.18 1392.75 1403.83
 1443.21 1480.27 1598.53 1668.53 1728.25 1820.44 1830.21  1933.3 1996.82 2016.85
 2038.57 2051.45 2129.15 2224.63 2247.88 2302.75 2330.38 2370.07 2482.54 2490.34
   203.1  203.66  203.38  202.05  201.92   200.2   199.7  198.86  198.63  198.05
  197.97  198.34  198.61  198.44  198.08   197.6  196.96  196.38  195.83  195.08
   195.3  194.98  195.51  195.51  194.94  195.08  194.85   195.1  195.11  194.83
  194.92  195.31  195.43  195.73  196.36  196.65  197.83  199.78  200.71  201.85
  201.63  202.13  202.07  202.96  204.42  204.22  204.41  203.63  203.51  204.18
  205.67  206.16  206.14  205.65  205.86   208.9   209.2  210.33   210.1  209.89
                                                                                
                                                                                
                                                                                
                                                                                
                                                                                
                                                                                
       0   18.18   38.96   97.55  118.11  183.67   251.5  289.13  330.38  352.66
  361.89  383.99  387.93  407.76  414.23   445.1  463.39  471.97  490.03  502.62
  621.11  668.32  721.66  758.73  806.37  850.21  876.45  883.24  910.94  946.66
 1152.79 1198.81 1255.25 1266.69 1276.55 1289.77 1310.17 1379.18 1392.75 1403.83
 1443.21 1480.27 1598.53 1668.53 1728.25 1820.44 1830.21  1933.3 1996.82 2016.85
 2038.57 2051.45 2129.15 2224.63 2247.88 2302.75 2330.38 2370.07 2482.54 2490.34
   203.1  203.66  203.38  202.05  201.92   200.2   199.7  198.86  198.63  198.05
  197.97  198.34  198.61  198.44  198.08   197.6  196.96  196.38  195.83  195.08
   195.3  194.98  195.51  195.51  194.94  195.08  194.85   195.1  195.11  194.83
  194.92  195.31  195.43  195.73  196.36  196.65  197.83  199.78  200.71  201.85
  201.63  202.13  202.07  202.96  204.42  204.22  204.41  203.63  203.51  204.18
  205.67  206.16  206.14  205.65  205.86   208.9   209.2  210.33   210.1  209.89
                                                                                
                                                                                
                                                                                
                                                                                
                                                                                
                                                                                
Multiple Barrel Culv=1,2.5,,32.5,.027,.7,1,2,2,190.85,190.83, 2,Culvert #1  , 0 ,107.1
   851.5   851.5   854.5   854.5
BC Design=,, 0 ,, 0 ,,,,,,

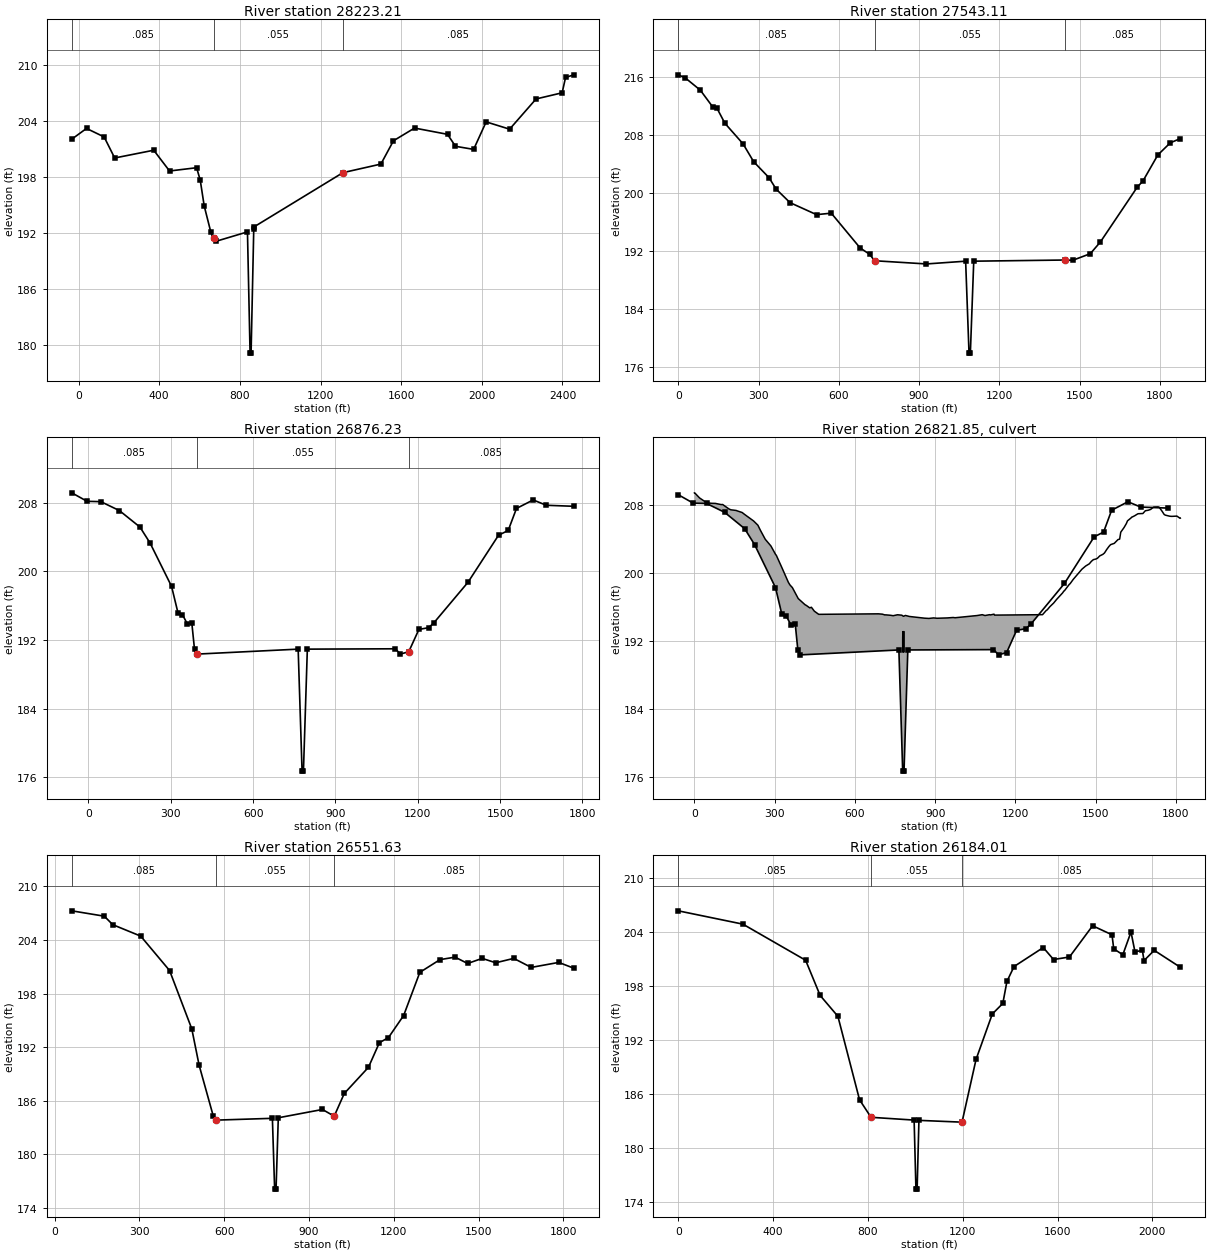
Type RM Length L Ch R = 1 ,28223.21,734.71,680.1,665.77
XS GIS Cut Line= 2
     1856353.483      362470.092     1854794.519      360528.069
#Sta/Elev= 30
   -33.9  202.05   39.25   203.2  126.65  202.29  178.91  200.04  372.67  200.87
  451.11  198.65  585.32     199  603.32  197.67  623.02  194.91  655.79  192.12
  669.26  191.44  680.88  191.13  837.54  192.14   850.5  179.18   855.5  179.18
  868.76  192.44  870.44  192.68 1310.89  198.47 1499.44  199.39 1561.68  201.88
 1666.34  203.24  1829.8  202.57 1869.38  201.29 1959.39  200.96 2021.45   203.9
 2137.79  203.12 2268.97  206.35 2398.39  207.01 2415.35  208.65 2456.45  208.93
#Mann= 3 , 0 , 0
   -33.9    .085       0  669.26    .055       0 1310.89    .085       0
Bank Sta=669.26,1310.89
Exp/Cntr=.5,.3

Type RM Length L Ch R = 1 ,27543.11,812.24,666.88,649.92
XS GIS Cut Line= 2
     1856732.088      361868.778     1855476.009      360474.619
#Sta/Elev= 30
       0  216.26    25.2  215.87   82.49  214.15  129.96  211.79  144.94  211.65
  174.35  209.59  242.37  206.75  282.06  204.29  339.27   202.1  365.77  200.53
  417.87  198.66  516.81  197.01  572.01  197.21  679.91  192.42  715.78  191.54
  733.73  190.66  927.77  190.22 1074.17   190.6 1086.83  177.94 1091.83  177.94
 1104.49   190.6 1444.94  190.76 1474.86  190.73 1540.08  191.63 1577.93  193.25
 1715.71   200.8 1736.89  201.64 1792.56  205.23 1839.13   206.9 1876.54  207.48
#Mann= 3 , 0 , 0
       0    .085       0  733.73    .055       0 1444.94    .085       0
Bank Sta=733.73,1444.94
Exp/Cntr=.5,.3

Type RM Length L Ch R = 1 ,26876.23,322.58,324.6,363.6
XS GIS Cut Line= 2
     1857106.239      361432.268     1855881.339      360073.743
#Sta/Elev= 30
  -60.57  209.16   -4.67  208.17   45.43  208.13  112.95  207.09  187.82  205.17
  224.67  203.31  302.96  198.26   326.3  195.18  342.72  194.96  360.62  193.87
  376.68  194.02  386.63  190.91   394.9  190.36  764.25  190.94  778.47  176.72
  783.47  176.72  797.69  190.94 1117.95  190.98 1136.95  190.37 1167.03  190.63
 1204.19  193.24 1239.65  193.44 1259.29  194.03 1383.12  198.74 1494.36  204.22
 1529.43  204.77 1559.61  207.34 1620.43  208.33 1668.35  207.71 1768.63  207.59
#Mann= 3 , 0 , 0
  -60.57    .085       0   394.9    .055       0 1167.03    .085       0
Bank Sta=394.9,1167.03
Exp/Cntr=.5,.3

Type RM Length L Ch R = 2 ,26821.85,,,
BEGIN DESCRIPTION:
Berwick Drive (Dam SCOTL-14)
END DESCRIPTION:
Bridge Culvert--1,0,-1,-1, 0
Deck Dist Width WeirC Skew NumUp NumDn MinLoCord MaxHiCord MaxSubmerge Is_Ogee
38.13,32.5,2.6,0,135,135,194.64,,.95,0,0,0,,
       0      .9   19.09   38.98   44.52   64.65   78.19   99.75  105.51   128.4
  135.94  156.06  159.17   178.3   188.2  207.49  217.17  221.07  237.23  246.68
  264.69  285.96  303.65  305.92  326.39  351.39  357.06  366.11  388.03  414.12
  415.92  419.47  430.89  432.83  435.56  437.28  439.68  448.28  459.52  460.51
  464.59  687.76   702.6  710.87  712.04  714.96  732.94  741.74  742.78  759.22
  775.04  781.36  788.76  803.61  860.16  876.27  893.86  907.39  945.38  967.18
  974.25 1050.62 1057.02 1075.83 1086.17 1103.38 1105.72 1106.13 1111.97 1119.92
 1121.58 1301.02 1301.14 1301.21 1301.51    1315 1318.88 1328.75 1337.71 1342.65
 1353.85 1376.41 1380.88  1383.2 1389.66 1397.86 1400.82 1404.64 1416.22 1438.05
 1448.59  1462.5 1476.12 1483.86 1491.37 1499.63 1506.13  1515.2 1526.77  1532.8
 1540.98 1549.37  1555.7 1569.47 1583.16 1589.59 1593.64 1606.08 1614.74 1618.84
  1631.6 1635.36 1636.92 1645.79 1657.09 1659.76 1676.26 1685.59 1695.52 1705.26
  1713.5 1717.14 1733.11 1737.25 1747.24 1756.24 1760.56 1776.13 1781.39 1787.41
  1801.9 1803.58 1803.97 1815.31  1816.3
  209.37  209.38  208.78  208.36  208.21  208.15  208.14     208  208.01   207.5
  207.39  207.31  207.27  207.07  206.83  206.39  206.17  206.08  205.58  204.98
  203.93  203.14  202.13  202.06  200.64  198.86  198.57  198.26  196.97  196.23
  196.21  196.14  195.88   195.9  195.93  195.95  195.85  195.49  195.24  195.21
  195.12  195.18  195.14  195.05  195.05  195.06  195.01  194.96  194.96  195.07
  195.02  194.89  194.99  194.87  194.67  194.64   194.7  194.66   194.7  194.75
  194.72  194.97  194.98  195.08  194.98  195.08  195.05  195.05  195.09  195.14
  195.03  195.07  195.08  195.08  195.09  195.57  195.65  196.02   196.3  196.44
  196.87  197.64  197.85  197.89  198.15   198.5  198.62  198.73  199.23  200.04
  200.42  200.79  201.05  201.34  201.54   201.6  201.69  201.98  202.16  202.32
  202.72  203.08   203.3  203.45  203.89  203.95  204.76  205.31  205.78  206.09
  206.42  206.54  206.55  206.69  206.91  206.93  206.95  207.28  207.33  207.43
  207.64  207.71  207.73  207.69  207.26  206.83  206.76  206.64  206.62  206.62
  206.65  206.65  206.64  206.39  206.41
                                                                                
                                                                                
                                                                                
                                                                                
                                                                                
                                                                                
                                                                                
                                                                                
                                                                                
                                                                                
                                                                                
                                                                                
                                                                                
                                        
       0      .9   19.09   38.98   44.52   64.65   78.19   99.75  105.51   128.4
  135.94  156.06  159.17   178.3   188.2  207.49  217.17  221.07  237.23  246.68
  264.69  285.96  303.65  305.92  326.39  351.39  357.06  366.11  388.03  414.12
  415.92  419.47  430.89  432.83  435.56  437.28  439.68  448.28  459.52  460.51
  464.59  687.76   702.6  710.87  712.04  714.96  732.94  741.74  742.78  759.22
  775.04  781.36  788.76  803.61  860.16  876.27  893.86  907.39  945.38  967.18
  974.25 1050.62 1057.02 1075.83 1086.17 1103.38 1105.72 1106.13 1111.97 1119.92
 1121.58 1301.02 1301.14 1301.21 1301.51    1315 1318.88 1328.75 1337.71 1342.65
 1353.85 1376.41 1380.88  1383.2 1389.66 1397.86 1400.82 1404.64 1416.22 1438.05
 1448.59  1462.5 1476.12 1483.86 1491.37 1499.63 1506.13  1515.2 1526.77  1532.8
 1540.98 1549.37  1555.7 1569.47 1583.16 1589.59 1593.64 1606.08 1614.74 1618.84
  1631.6 1635.36 1636.92 1645.79 1657.09 1659.76 1676.26 1685.59 1695.52 1705.26
  1713.5 1717.14 1733.11 1737.25 1747.24 1756.24 1760.56 1776.13 1781.39 1787.41
  1801.9 1803.58 1803.97 1815.31  1816.3
  209.37  209.38  208.78  208.36  208.21  208.15  208.14     208  208.01   207.5
  207.39  207.31  207.27  207.07  206.83  206.39  206.17  206.08  205.58  204.98
  203.93  203.14  202.13  202.06  200.64  198.86  198.57  198.26  196.97  196.23
  196.21  196.14  195.88   195.9  195.93  195.95  195.85  195.49  195.24  195.21
  195.12  195.18  195.14  195.05  195.05  195.06  195.01  194.96  194.96  195.07
  195.02  194.89  194.99  194.87  194.67  194.64   194.7  194.66   194.7  194.75
  194.72  194.97  194.98  195.08  194.98  195.08  195.05  195.05  195.09  195.14
  195.03  195.07  195.08  195.08  195.09  195.57  195.65  196.02   196.3  196.44
  196.87  197.64  197.85  197.89  198.15   198.5  198.62  198.73  199.23  200.04
  200.42  200.79  201.05  201.34  201.54   201.6  201.69  201.98  202.16  202.32
  202.72  203.08   203.3  203.45  203.89  203.95  204.76  205.31  205.78  206.09
  206.42  206.54  206.55  206.69  206.91  206.93  206.95  207.28  207.33  207.43
  207.64  207.71  207.73  207.69  207.26  206.83  206.76  206.64  206.62  206.62
  206.65  206.65  206.64  206.39  206.41
                                                                                
                                                                                
                                                                                
                                                                                
                                                                                
                                                                                
                                                                                
                                                                                
                                                                                
                                                                                
                                                                                
                                                                                
                                                                                
                                        
Multiple Barrel Culv=1,2.5,,32.5,.027,.7,1,2,2,190.65,190.63, 2,Culvert #1  , 0 ,38.13
  779.46  779.46  782.46  782.46
BC Design=,, 0 ,, 0 ,,,,,,

Type RM Length L Ch R = 1 ,26551.63,328.85,367.61,305.21
XS GIS Cut Line= 2
     1857311.131      361196.196     1856081.778      359913.392
#Sta/Elev= 30
   60.57  207.25  175.68  206.65  205.63   205.7  304.61  204.42  406.72  200.57
  485.27  194.05  511.16  189.99  560.91  184.34  572.63  183.84  770.54  184.04
  778.46  176.12  783.46  176.12  791.44   184.1  947.62  185.03  989.29  184.28
 1024.88  186.82 1110.53  189.75 1149.15   192.5 1181.27  193.07    1235  195.54
 1292.38  200.37 1363.57  201.79 1416.99  202.07 1461.43  201.36 1512.98  201.93
  1560.8  201.44 1624.68  201.93 1686.55  200.92 1783.95  201.48 1837.34  200.83
#Mann= 3 , 0 , 0
   60.57    .085       0  572.63    .055       0  989.29    .085       0
Bank Sta=572.63,989.29
Exp/Cntr=.5,.3

Type RM Length L Ch R = 1 ,26184.01,755.83,682.13,427.13
XS GIS Cut Line= 4
     1857364.582      361236.284     1857515.088      360912.124
     1856732.088      360176.189     1856104.048       359900.03
#Sta/Elev= 30
       0  206.37  272.78  204.89  537.35  200.88  598.56  196.97  673.52  194.65
  764.79  185.38  813.33  183.43  995.08  183.12 1002.75  175.45 1007.75  175.45
 1015.39  183.09 1197.17  182.89 1256.32  189.86 1324.92  194.91 1369.23  196.08
 1386.63  198.53 1416.63  200.18 1539.85  202.29 1583.23  200.96 1650.33  201.24
 1748.04  204.71 1829.85  203.71 1837.17  202.15 1875.51  201.49 1910.03  204.02
 1926.69  201.82 1958.03  201.97 1964.92  200.84 2007.95  201.98 2118.03   200.1
#Mann= 3 , 0 , 0
       0    .085       0  813.33    .055       0 1197.17    .085       0
Bank Sta=813.33,1197.17
Exp/Cntr=.3,.1

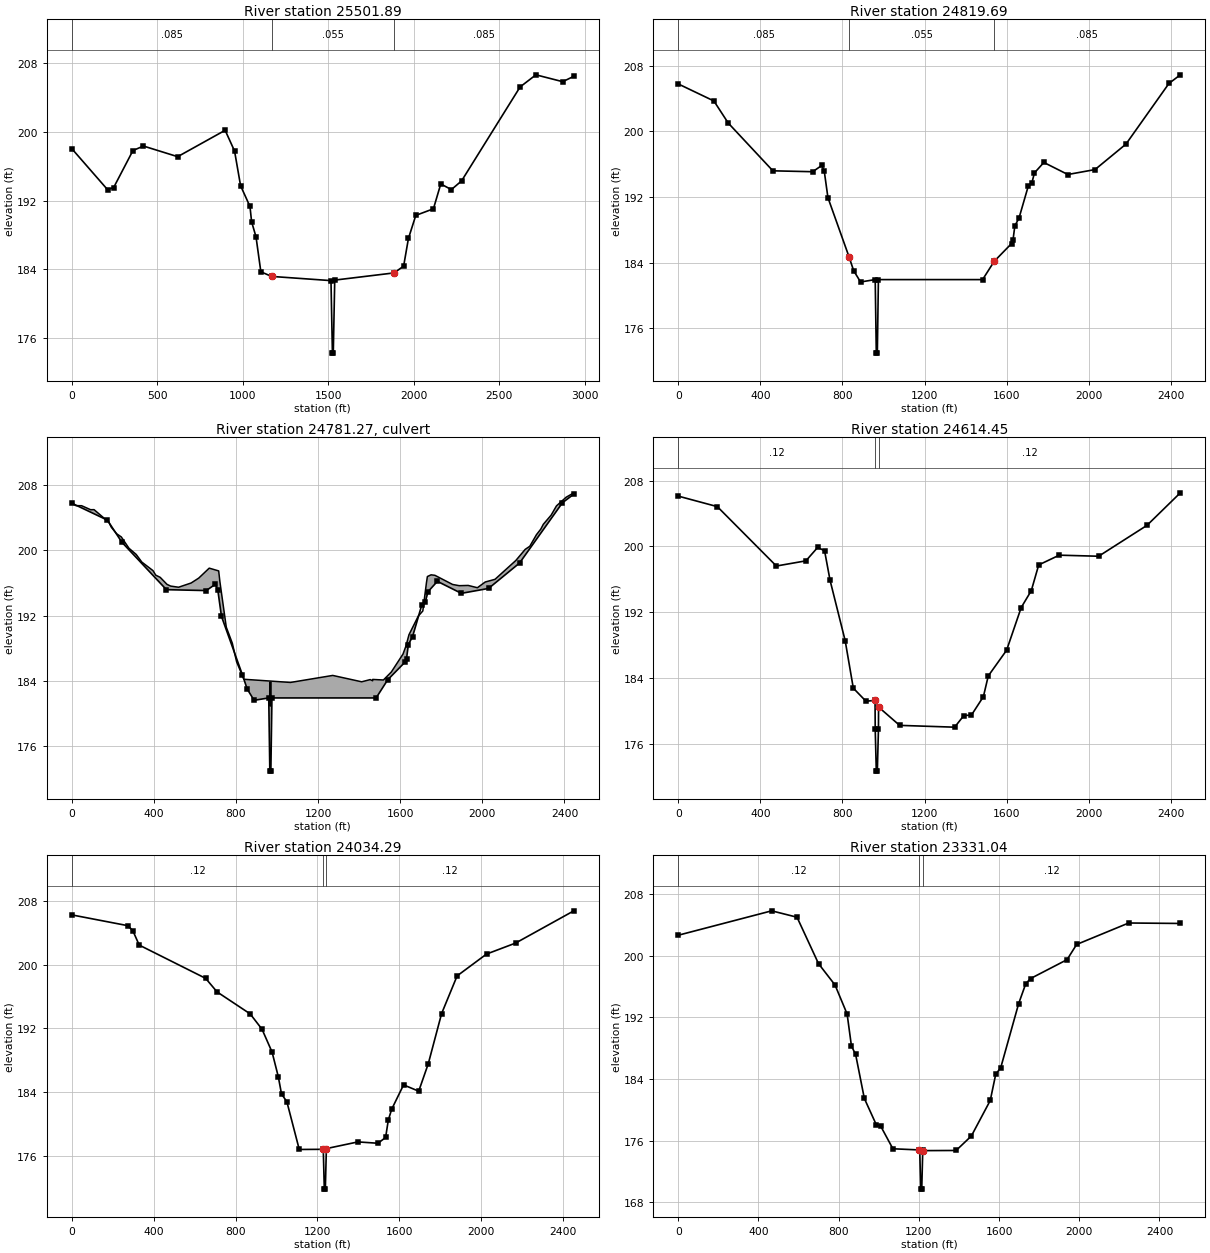
Type RM Length L Ch R = 1 ,25501.89,1050.5,682.2,428.35
XS GIS Cut Line= 5
     1859012.628      360715.145     1858393.497      360643.878
     1858082.491      360547.937     1856941.434      359904.484
     1856442.566      359445.703
#Sta/Elev= 30
       0  198.06  208.97  193.28  244.98  193.52  357.86  197.84  419.34  198.36
   619.4  197.12  897.02   200.2  952.04  197.78  987.35  193.73 1042.23  191.31
 1051.73  189.53 1077.62  187.76 1105.84  183.69 1168.69  183.15 1515.98  182.66
 1524.44   174.2 1529.44   174.2 1537.96  182.72 1885.18  183.56 1940.91  184.35
    1969  187.58 2012.06  190.27 2115.19  191.04  2158.1  193.94 2220.19  193.28
 2279.61  194.29 2622.25  205.26 2714.61  206.67 2871.31  205.87 2936.42   206.5
#Mann= 3 , 0 , 0
       0    .085       0 1168.69    .055       0 1885.18    .085       0
Bank Sta=1168.69,1885.18
Exp/Cntr=.5,.3

Type RM Length L Ch R = 1 ,24819.69,126.94,205.24,223.23
XS GIS Cut Line= 2
     1858998.345      360341.144     1856695.534      359517.121
#Sta/Elev= 30
       0  205.79  173.74  203.71   243.5  201.02  461.02  195.19   655.1  195.08
  698.84  195.84  711.03   195.2  729.22  191.92  831.57  184.73  854.54  183.01
  888.13  181.63  959.53  181.92  964.82  172.95  969.82  172.95  975.11  181.92
 1482.59  181.92 1539.27  184.15 1623.77  186.32 1630.75  186.74 1639.75  188.47
  1660.2  189.44 1704.84   193.3  1722.8  193.74 1735.33  194.94 1781.01  196.21
 1897.88  194.74 2030.17  195.34 2181.11  198.45 2390.47  205.85  2445.8   206.9
#Mann= 3 , 0 , 0
       0    .085       0  831.57    .055       0 1539.27    .085       0
Bank Sta=831.57,1539.27
Exp/Cntr=.5,.3

Type RM Length L Ch R = 2 ,24781.27,,,
BEGIN DESCRIPTION:
Jones Lake Dam (Dam SCOTL-15)
END DESCRIPTION:
Bridge Culvert--1,0,-1,-1, 0
Deck Dist Width WeirC Skew NumUp NumDn MinLoCord MaxHiCord MaxSubmerge Is_Ogee
22.17,32.5,2.6,0, 60, 60,183.9,,.95,0,0,0,,
       0   20.18    48.1   91.91  108.53  180.01  192.84  218.84  241.41  278.55
  313.75  341.39  395.44  409.12  430.76  463.97  481.71  520.29  581.48  618.48
   669.6  715.64  721.84  752.67  782.21  803.06  838.55 1065.29 1271.21 1412.17
 1453.82 1465.66 1466.03 1518.07 1556.65 1613.54 1628.06 1642.64 1688.26 1710.11
  1727.7  1732.3 1750.29 1769.06 1855.04 1887.52 1931.13 1975.96 2014.06 2061.82
 2163.23  2208.8  2231.2 2263.59 2284.71 2296.95 2335.25 2361.09 2408.29  2445.8
  205.79  205.49  205.48  204.99     205  203.47  202.83  202.04  201.65  200.27
  199.51  198.57  197.53  196.97   196.7  195.84  195.63  195.49  196.01  196.61
  197.83  197.49  196.13   190.6  188.62  186.34  184.21  183.82  184.68   183.9
  184.17  184.02  184.19  184.12   185.1   187.3  188.29  189.67  191.96  192.58
  196.03   196.8  197.01  196.95  195.83  195.68  195.71  195.43  196.13  196.46
  198.77  200.13  200.51  201.93  202.61   203.2  204.33  205.46  206.52  207.06
                                                                                
                                                                                
                                                                                
                                                                                
                                                                                
                                                                                
       0   20.18    48.1   91.91  108.53  180.01  192.84  218.84  241.41  278.55
  313.75  341.39  395.44  409.12  430.76  463.97  481.71  520.29  581.48  618.48
   669.6  715.64  721.84  752.67  782.21  803.06  838.55 1065.29 1271.21 1412.17
 1453.82 1465.66 1466.03 1518.07 1556.65 1613.54 1628.06 1642.64 1688.26 1710.11
  1727.7  1732.3 1750.29 1769.06 1855.04 1887.52 1931.13 1975.96 2014.06 2061.82
 2163.23  2208.8  2231.2 2263.59 2284.71 2296.95 2335.25 2361.09 2408.29  2445.8
  205.79  205.49  205.48  204.99     205  203.47  202.83  202.04  201.65  200.27
  199.51  198.57  197.53  196.97   196.7  195.84  195.63  195.49  196.01  196.61
  197.83  197.49  196.13   190.6  188.62  186.34  184.21  183.82  184.68   183.9
  184.17  184.02  184.19  184.12   185.1   187.3  188.29  189.67  191.96  192.58
  196.03   196.8  197.01  196.95  195.83  195.68  195.71  195.43  196.13  196.46
  198.77  200.13  200.51  201.93  202.61   203.2  204.33  205.46  206.52  207.06
                                                                                
                                                                                
                                                                                
                                                                                
                                                                                
                                                                                
Multiple Barrel Culv=1,3,,32.5,.027,.7,1,2,2,180.9,180.9, 2,Culvert #1  , 0 ,22.17
  965.57  965.57  969.07  969.07
BC Design=,, 0 ,, 0 ,,,,,,

Type RM Length L Ch R = 1 ,24614.45,572.54,580.16,544.27
XS GIS Cut Line= 2
     1859039.354      360221.887     1856736.542      359397.863
#Sta/Elev= 30
       0  206.12  190.41  204.84  478.07  197.61  621.82  198.24  679.51  199.88
  712.92  199.46  739.58  195.87  813.37   188.5  852.87  182.74  914.51  181.15
  958.76  181.25  959.57  177.73  964.82  172.64  969.82  172.64  975.33  177.74
  975.88  180.44 1078.49  178.21 1346.37  177.99 1391.45  179.41 1428.28  179.46
 1486.58  181.71  1510.3  184.23 1599.64  187.36 1670.59  192.55 1720.05  194.62
 1755.86  197.74 1856.04  198.93 2047.98   198.8 2283.46  202.56  2445.8  206.52
#Mann= 3 , 0 , 0
       0     .12       0  958.76    .055       0  975.88     .12       0
Bank Sta=958.76,975.88
Exp/Cntr=.5,.3

Type RM Length L Ch R = 1 ,24034.29,644.37,703.25,746.09
XS GIS Cut Line= 4
     1859074.987      360109.376     1858518.214      359766.404
     1858384.589      359441.249     1857052.789      358875.568
#Sta/Elev= 30
       0  206.25  274.91  204.89  298.68  204.24  329.35  202.46  653.93  198.28
  709.61  196.58  871.28  193.82   929.3  191.89  978.41  189.02 1008.81  185.93
 1024.46  183.76 1050.62  182.79 1111.17  176.79 1228.53  176.81 1233.53  171.81
 1238.53  171.81 1243.62   176.9 1397.78  177.74 1495.76  177.57 1532.98   178.3
 1546.15  180.48 1562.59  181.84 1620.64   184.9 1694.65  184.11 1741.42  187.56
 1806.38  193.85 1882.29  198.59 2025.91  201.33 2167.84  202.71 2452.43  206.76
#Mann= 3 , 0 , 0
       0     .12       0 1228.53    .055       0 1243.62     .12       0
Bank Sta=1228.53,1243.62
Exp/Cntr=.3,.1

Type RM Length L Ch R = 1 ,23331.04,832.96,946.6,831.19
XS GIS Cut Line= 2
     1859475.863      359717.408     1857703.099      357949.099
#Sta/Elev= 30
       0  202.68  466.03  205.85  592.38  205.02  699.82  198.98  781.88  196.22
  842.23  192.45  863.81  188.29   884.6  187.21  928.08  181.49  987.41  178.09
 1009.52   177.9  1070.5  174.95 1201.88   174.8 1204.32  174.79  1209.4  169.71
  1214.4  169.71 1219.42  174.73 1221.91  174.71 1385.89  174.73 1461.88  176.61
 1556.02  181.22 1583.33  184.62 1608.43  185.49  1697.7   193.8 1733.33   196.4
 1757.41  197.06 1939.13  199.51 1986.76  201.48 2246.49  204.27 2503.92  204.21
#Mann= 3 , 0 , 0
       0     .12       0 1201.88    .055       0 1221.91     .12       0
Bank Sta=1201.88,1221.91
Exp/Cntr=.3,.1

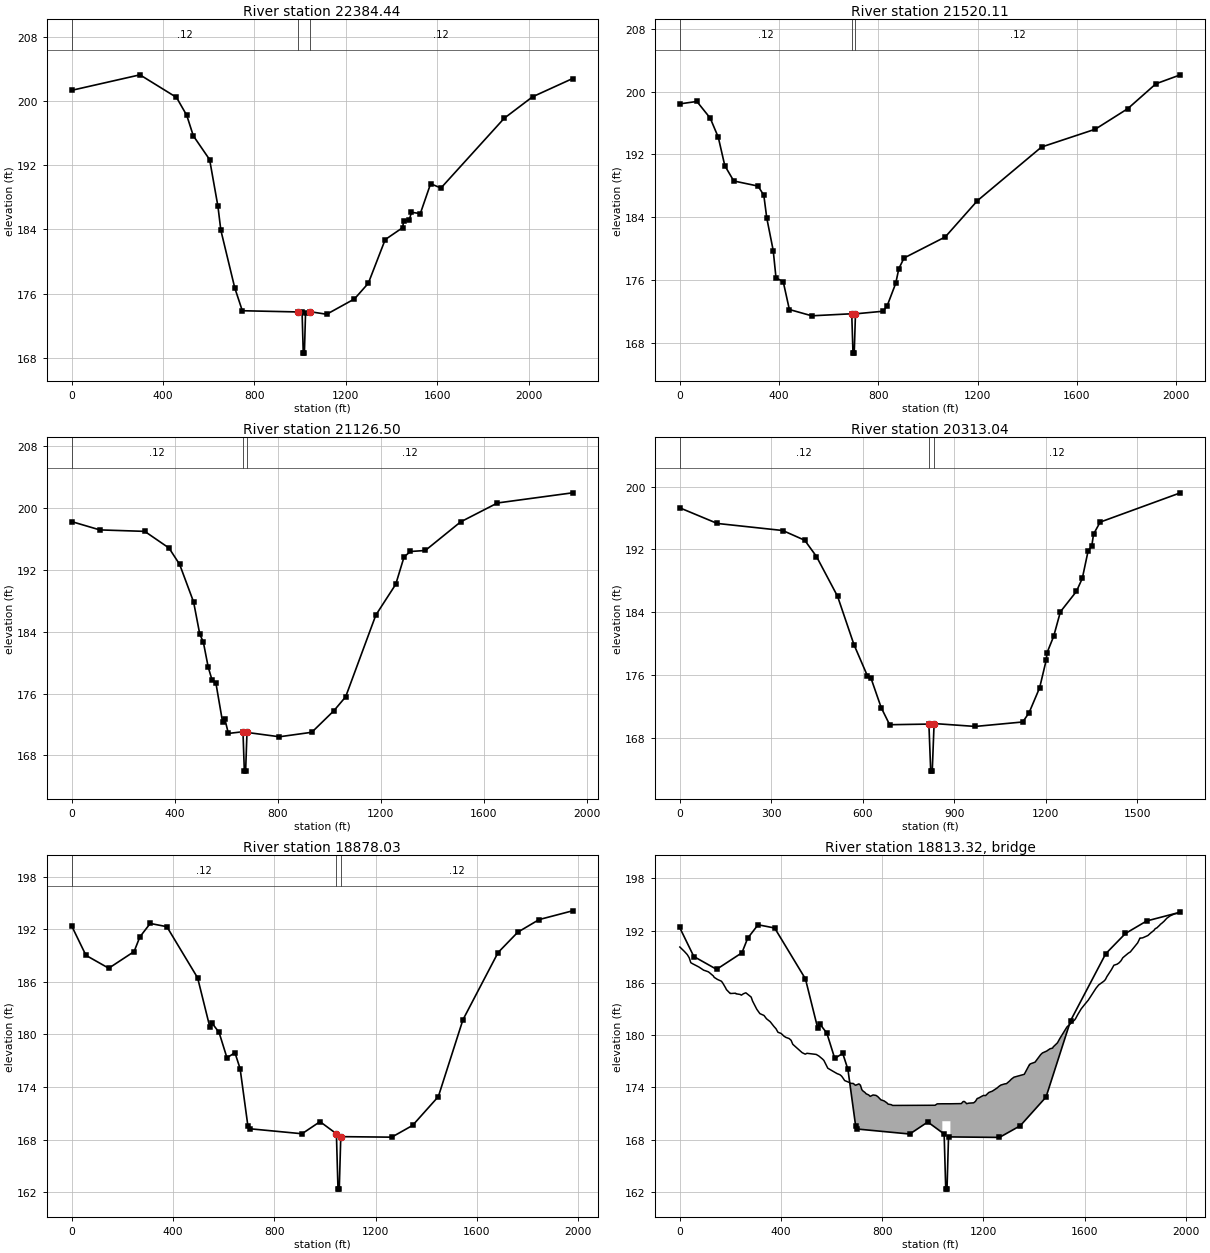
Type RM Length L Ch R = 1 ,22384.44,898.58,887.77,740.31
XS GIS Cut Line= 2
      1859930.19      358986.923     1858362.318      357454.685
#Sta/Elev= 30
       0  201.32   298.8  203.25   458.6  200.44  503.53  198.21  532.26  195.66
  603.77  192.69  640.14  186.87  652.77  183.91  713.66  176.73  746.82  173.87
  988.71  173.72 1008.52  173.68 1013.61  168.59 1018.61  168.59 1023.62   173.6
 1043.51  173.75 1116.08  173.43 1237.81  175.34  1298.4  177.29 1372.34  182.73
 1448.95  184.22 1453.07   185.1 1477.45  185.16 1487.27  186.13 1526.05  185.97
 1571.16  189.69 1616.32  189.15 1893.33  197.84 2017.21  200.51 2192.25  202.78
#Mann= 3 , 0 , 0
       0     .12       0  988.71    .055       0 1043.51     .12       0
Bank Sta=988.71,1043.51
Exp/Cntr=.3,.1

Type RM Length L Ch R = 1 ,21520.11,346.22,393.61,401.33
XS GIS Cut Line= 3
     1860393.424       357726.39      1859195.25      357619.489
     1858642.931      357022.629
#Sta/Elev= 30
       0  198.43   69.62  198.74  123.32  196.62  155.84  194.18  182.03  190.57
  218.18  188.62  315.92  187.97  339.14   186.8  350.98  183.91  376.96  179.77
   388.2  176.28  417.27   175.8  441.99  172.26  532.22  171.46   693.1  171.72
  698.11  166.71  703.11  166.71  708.11  171.71  818.59  172.04  835.58  172.72
  870.14  175.59  882.67  177.46  903.74  178.82 1069.68   181.5 1198.99  186.11
 1457.08  192.94  1673.6  195.21 1804.67  197.83 1917.68  200.99 2016.14  202.13
#Mann= 3 , 0 , 0
       0     .12       0   693.1    .055       0  708.11     .12       0
Bank Sta=693.1,708.11
Exp/Cntr=.3,.1

Type RM Length L Ch R = 1 ,21126.50,631.1,813.46,760.19
XS GIS Cut Line= 2
     1860451.329      357557.131     1858629.569      356875.641
#Sta/Elev= 30
       0  198.21  109.14  197.14  283.67  196.95  377.79   194.8  419.09  192.69
  473.46  187.82  497.31  183.68  511.24  182.64  530.25   179.4  545.12  177.74
  559.96  177.37  585.88  172.34  594.22  172.76  608.52  170.84  665.21  171.06
  670.49  165.97  675.49  165.97  680.77  170.97  806.72  170.41  932.43  170.99
 1017.87  173.76 1063.96  175.57 1181.18  186.13  1258.5  190.11 1290.96  193.66
  1315.8  194.35 1373.41  194.48 1510.35  198.17 1653.64  200.62 1945.05  201.93
#Mann= 3 , 0 , 0
       0     .12       0  665.21    .055       0  680.77     .12       0
Bank Sta=665.21,680.77
Exp/Cntr=.3,.1

Type RM Length L Ch R = 1 ,20313.04,1371.91,1435.01,1263.97
XS GIS Cut Line= 2
     1860566.496      357357.053     1859515.299      356097.511
#Sta/Elev= 30
       0  197.31  123.42  195.31  337.96  194.41  409.97  193.17  448.46   191.1
  517.56  186.03  571.35  179.87  615.24  175.91  627.11   175.6  660.42  171.86
  688.16  169.68  816.72  169.76  822.71  163.77  827.71  163.77  833.77  169.83
  968.62  169.46 1124.16  170.03 1144.84   171.2 1179.45  174.38 1200.89  177.88
 1203.71  178.84 1225.45  180.93  1247.5  184.06  1299.9  186.65 1319.29  188.32
 1338.23  191.79 1350.42  192.44 1356.01  193.94 1377.72  195.48 1640.57  199.21
#Mann= 3 , 0 , 0
       0     .12       0  816.72    .055       0  833.77     .12       0
Bank Sta=816.72,833.77
Exp/Cntr=.5,.3

Type RM Length L Ch R = 1 ,18878.03,138.92,141.32,146.4
XS GIS Cut Line= 6
     1862020.893      356647.382     1861807.864       356580.81
     1861541.577        356416.6     1860756.032      355757.542
      1860574.07      355631.056     1860403.203      355537.855
#Sta/Elev= 30
    -.99  192.37    55.3  189.02  145.31  187.55  245.46  189.45   268.2  191.12
  309.17  192.66  374.78  192.29  496.44  186.45  544.39  180.86  552.86   181.3
  581.02  180.23  612.26  177.33  643.81  177.91  664.27  176.08  695.06  169.53
  702.07  169.23   908.8  168.66  979.96  170.04 1044.57  168.66 1050.89  162.34
 1055.89  162.34 1061.88  168.33 1263.14  168.27 1345.47  169.61 1447.26   172.9
 1544.43  181.67 1683.24  189.34 1761.01  191.66 1845.21   193.1 1977.21   194.1
#Mann= 3 , 0 , 0
    -.99     .12       0 1044.57    .055       0 1061.88     .12       0
Bank Sta=1044.57,1061.88
Exp/Cntr=.5,.3

Type RM Length L Ch R = 3 ,18813.32,,,
BEGIN DESCRIPTION:
SR 1614 (NCDOT # 58)
END DESCRIPTION:
Bridge Culvert--1,0,-1,-1, 0
Deck Dist Width WeirC Skew NumUp NumDn MinLoCord MaxHiCord MaxSubmerge Is_Ogee
52.06,25.3,2.6,0,188,188,171.94,,.95,0,0,0,,
       0     2.5   17.72   29.37   36.98   43.35   51.22   71.01   75.16   94.06
   94.23  101.81  113.04  117.35  132.43  135.79  148.76  164.67  170.42  181.31
  184.01  199.07  199.66  202.38  220.47  222.44  223.21  238.05  243.35  251.39
  260.85  281.88  287.47   298.7  304.09   315.9  316.31  332.63  342.46  357.26
  365.25  371.82  380.18  387.84  400.06   411.8  418.71     432  439.77  446.39
  483.49  491.75  495.66  502.46  538.96  549.41  563.94  569.31   579.3  584.73
  600.86  601.45  601.74  602.87  622.62  626.21   633.3  639.32  643.14  651.45
  670.21  673.34  685.27  685.34  694.08  707.84  713.81  719.24   723.3  731.51
  736.57  746.16  752.36  763.57  775.22     782  794.76   807.2  817.79  823.11
   835.4   840.9 1008.73 1017.14 1037.39 1069.39 1112.41 1119.84 1124.39 1129.63
 1133.36 1141.97 1161.35 1168.34 1175.16 1181.69 1194.51 1200.66 1208.36  1220.8
 1227.47 1234.49 1253.38 1263.55 1265.87 1267.98 1283.94  1290.9 1303.14 1310.43
 1320.46 1361.25 1381.79 1382.25 1386.18 1403.71 1406.02 1426.12 1433.03 1450.19
 1452.87 1463.11 1473.52 1475.58 1492.39 1501.86 1527.38 1528.88 1529.68 1535.07
 1557.57 1560.44 1561.74 1563.86  1573.2  1586.3  1599.7 1614.93 1617.26 1619.73
 1644.69 1655.34  1674.4  1675.8 1681.73 1687.88 1705.91 1715.38 1728.24 1736.09
 1743.74 1750.72  1772.7 1780.62 1783.54 1809.51 1818.59  1819.5 1820.87  1829.1
 1849.94 1860.11 1873.54 1878.76 1886.57 1890.31 1896.26 1899.26 1903.63 1905.75
 1912.93 1924.32 1925.26 1926.56 1938.14 1955.26 1965.08  1978.2
  190.11  190.04  189.61  189.24  188.88  188.31  188.18  187.88  187.82  187.46
  187.45  187.38  187.26  187.16  186.79  186.63  186.39  186.18  185.94   185.4
  185.23  184.78  184.79  184.78  184.81  184.73  184.74  184.67  184.59  184.75
  184.86  184.37  183.91  183.29  182.97  182.48  182.47  182.26  181.88  181.54
  181.25     181  180.73  180.33   180.2  179.88  179.75  179.61  179.41  178.95
  177.99  177.87  177.82  177.92  177.79  177.61  177.26   177.1  176.51  176.21
  175.93  175.92  175.91   175.9  175.57  175.54  175.45   175.3  175.15  174.79
  174.57  174.48  174.46  174.46  174.25  174.41  174.26  173.75  173.61  173.43
  173.27  173.15  172.98  173.14  173.09  172.96  172.58  172.46  172.25  172.09
  172.03  171.94  171.96  172.12  172.13  172.13  172.15  172.39  172.39  172.27
  172.14   172.2  172.24  172.41  172.73   172.8  173.01  173.09  173.07  173.42
   173.5  173.57  173.93  174.18  174.21  174.27  174.41  174.44  174.74  174.96
  175.18  175.51  176.63  176.62  176.72   176.9  176.99  177.77  177.96  178.18
  178.24  178.44  178.52  178.65  179.12  179.62  180.84   180.9  180.93  181.08
  181.66  181.75   181.8  181.89  182.39  183.02  183.51  184.04  184.16  184.26
  185.38  185.76  186.15  186.19  186.37  186.72  187.52  188.02  188.14   188.3
  188.54  188.88  189.41  189.55  189.66  190.59  191.14  191.12  191.13  191.16
  191.43   191.7  192.01  192.21  192.33  192.45   192.6  192.72   192.8  192.86
  193.04  193.41  193.43  193.45  193.69  193.91  193.96  194.26
                                                                                
                                                                                
                                                                                
                                                                                
                                                                                
                                                                                
                                                                                
                                                                                
                                                                                
                                  170.13  170.13
                                                                                
                                                                                
                                                                                
                                                                                
                                                                                
                                                                                
                                                                                
                                                                                
                                                                
       0     2.5   17.72   29.37   36.98   43.35   51.22   71.01   75.16   94.06
   94.23  101.81  113.04  117.35  132.43  135.79  148.76  164.67  170.42  181.31
  184.01  199.07  199.66  202.38  220.47  222.44  223.21  238.05  243.35  251.39
  260.85  281.88  287.47   298.7  304.09   315.9  316.31  332.63  342.46  357.26
  365.25  371.82  380.18  387.84  400.06   411.8  418.71     432  439.77  446.39
  483.49  491.75  495.66  502.46  538.96  549.41  563.94  569.31   579.3  584.73
  600.86  601.45  601.74  602.87  622.62  626.21   633.3  639.32  643.14  651.45
  670.21  673.34  685.27  685.34  694.08  707.84  713.81  719.24   723.3  731.51
  736.57  746.16  752.36  763.57  775.22     782  794.76   807.2  817.79  823.11
   835.4   840.9 1008.73 1017.14 1037.39 1069.39 1112.41 1119.84 1124.39 1129.63
 1133.36 1141.97 1161.35 1168.34 1175.16 1181.69 1194.51 1200.66 1208.36  1220.8
 1227.47 1234.49 1253.38 1263.55 1265.87 1267.98 1283.94  1290.9 1303.14 1310.43
 1320.46 1361.25 1381.79 1382.25 1386.18 1403.71 1406.02 1426.12 1433.03 1450.19
 1452.87 1463.11 1473.52 1475.58 1492.39 1501.86 1527.38 1528.88 1529.68 1535.07
 1557.57 1560.44 1561.74 1563.86  1573.2  1586.3  1599.7 1614.93 1617.26 1619.73
 1644.69 1655.34  1674.4  1675.8 1681.73 1687.88 1705.91 1715.38 1728.24 1736.09
 1743.74 1750.72  1772.7 1780.62 1783.54 1809.51 1818.59  1819.5 1820.87  1829.1
 1849.94 1860.11 1873.54 1878.76 1886.57 1890.31 1896.26 1899.26 1903.63 1905.75
 1912.93 1924.32 1925.26 1926.56 1938.14 1955.26 1965.08  1978.2
  190.11  190.04  189.61  189.24  188.88  188.31  188.18  187.88  187.82  187.46
  187.45  187.38  187.26  187.16  186.79  186.63  186.39  186.18  185.94   185.4
  185.23  184.78  184.79  184.78  184.81  184.73  184.74  184.67  184.59  184.75
  184.86  184.37  183.91  183.29  182.97  182.48  182.47  182.26  181.88  181.54
  181.25     181  180.73  180.33   180.2  179.88  179.75  179.61  179.41  178.95
  177.99  177.87  177.82  177.92  177.79  177.61  177.26   177.1  176.51  176.21
  175.93  175.92  175.91   175.9  175.57  175.54  175.45   175.3  175.15  174.79
  174.57  174.48  174.46  174.46  174.25  174.41  174.26  173.75  173.61  173.43
  173.27  173.15  172.98  173.14  173.09  172.96  172.58  172.46  172.25  172.09
  172.03  171.94  171.96  172.12  172.13  172.13  172.15  172.39  172.39  172.27
  172.14   172.2  172.24  172.41  172.73   172.8  173.01  173.09  173.07  173.42
   173.5  173.57  173.93  174.18  174.21  174.27  174.41  174.44  174.74  174.96
  175.18  175.51  176.63  176.62  176.72   176.9  176.99  177.77  177.96  178.18
  178.24  178.44  178.52  178.65  179.12  179.62  180.84   180.9  180.93  181.08
  181.66  181.75   181.8  181.89  182.39  183.02  183.51  184.04  184.16  184.26
  185.38  185.76  186.15  186.19  186.37  186.72  187.52  188.02  188.14   188.3
  188.54  188.88  189.41  189.55  189.66  190.59  191.14  191.12  191.13  191.16
  191.43   191.7  192.01  192.21  192.33  192.45   192.6  192.72   192.8  192.86
  193.04  193.41  193.43  193.45  193.69  193.91  193.96  194.26
                                                                                
                                                                                
                                                                                
                                                                                
                                                                                
                                                                                
                                                                                
                                                                                
                                                                                
                                  170.13  170.13
                                                                                
                                                                                
                                                                                
                                                                                
                                                                                
                                                                                
                                                                                
                                                                                
                                                                
BR Coef=-1 , 1 , 0 ,, 0 ,,,.8,0,1.2,0,
WSPro=,,,, 1 ,,,, 0 ,,,, 0 ,,,,-1 ,-1 ,-1 , 0 , 0 , 0 , 0 , 0
BC Design=,, 0 ,, 0 ,,,,,,

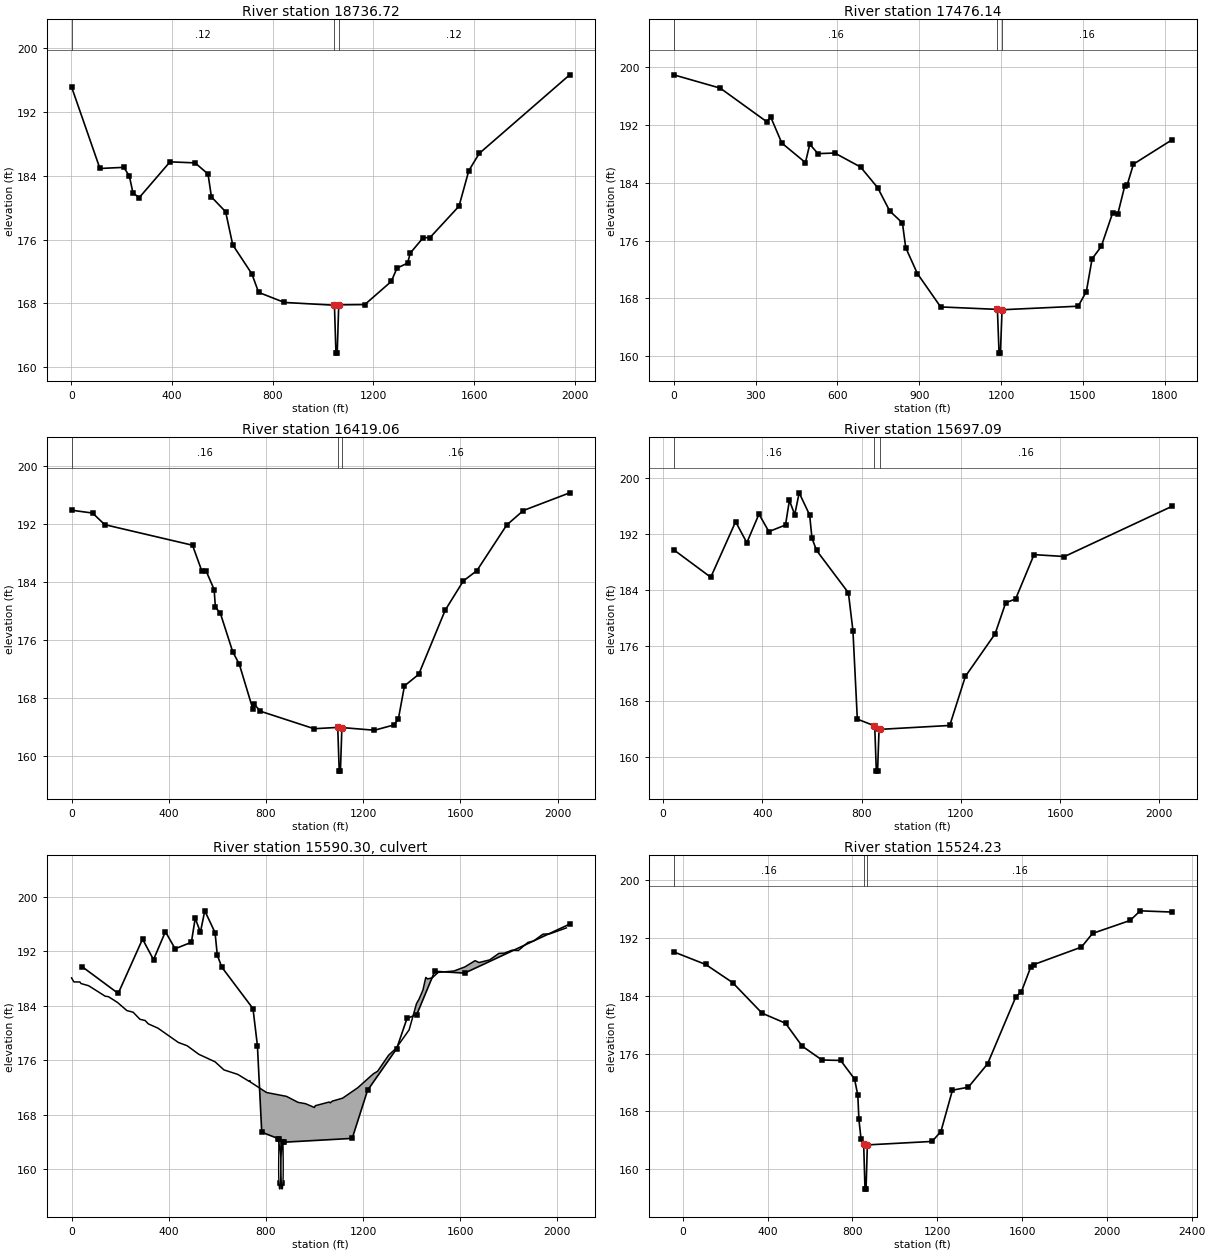
Type RM Length L Ch R = 1 ,18736.72,1246.21,1260.58,1203.06
XS GIS Cut Line= 6
     1862122.969      356554.182      1861909.94       356487.61
     1861643.654        356323.4     1860858.109      355664.341
     1860676.146      355537.855     1860505.279      355444.655
#Sta/Elev= 30
     .99  195.12  113.53  184.91  208.48  185.05  230.34  183.97  244.94  181.83
  269.82  181.26  391.92  185.74  491.51  185.61  542.92  184.21  556.37  181.34
  612.78  179.49     641  175.34  716.94  171.71  743.79  169.39  845.73  168.13
 1044.89  167.78 1050.89  161.78 1055.89  161.78 1061.94  167.83 1165.43  167.86
 1270.56  170.76 1293.37  172.43 1335.18  173.05 1346.21  174.32 1397.94  176.26
 1423.65  176.23 1539.66  180.19 1578.42  184.63 1619.79  186.79 1979.19  196.64
#Mann= 3 , 0 , 0
     .99     .12       0 1044.89    .055       0 1061.94     .12       0
Bank Sta=1044.89,1061.94
Exp/Cntr=.5,.3

Type RM Length L Ch R = 1 ,17476.14,1081.35,1057.08,1000.56
XS GIS Cut Line= 3
     1862393.351      355873.451     1862197.368      355151.873
     1861248.627      354639.643
#Sta/Elev= 30
       0  198.88  170.67  197.04  340.77  192.41  355.72  193.04  396.24  189.46
  482.83  186.76  498.76  189.29  528.76     188  590.36  188.08  684.98  186.15
  747.72  183.29  791.84  180.08  838.41  178.42  850.45  175.01   893.1  171.44
   978.5  166.83 1186.52  166.49 1192.56  160.45 1197.56  160.45 1203.55  166.44
 1482.67  166.93 1512.58  168.96  1533.6  173.47 1567.16  175.18 1609.33  179.86
 1627.75  179.65 1653.56  183.58 1662.49  183.71 1685.26  186.55 1825.91  189.89
#Mann= 3 , 0 , 0
       0     .16       0 1186.52    .055       0 1203.55     .16       0
Bank Sta=1186.52,1203.55
Exp/Cntr=.3,.1

Type RM Length L Ch R = 1 ,16419.06,710.75,721.97,607.9
XS GIS Cut Line= 2
     1863368.817      354550.559     1861484.699      353744.352
#Sta/Elev= 30
       0  193.87   86.44  193.48  136.41  191.88  497.62  189.04  536.01  185.47
  554.35  185.42  586.53  182.93  591.68  180.49  611.87  179.68  662.84  174.36
  690.23  172.61  745.61  166.46  749.82  167.15  777.25  166.14  997.58  163.73
 1095.05  163.91 1101.08  157.88 1106.08  157.88 1112.09  163.89  1245.9  163.52
 1325.26  164.24 1344.16  165.02 1369.54  169.64  1428.1  171.23 1537.26  180.09
 1611.85  184.12  1667.3  185.53 1790.46  191.84 1858.73  193.83 2049.36  196.27
#Mann= 3 , 0 , 0
       0     .16       0 1095.05    .055       0 1112.09     .16       0
Bank Sta=1095.05,1112.09
Exp/Cntr=.5,.3

Type RM Length L Ch R = 1 ,15697.09,170.44,172.86,151.8
XS GIS Cut Line= 2
     1863493.847      353516.512     1861486.156      353563.863
#Sta/Elev= 30
   42.55  189.76  191.97  185.81  292.19  193.79  337.33  190.77  386.29  194.88
  426.23  192.37  493.26  193.32  508.99  196.85  530.45   194.8  548.38  197.94
  590.67  194.75  599.97  191.42  618.43  189.67  746.85  183.58  765.11  178.15
  782.85  165.43  849.87   164.5  852.94  164.44  859.42  157.96  864.42  157.96
  870.51  164.05  873.97  163.96 1155.37  164.52 1218.47  171.57 1338.37  177.69
    1381  182.15 1420.96  182.69  1495.2  189.06 1618.04  188.79  2050.8  195.99
#Mann= 3 , 0 , 0
   42.55     .16       0  849.87    .055       0  873.97     .16       0
Bank Sta=849.87,873.97
Exp/Cntr=.5,.3

Type RM Length L Ch R = 2 ,15590.30,,,
BEGIN DESCRIPTION:
SR 1621 (NCDOT # 107)
END DESCRIPTION:
Bridge Culvert--1,0,-1,-1, 0
Deck Dist Width WeirC Skew NumUp NumDn MinLoCord MaxHiCord MaxSubmerge Is_Ogee
81.79,50,2.6,0, 60, 60,169.06,,.95,0,0,0,,
       0    9.48   34.15    38.9   70.31  138.46   151.9  188.88  227.76  253.48
   281.5  302.56  315.97  355.53  439.52  476.12  523.81  590.64  627.28  684.12
     731  734.37  735.16  802.56  885.06  932.68  962.94  999.93 1003.15 1060.29
 1064.87 1073.33 1115.89 1178.18 1242.76 1259.63 1305.29 1335.35  1389.7 1420.09
 1429.99 1446.64 1458.25 1465.27 1484.78 1509.22 1574.08 1619.04 1661.07  1677.7
 1721.18 1759.23 1782.05 1813.58 1839.62 1878.59 1901.95 1940.48 1969.64 2036.96
  188.09   187.5  187.49  187.26  186.94   185.4  185.33  184.49  183.29  183.05
  182.01  181.84  181.34  180.71  178.61  178.12  176.87  175.77  174.58  173.92
   172.9  173.01  172.82  171.26  170.69  169.81  169.62  169.06  169.32  169.86
  169.74  169.99  170.43  171.96  174.02  174.37  176.74  177.73  180.46  184.32
  184.93  186.32  188.16  187.94   188.1   188.9   189.1   189.7  190.62  190.35
  190.73  191.69  191.73  192.16  192.12   193.3  193.51  194.51  194.57  195.43
                                                                                
                                                                                
                                                                                
                                                                                
                                                                                
                                                                                
       0    9.48   34.15    38.9   70.31  138.46   151.9  188.88  227.76  253.48
   281.5  302.56  315.97  355.53  439.52  476.12  523.81  590.64  627.28  684.12
     731  734.37  735.16  802.56  885.06  932.68  962.94  999.93 1003.15 1060.29
 1064.87 1073.33 1115.89 1178.18 1242.76 1259.63 1305.29 1335.35  1389.7 1420.09
 1429.99 1446.64 1458.25 1465.27 1484.78 1509.22 1574.08 1619.04 1661.07  1677.7
 1721.18 1759.23 1782.05 1813.58 1839.62 1878.59 1901.95 1940.48 1969.64 2036.96
  188.09   187.5  187.49  187.26  186.94   185.4  185.33  184.49  183.29  183.05
  182.01  181.84  181.34  180.71  178.61  178.12  176.87  175.77  174.58  173.92
   172.9  173.01  172.82  171.26  170.69  169.81  169.62  169.06  169.32  169.86
  169.74  169.99  170.43  171.96  174.02  174.37  176.74  177.73  180.46  184.32
  184.93  186.32  188.16  187.94   188.1   188.9   189.1   189.7  190.62  190.35
  190.73  191.69  191.73  192.16  192.12   193.3  193.51  194.51  194.57  195.43
                                                                                
                                                                                
                                                                                
                                                                                
                                                                                
                                                                                
Multiple Barrel Culv=3,6.5,9.23,50,.027,.7,1,36,2,157.07,157.05, 2,Culvert #1  , 0 ,81.79
  857.06  857.06  866.79  866.79
BC Design=,, 0 ,, 0 ,,,,,,

Type RM Length L Ch R = 1 ,15524.23,1437.7,1456.03,1451.74
XS GIS Cut Line= 2
     1863646.237      353387.111     1861297.617      353415.522
#Sta/Elev= 30
  -42.55  190.05  108.21  188.31  234.95  185.81  373.99  181.58  484.67  180.19
  562.93  177.03  656.63  175.11  744.57  175.05  810.08  172.49  825.58  170.24
  830.58  166.96  840.53  164.23  853.22  163.47  859.42  157.27  864.42  157.27
  870.53  163.38 1175.74  163.86 1217.27  165.22 1271.77  170.94 1346.53  171.35
 1437.22  174.57 1571.32  183.88 1596.62  184.52 1640.88  187.95  1654.9  188.29
 1879.96  190.71 1932.45   192.6 2109.53  194.39 2157.29  195.72 2306.24  195.55
#Mann= 3 , 0 , 0
  -42.55     .16       0  853.22    .055       0  870.53     .16       0
Bank Sta=853.22,870.53
Exp/Cntr=.5,.3

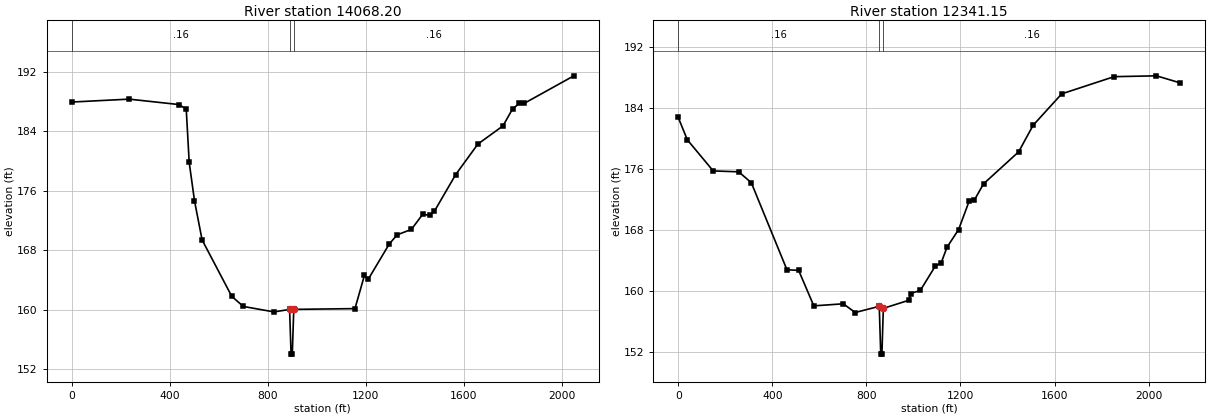
Type RM Length L Ch R = 1 ,14068.20,1592.09,1727.05,1618.91
XS GIS Cut Line= 2
     1863900.021      352290.475      1861911.27      351798.022
#Sta/Elev= 30
       0  187.91  233.96   188.3  438.14  187.57  467.13  186.94  479.17  179.81
  500.77  174.66  531.78   169.4  652.88  161.82  700.19  160.46  825.07  159.73
  888.88  160.06  894.88  154.06  899.88  154.06  905.89  160.07  1155.6  160.17
 1194.28  164.64  1210.8  164.17 1295.43  168.84 1327.21  170.07    1386  170.81
 1431.41  172.81 1461.67  172.72 1479.28  173.22 1566.65  178.17 1657.04  182.26
  1759.6  184.71 1798.65  186.98 1826.21  187.72  1846.1  187.73 2048.81  191.43
#Mann= 3 , 0 , 0
       0     .16       0  888.88    .055       0  905.89     .16       0
Bank Sta=888.88,905.89
Exp/Cntr=.3,.1

Type RM Length L Ch R = 1 ,12341.15,1103.01,1110.17,987.71
XS GIS Cut Line= 2
     1864193.598      350803.647     1862138.556      350225.963
#Sta/Elev= 30
       0  182.73   38.71   179.8  148.57  175.73  257.07  175.61  310.61  174.19
  462.27  162.78  511.89  162.71  576.44  158.06  701.85  158.33  752.39  157.19
  854.72     158  860.98  151.74  865.98  151.74  871.97  157.73  981.05   158.8
  987.83  159.67 1029.54  160.09  1092.2  163.23  1118.1  163.71 1143.15  165.76
 1192.11  168.05 1237.68  171.84 1258.26  171.87 1298.17  174.04 1447.41  178.23
 1508.74   181.7 1630.43  185.82 1853.02  188.07 2033.34  188.18 2134.69  187.25
#Mann= 3 , 0 , 0
       0     .16       0  854.72    .055       0  871.97     .16       0
Bank Sta=854.72,871.97
Exp/Cntr=.3,.1