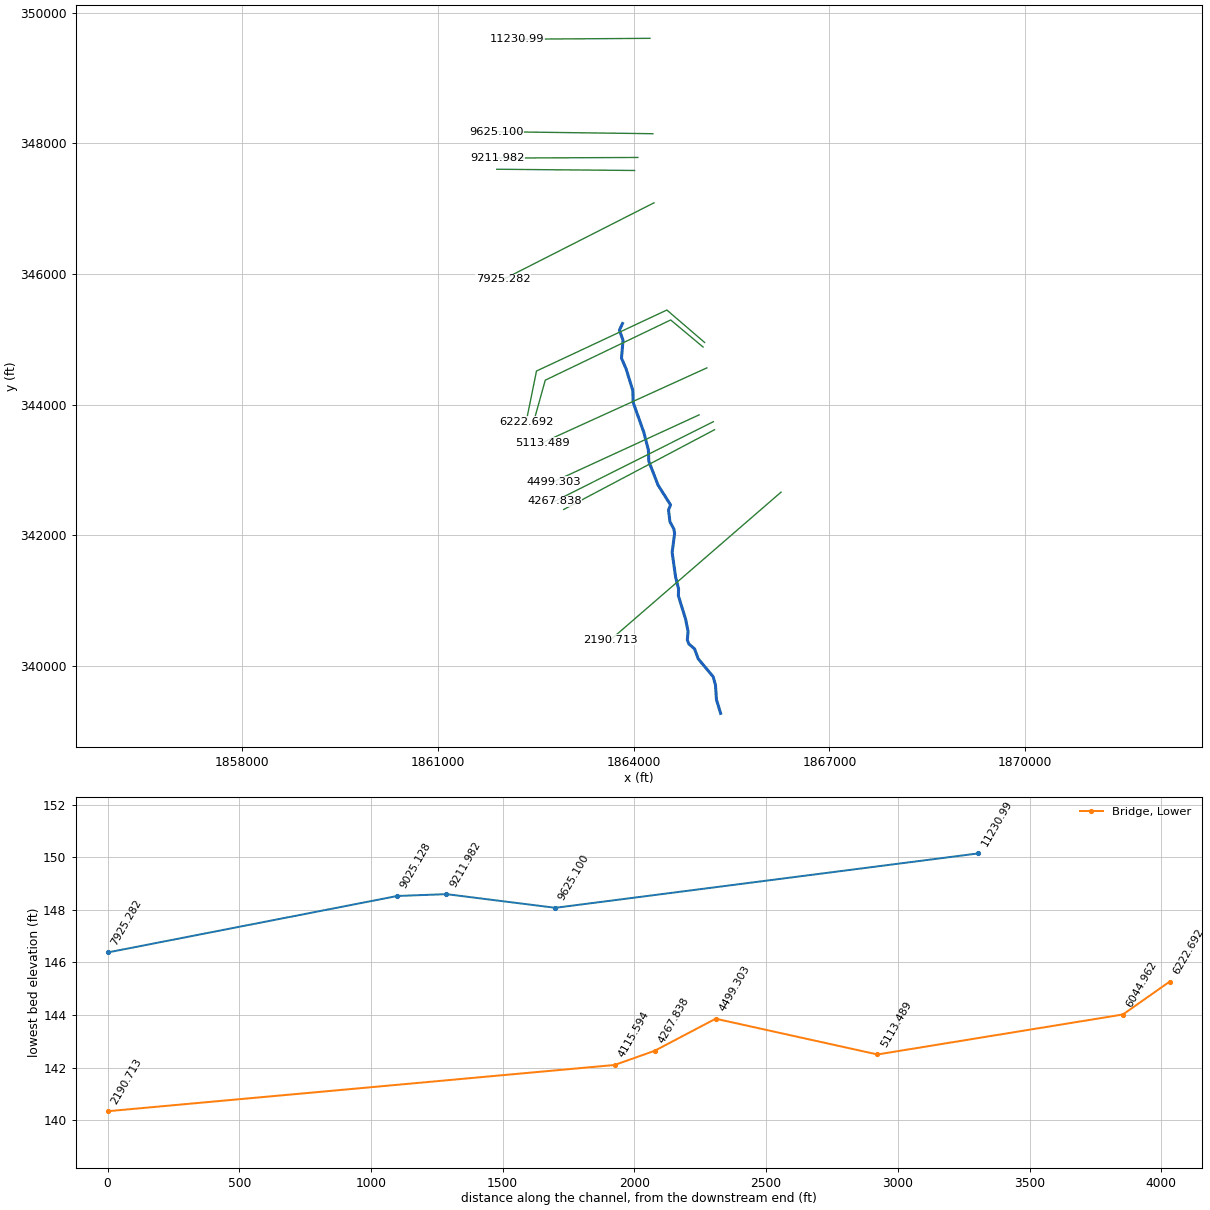
HEC-RAS study bridge.prj: Bridge Creek to Leith Creek

--- bridge.g02 (geometry) --- (continued)

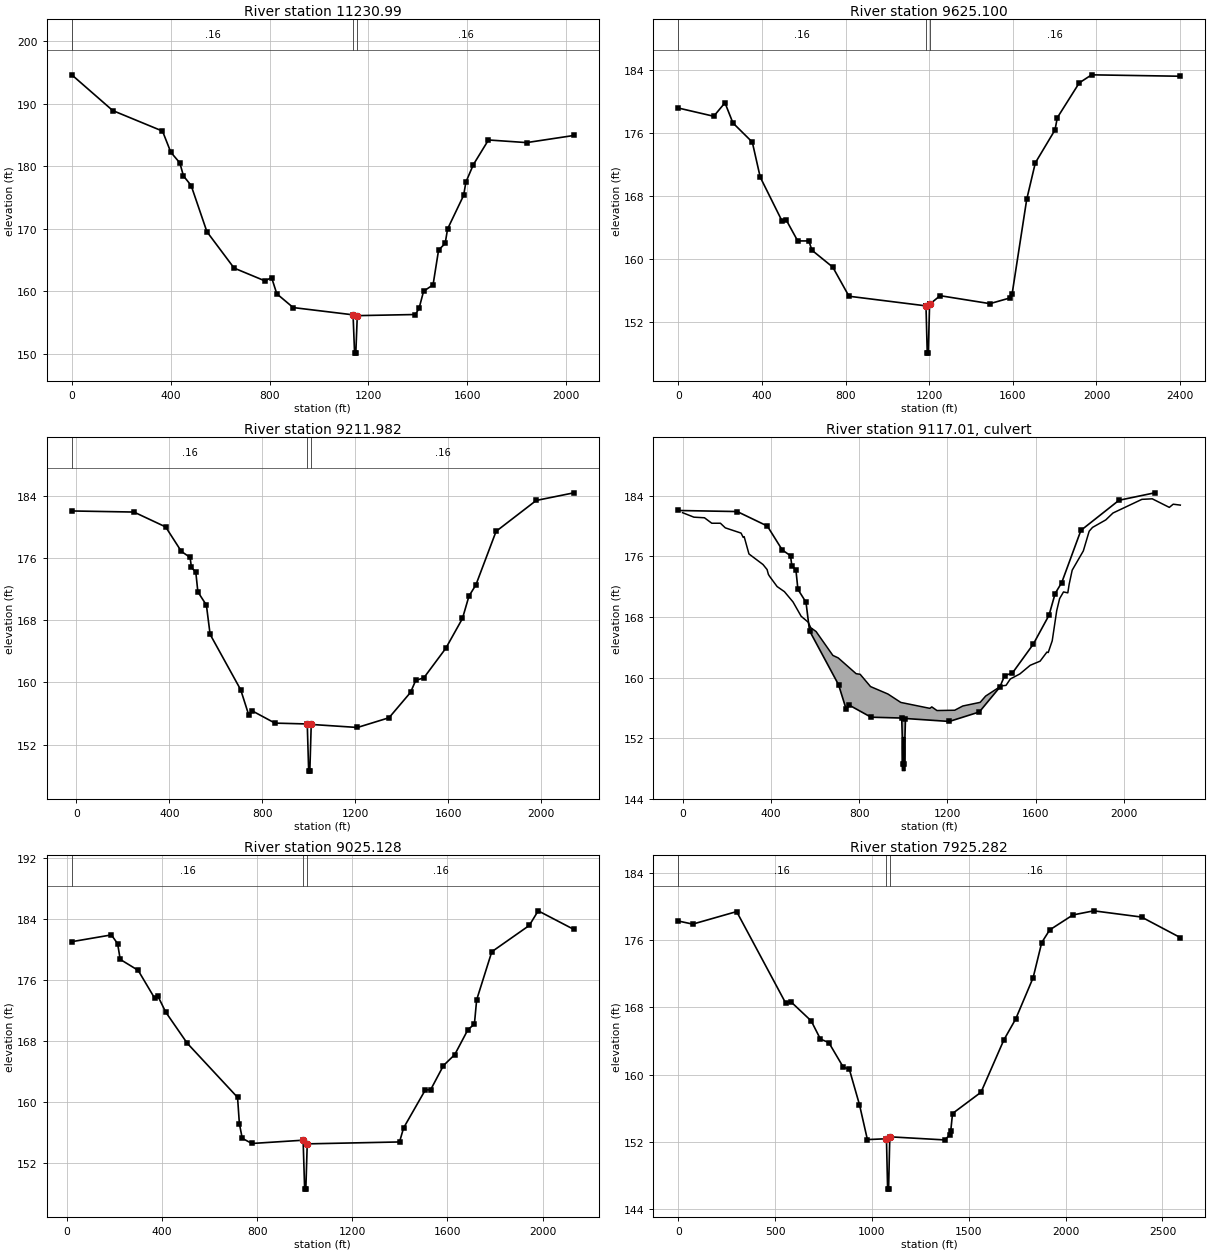
Type RM Length L Ch R = 1 ,11230.99,1794.48,1605.89,1462.88
XS GIS Cut Line= 2
     1864250.745      349610.873     1862219.638       349597.51
#Sta/Elev= 30
       0  194.62   165.7  188.91  367.03  185.63  400.71  182.25  437.31  180.54
  451.64  178.48  482.97  176.93  546.69  169.55  656.69  163.74  781.09   161.7
  808.52  162.21  829.45  159.63  895.69  157.43 1137.97  156.27 1144.09  150.15
 1149.09  150.15 1155.08  156.14 1390.02  156.32 1404.99  157.31 1423.27  160.04
 1461.57  161.06 1483.99  166.63 1510.52  167.67 1520.31  169.99 1585.21  175.35
 1594.45  177.48 1624.51  180.26 1685.72  184.21 1840.15  183.79 2031.15  184.93
#Mann= 3 , 0 , 0
       0     .16       0 1137.97    .055       0 1155.08     .16       0
Bank Sta=1137.97,1155.08
Exp/Cntr=.3,.1

Type RM Length L Ch R = 1 ,9625.100,432.63,413.12,411.75
XS GIS Cut Line= 2
     1864295.287      348149.901     1861894.483      348181.081
#Sta/Elev= 30
       0  179.19  169.74  178.14  223.44  179.85   261.6  177.29  354.18  174.86
  391.97  170.42  495.94  164.87  517.05  164.95  571.36  162.32  624.58  162.32
  639.41  161.14  739.17  158.99  816.51   155.3  1183.7  154.08 1184.79  154.09
  1190.8  148.08  1195.8  148.08    1202  154.28  1202.9  154.29 1252.25  155.37
  1490.6  154.36 1587.37  155.09  1596.3  155.53 1666.58  167.61  1707.7  172.23
 1801.66   176.4 1812.82  177.96  1917.8  182.38 1976.86   183.4 2401.01  183.22
#Mann= 3 , 0 , 0
       0     .16       0  1183.7    .055       0  1202.9     .16       0
Bank Sta=1183.7,1202.9
Exp/Cntr=.5,.3

Type RM Length L Ch R = 1 ,9211.982,193.84,186.86,195.93
XS GIS Cut Line= 2
     1864065.777       347786.12     1861906.563       347776.65
#Sta/Elev= 30
  -19.63  182.03   247.7  181.89  384.11  179.98   451.7  176.83  489.23  176.06
  495.04  174.77   513.8  174.16   522.7  171.63  559.35  169.93  575.35  166.17
   706.9  159.05  741.64   155.8  755.93  156.35  854.11  154.77  993.13  154.66
  999.19   148.6 1004.19   148.6 1010.19   154.6 1208.97  154.21 1344.78  155.46
 1437.34  158.72 1459.55  160.26 1494.57  160.59 1588.84  164.38 1660.66  168.22
 1688.38  171.08 1718.34  172.53 1805.18  179.41 1977.86  183.38  2139.6  184.36
#Mann= 3 , 0 , 0
  -19.63     .16       0  993.13    .055       0 1010.19     .16       0
Bank Sta=993.13,1010.19
Exp/Cntr=.5,.3

Type RM Length L Ch R = 2 ,9117.01 ,,,
BEGIN DESCRIPTION:
SR 1620 (NCDOT 82 2067)
END DESCRIPTION:
Bridge Culvert--1,0,-1,-1, 0
Deck Dist Width WeirC Skew NumUp NumDn MinLoCord MaxHiCord MaxSubmerge Is_Ogee
72.47,45,2.6,0, 60, 60,155.65,,.95,0,0,0,,
       0   51.31   99.24  132.33  171.52  193.62  265.08  274.65  279.13  300.81
  364.33  383.06  388.85  394.07  428.37  461.44  500.53  537.44   569.3  580.59
  604.99  681.14  705.44  786.43  804.83  851.77  930.62  988.96 1120.49 1129.43
 1152.85 1233.14 1269.86 1348.66 1373.42 1443.65 1465.84 1485.17 1528.66 1575.52
 1620.18 1651.22 1656.99  1675.2 1695.52 1708.69 1726.24 1745.75 1751.88 1765.67
 1816.13 1842.63 1857.82 1917.89 1950.58 2081.58 2128.58  2205.8 2223.37 2255.63
  181.74  181.15  181.07  180.35  180.35  179.74  179.05  178.49  178.58   176.3
  174.91  174.24  173.61  173.36     172  171.33  169.97  168.08   167.3  166.58
  166.07  162.92  162.59  160.51  160.43  158.81  157.83  156.72  155.94  156.13
  155.65  155.69  156.25  156.73  157.56  158.89  158.97  159.81  160.48  161.62
  162.16  163.36   163.3  164.85  168.82  170.41  171.29  171.17   172.3  174.16
   176.7   179.3   179.8  180.79   181.7   183.5  183.57  182.44  182.86  182.74
                                                                                
                                                                                
                                                                                
                                                                                
                                                                                
                                                                                
       0   51.31   99.24  132.33  171.52  193.62  265.08  274.65  279.13  300.81
  364.33  383.06  388.85  394.07  428.37  461.44  500.53  537.44   569.3  580.59
  604.99  681.14  705.44  786.43  804.83  851.77  930.62  988.96 1120.49 1129.43
 1152.85 1233.14 1269.86 1348.66 1373.42 1443.65 1465.84 1485.17 1528.66 1575.52
 1620.18 1651.22 1656.99  1675.2 1695.52 1708.69 1726.24 1745.75 1751.88 1765.67
 1816.13 1842.63 1857.82 1917.89 1950.58 2081.58 2128.58  2205.8 2223.37 2255.63
  181.74  181.15  181.07  180.35  180.35  179.74  179.05  178.49  178.58   176.3
  174.91  174.24  173.61  173.36     172  171.33  169.97  168.08   167.3  166.58
  166.07  162.92  162.59  160.51  160.43  158.81  157.83  156.72  155.94  156.13
  155.65  155.69  156.25  156.73  157.56  158.89  158.97  159.81  160.48  161.62
  162.16  163.36   163.3  164.85  168.82  170.41  171.29  171.17   172.3  174.16
   176.7   179.3   179.8  180.79   181.7   183.5  183.57  182.44  182.86  182.74
                                                                                
                                                                                
                                                                                
                                                                                
                                                                                
                                                                                
Multiple Barrel Culv=1,4.5,,45,.027,.7,1,2,2,147.66,147.64, 3,Culvert #1  , 0 ,72.47
  996.69  996.69 1001.69 1001.69 1006.69 1006.69
BC Design=,, 0 ,, 0 ,,,,,,

Type RM Length L Ch R = 1 ,9025.128,991.48,1099.85,1157.36
XS GIS Cut Line= 2
     1864015.306      347586.609     1861903.443      347605.549
#Sta/Elev= 30
   19.63     181  186.29  181.89  212.57  180.73  223.34  178.68  298.78  177.24
  368.76  173.56  382.15  173.84  414.87  171.76   504.9  167.69     717  160.57
  724.62  157.14  736.66   155.2  777.17  154.52  992.77  154.95  999.19  148.53
 1004.19  148.53 1010.13  154.47 1398.32  154.72 1415.39  156.56 1507.06  161.56
  1529.2  161.57 1583.16  164.75 1630.55  166.18 1685.95  169.45 1713.29  170.19
 1722.76  173.37 1786.41  179.68 1944.11  183.13 1981.54  185.05 2131.58  182.61
#Mann= 3 , 0 , 0
   19.63     .16       0  992.77    .055       0 1010.13     .16       0
Bank Sta=992.77,1010.13
Exp/Cntr=.5,.3

Type RM Length L Ch R = 1 ,7925.282,,,
XS GIS Cut Line= 2
     1864311.976      347091.313     1862001.237      345917.003
#Sta/Elev= 30
       0  178.26   74.79  177.89  301.57  179.38  553.96  168.53  581.06  168.67
   686.5  166.38  734.07  164.22  777.43   163.8  852.82  160.85  882.68  160.68
  935.67  156.42  976.54  152.27 1074.97  152.37 1080.96  146.38 1085.96  146.38
 1092.18   152.6 1375.88  152.23 1400.88  152.81 1406.65  153.24 1416.03  155.37
 1563.07   157.9 1680.86  164.11 1742.14  166.61 1832.04  171.51 1876.56   175.7
 1917.74   177.2 2037.57  178.98 2145.14  179.47 2391.74  178.73 2592.01  176.29
#Mann= 3 , 0 , 0
       0     .16       0 1074.97    .055       0 1092.18     .16       0
Bank Sta=1074.97,1092.18
Exp/Cntr=.3,.1

River Reach=Bridge          ,Lower
Junct Up Dn=2               ,
Reach XY= 30
     1863830.082      345243.287     1863782.772        345141.6
     1863838.137      344985.534     1863814.099      344711.531
      1863883.59      344551.936     1863987.191      344219.369
     1863993.762      344031.805     1864156.043      343577.179
     1864226.574      343305.217     1864232.821      343132.936
     1864374.727      342767.146     1864565.752       342464.39
     1864534.613      342387.113     1864556.325      342206.446
     1864617.984      342091.832     1864627.876      342026.037
      1864590.21      341736.326     1864643.566       341358.95
     1864688.818      341177.192     1864685.614      341072.717
     1864795.161      340718.903     1864833.886       340525.89
     1864822.862      340393.461     1864846.914      340334.469
     1864933.867      340258.009      1864990.05      340105.639
     1865218.137      339833.235     1865253.841      339706.966
     1865269.442      339478.733     1865333.142      339270.719

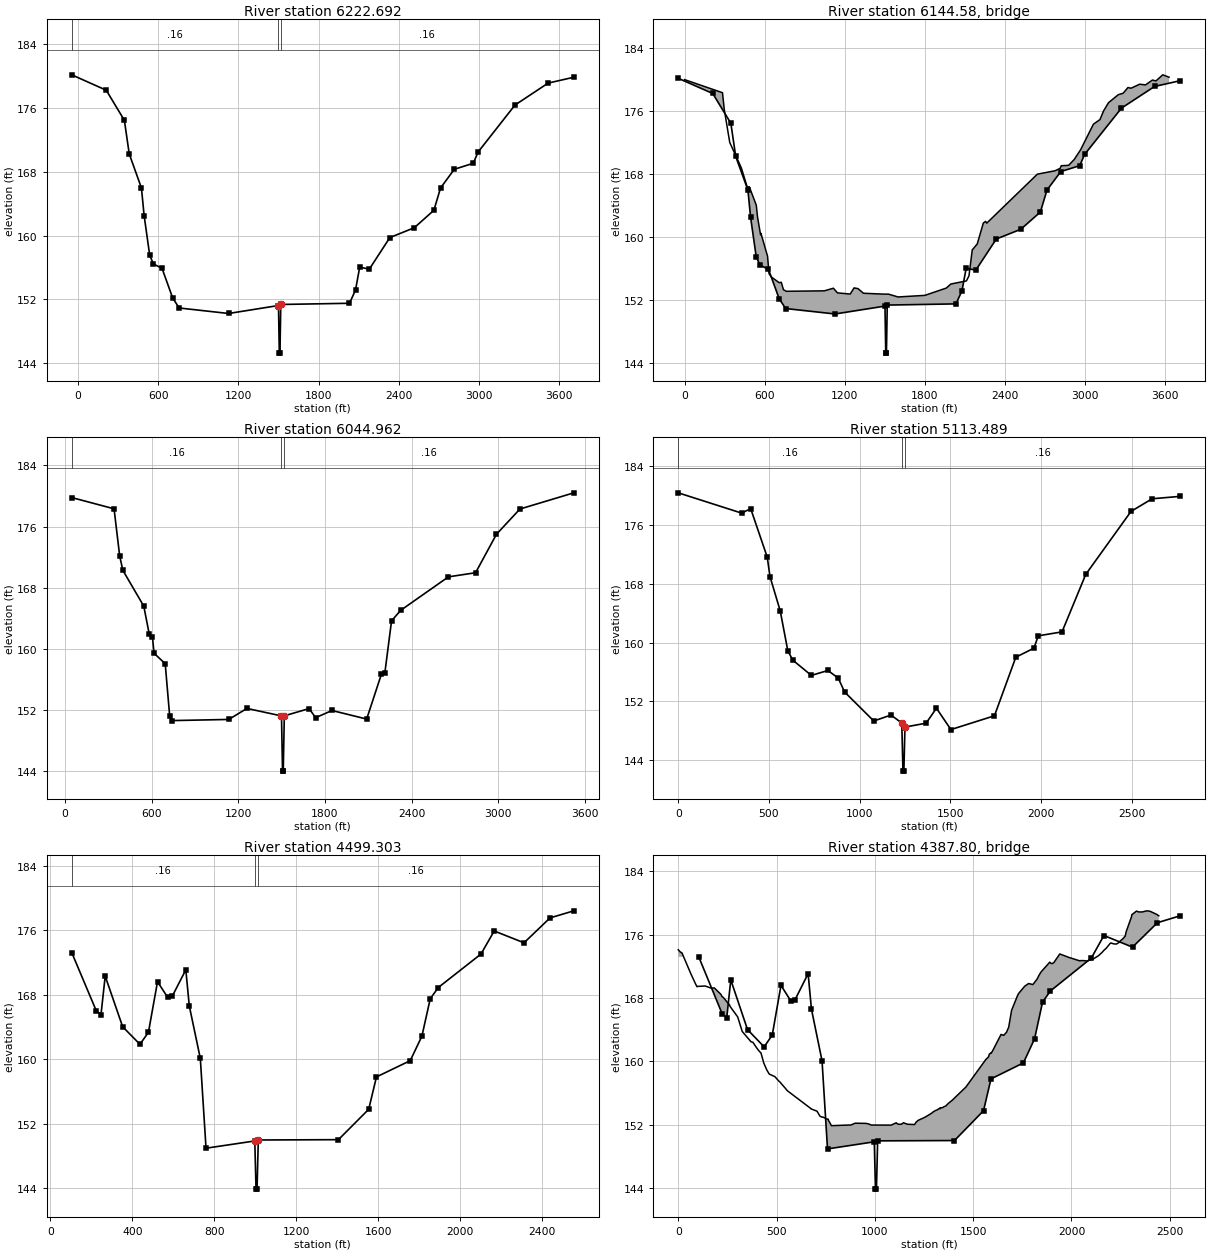
Type RM Length L Ch R = 1 ,6222.692,173.37,177.73,183.53
XS GIS Cut Line= 4
      1865087.48      344952.624     1864509.395       345448.96
     1862512.373      344514.681     1862354.713      343738.061
#Sta/Elev= 30
  -47.55  180.16  210.71  178.23  346.46  174.45  382.66  170.25  474.12  165.97
   494.1  162.52  536.06  157.53  564.13  156.44  628.02  155.91  707.59   152.2
  756.35  150.93 1126.59  150.24 1500.27  151.24 1506.24  145.27 1511.24  145.27
 1517.34  151.37 2031.77  151.52 2076.99  153.18 2108.22  156.05 2180.42   155.8
 2334.08  159.76 2517.13  160.99 2663.78  163.18 2713.36  165.97 2816.77  168.32
 2958.47  169.07 2995.06  170.49 3270.86  176.37 3518.64  179.12  3711.6  179.86
#Mann= 3 , 0 , 0
  -47.55     .16       0 1500.27    .055       0 1517.34     .16       0
Bank Sta=1500.27,1517.34
Exp/Cntr=.5,.3

Type RM Length L Ch R = 3 ,6144.58 ,,,
BEGIN DESCRIPTION:
Railroad (assumed same as SR619)
END DESCRIPTION:
Bridge Culvert--1,0,-1,-1, 0
Deck Dist Width WeirC Skew NumUp NumDn MinLoCord MaxHiCord MaxSubmerge Is_Ogee
65.56,25.1,2.6,0, 60, 60,152.4,,.95,0,0,0,,
       0  283.83  297.24  338.04  425.44  469.78  484.15  536.91  546.23  568.87
  571.89  621.37  632.05  648.36  707.66   723.9  740.36  761.52 1046.66 1114.09
 1144.73 1239.98 1268.79 1298.17 1339.41 1491.24 1526.24 1580.97 1596.68  1798.3
 1959.46 1993.27    2110 2129.22 2153.69 2191.17 2236.58 2253.55 2262.11 2641.21
 2773.26 2811.35 2820.35 2875.17 2916.81 2965.06 3061.14 3110.09 3136.78 3173.83
 3247.36 3283.24 3319.82 3342.84 3407.16 3450.61 3503.21 3528.64 3580.29 3627.26
  179.99  178.33  176.19  172.02  168.76   166.3   166.4  164.05  162.54   160.3
  160.47  157.56  155.37  154.95  154.22  154.26  153.32  153.12  153.18  153.51
  152.92  152.77  153.55  153.46  152.87  152.76  152.76  152.49   152.4   152.6
  153.53  154.04  154.44  155.07  158.37  159.13  161.78     162  161.77  167.99
  168.42  168.72  169.06  169.11  169.84  171.09  174.34  174.92  176.01  177.06
  178.08  178.26  178.99   178.9  179.41  179.32  179.94  179.82   180.6   180.3
                                                                                
                                                                                
                                          150.76  150.76
                                                                                
                                                                                
                                                                                
       0  283.83  297.24  338.04  425.44  469.78  484.15  536.91  546.23  568.87
  571.89  621.37  632.05  648.36  707.66   723.9  740.36  761.52 1046.66 1114.09
 1144.73 1239.98 1268.79 1298.17 1339.41 1491.24 1526.24 1580.97 1596.68  1798.3
 1959.46 1993.27    2110 2129.22 2153.69 2191.17 2236.58 2253.55 2262.11 2641.21
 2773.26 2811.35 2820.35 2875.17 2916.81 2965.06 3061.14 3110.09 3136.78 3173.83
 3247.36 3283.24 3319.82 3342.84 3407.16 3450.61 3503.21 3528.64 3580.29 3627.26
  179.99  178.33  176.19  172.02  168.76   166.3   166.4  164.05  162.54   160.3
  160.47  157.56  155.37  154.95  154.22  154.26  153.32  153.12  153.18  153.51
  152.92  152.77  153.55  153.46  152.87  152.76  152.76  152.49   152.4   152.6
  153.53  154.04  154.44  155.07  158.37  159.13  161.78     162  161.77  167.99
  168.42  168.72  169.06  169.11  169.84  171.09  174.34  174.92  176.01  177.06
  178.08  178.26  178.99   178.9  179.41  179.32  179.94  179.82   180.6   180.3
                                                                                
                                                                                
                                          150.76  150.76
                                                                                
                                                                                
                                                                                
BR Coef=-1 , 1 , 0 ,, 0 ,,,.8,0,1.2,0,
WSPro=,,,, 1 ,,,, 0 ,,,, 0 ,,,,-1 ,-1 ,-1 , 0 , 0 , 0 , 0 , 0
BC Design=,, 0 ,, 0 ,,,,,,

Type RM Length L Ch R = 1 ,6044.962,939.74,931.47,915.74
XS GIS Cut Line= 4
     1865064.123      344882.554     1864567.787       345297.14
     1862646.675      344374.539     1862459.819      343703.026
#Sta/Elev= 30
   47.55   179.8  340.31  178.33  378.99  172.18  400.84  170.29  545.88   165.6
  583.73  161.94  606.18  161.52  616.88  159.44  694.26  158.07  725.33   151.2
  742.51  150.63 1134.17  150.78 1259.98  152.22 1499.03  151.24 1506.25  144.02
 1511.25  144.02 1518.48  151.25 1690.27   152.2 1735.26  151.01 1848.72  151.95
 2088.51  150.83 2190.03  156.67 2214.63   156.9 2260.78  163.68 2324.73  165.06
 2654.36  169.43 2842.43  169.97  2986.8     175  3149.1   178.3 3522.45  180.42
#Mann= 3 , 0 , 0
   47.55     .16       0 1499.03    .055       0 1518.48     .16       0
Bank Sta=1499.03,1518.48
Exp/Cntr=.5,.3

Type RM Length L Ch R = 1 ,5113.489,629.49,614.19,611.73
XS GIS Cut Line= 2
     1865121.681      344562.759     1862602.598       343416.86
#Sta/Elev= 30
       0  180.41  349.33  177.65  399.47  178.25   490.7  171.64  505.67  169.01
  562.34  164.31  603.83  158.92  630.88  157.63  733.72  155.54  825.15  156.21
  882.05  155.17  916.99  153.28 1077.89  149.33  1172.7  150.14 1232.16  149.05
 1238.71   142.5 1243.71   142.5 1249.71   148.5 1366.15  149.03 1423.25  151.07
  1502.9  148.16 1743.03  150.04 1860.77  158.02 1960.78  159.25 1984.42  160.93
 2115.43  161.47 2246.27   169.3 2495.77  177.88 2612.11   179.6 2767.47  179.93
#Mann= 3 , 0 , 0
       0     .16       0 1232.16    .055       0 1249.71     .16       0
Bank Sta=1232.16,1249.71
Exp/Cntr=.5,.3

Type RM Length L Ch R = 1 ,4499.303,231.91,231.46,241.75
XS GIS Cut Line= 2
     1865003.303      343843.021     1862777.797      342820.235
#Sta/Elev= 30
   104.2  173.22  223.33  166.02  246.67  165.52  267.31   170.3   352.4  164.02
  436.85  161.84  478.17  163.33  522.51  169.61  571.39  167.69  594.62  167.82
  660.55  171.09  677.46  166.61  731.35  160.08  759.13  148.94  997.06  149.84
 1003.04  143.86 1008.04  143.86 1014.14  149.96 1404.99     150  1552.7  153.77
 1590.56  157.79  1755.4  159.81 1812.23  162.85 1852.87  167.49 1892.28  168.89
  2100.6  173.05 2164.94  175.91 2310.44  174.44 2437.19  177.53 2553.48  178.41
#Mann= 3 , 0 , 0
   104.2     .16       0  997.06    .055       0 1014.14     .16       0
Bank Sta=997.06,1014.14
Exp/Cntr=.5,.3

Type RM Length L Ch R = 3 ,4387.80 ,,,
BEGIN DESCRIPTION:
SR 1619 (NCDOT # 52)
END DESCRIPTION:
Bridge Culvert--1,0,-1,-1, 0
Deck Dist Width WeirC Skew NumUp NumDn MinLoCord MaxHiCord MaxSubmerge Is_Ogee
98.95,25.1,2.6,0,165,165,151.88,,.95,0,0,0,,
       0    9.63   19.18    64.3   89.07   95.48   99.89  137.19  165.65  183.86
  217.15  223.13  227.29  231.66  258.56  260.82  262.99   302.4  325.34  370.61
  379.18     399  399.41  411.84  420.94     435  450.21  462.81  491.59  491.72
  491.81  509.84  518.62  526.67  538.93   542.3  544.81  554.69  674.64  674.73
  705.68  719.91  720.27  721.15  731.31   737.9  755.71  761.99  764.76  767.22
  779.05   879.1  888.55  899.45  955.14  955.36  955.47  970.69  981.03  988.04
 1023.04 1082.99 1108.44 1110.97 1120.47 1131.74 1135.93 1145.14 1145.17 1145.19
 1165.93 1201.98 1209.96 1220.03 1233.89 1234.96 1251.92 1259.77 1285.14 1290.83
 1293.02 1308.56 1316.19 1331.42 1332.11 1333.76 1345.51 1350.43 1361.02 1374.37
 1380.03 1393.13 1398.68 1464.22 1465.38 1465.89 1564.03 1578.59 1582.03 1591.35
 1592.21 1600.37 1641.84  1654.7 1656.01 1669.85  1673.9 1680.65 1695.37 1720.23
 1723.21  1724.9 1726.61 1731.65 1761.83 1778.51 1781.69 1784.73 1803.53 1824.82
 1835.27  1845.9  1889.4 1895.31 1900.55 1909.98 1940.43 1987.12 2042.04  2046.3
 2059.97 2076.82 2081.98 2103.59 2105.86 2108.03 2116.92 2137.19 2154.19 2160.17
 2164.48 2176.24 2196.24 2200.35 2215.48 2228.59 2241.53 2248.18 2259.93 2273.31
 2277.95 2297.04 2305.36 2307.01 2312.62 2330.67 2341.29 2360.41 2377.48 2385.37
 2398.95 2414.52 2434.38 2442.67 2443.85
  174.11  173.85   173.7  171.07  169.74  169.44  169.48  169.53  169.27  169.28
  168.47  168.18  168.12  168.02   167.2  167.17  166.97  165.62  163.79  162.47
  162.43  161.71  161.69  161.29  161.06   159.8  158.93   158.4  158.08  158.08
  158.07  157.56  157.36  157.12  156.78  156.67   156.6   156.3  154.04  154.01
  153.71  153.11   153.1  153.07  152.96  152.95  152.71  152.72   152.5  152.42
  151.88  151.97  152.07  152.19  152.17  152.17  152.17  152.08  151.96  151.96
  151.95  151.95  152.24  152.18  152.05  152.07  152.07  152.25  152.25  152.25
  152.06  152.02  152.33  152.55   152.7  152.72  152.91  153.02   153.4  153.49
  153.56   153.8  153.87   154.1  154.02  154.12  154.17  154.26  154.38  154.71
  154.83  155.08  155.22  156.79  156.84  156.86  160.23  160.59  160.92  161.09
  161.05  161.41  163.41  163.29  163.32  163.69  163.95  164.32  166.46  168.01
  168.17  168.29  168.38   168.6   169.5  169.79  169.84  169.83  169.71  170.39
  170.91  171.33  172.54  172.41  172.35  172.48  173.58  173.14  172.71  172.74
  172.74   172.7  172.72  172.88  172.91  172.91  173.04  173.36  173.74   173.9
  174.03  174.29   174.9  174.97  174.85  174.83  175.03  175.23  175.46  175.84
  176.38  177.71  178.29  178.55  178.65     179  178.89  178.89     179  179.03
  178.98   178.8  178.57  178.41  178.41
                                                                                
                                                                                
                                                                                
                                                                                
                                                                                
                                                                          149.96
  149.95
                                                                                
                                                                                
                                                                                
                                                                                
                                                                                
                                                                                
                                                                                
                                                                                
                                                                                
                                        
       0    9.63   19.18    64.3   89.07   95.48   99.89  137.19  165.65  183.86
  217.15  223.13  227.29  231.66  258.56  260.82  262.99   302.4  325.34  370.61
  379.18     399  399.41  411.84  420.94     435  450.21  462.81  491.59  491.72
  491.81  509.84  518.62  526.67  538.93   542.3  544.81  554.69  674.64  674.73
  705.68  719.91  720.27  721.15  731.31   737.9  755.71  761.99  764.76  767.22
  779.05   879.1  888.55  899.45  955.14  955.36  955.47  970.69  981.03  988.04
 1023.04 1082.99 1108.44 1110.97 1120.47 1131.74 1135.93 1145.14 1145.17 1145.19
 1165.93 1201.98 1209.96 1220.03 1233.89 1234.96 1251.92 1259.77 1285.14 1290.83
 1293.02 1308.56 1316.19 1331.42 1332.11 1333.76 1345.51 1350.43 1361.02 1374.37
 1380.03 1393.13 1398.68 1464.22 1465.38 1465.89 1564.03 1578.59 1582.03 1591.35
 1592.21 1600.37 1641.84  1654.7 1656.01 1669.85  1673.9 1680.65 1695.37 1720.23
 1723.21  1724.9 1726.61 1731.65 1761.83 1778.51 1781.69 1784.73 1803.53 1824.82
 1835.27  1845.9  1889.4 1895.31 1900.55 1909.98 1940.43 1987.12 2042.04  2046.3
 2059.97 2076.82 2081.98 2103.59 2105.86 2108.03 2116.92 2137.19 2154.19 2160.17
 2164.48 2176.24 2196.24 2200.35 2215.48 2228.59 2241.53 2248.18 2259.93 2273.31
 2277.95 2297.04 2305.36 2307.01 2312.62 2330.67 2341.29 2360.41 2377.48 2385.37
 2398.95 2414.52 2434.38 2442.67 2443.85
  174.11  173.85   173.7  171.07  169.74  169.44  169.48  169.53  169.27  169.28
  168.47  168.18  168.12  168.02   167.2  167.17  166.97  165.62  163.79  162.47
  162.43  161.71  161.69  161.29  161.06   159.8  158.93   158.4  158.08  158.08
  158.07  157.56  157.36  157.12  156.78  156.67   156.6   156.3  154.04  154.01
  153.71  153.11   153.1  153.07  152.96  152.95  152.71  152.72   152.5  152.42
  151.88  151.97  152.07  152.19  152.17  152.17  152.17  152.08  151.96  151.96
  151.95  151.95  152.24  152.18  152.05  152.07  152.07  152.25  152.25  152.25
  152.06  152.02  152.33  152.55   152.7  152.72  152.91  153.02   153.4  153.49
  153.56   153.8  153.87   154.1  154.02  154.12  154.17  154.26  154.38  154.71
  154.83  155.08  155.22  156.79  156.84  156.86  160.23  160.59  160.92  161.09
  161.05  161.41  163.41  163.29  163.32  163.69  163.95  164.32  166.46  168.01
  168.17  168.29  168.38   168.6   169.5  169.79  169.84  169.83  169.71  170.39
  170.91  171.33  172.54  172.41  172.35  172.48  173.58  173.14  172.71  172.74
  172.74   172.7  172.72  172.88  172.91  172.91  173.04  173.36  173.74   173.9
  174.03  174.29   174.9  174.97  174.85  174.83  175.03  175.23  175.46  175.84
  176.38  177.71  178.29  178.55  178.65     179  178.89  178.89     179  179.03
  178.98   178.8  178.57  178.41  178.41
                                                                                
                                                                                
                                                                                
                                                                                
                                                                                
                                                                          149.96
  149.95
                                                                                
                                                                                
                                                                                
                                                                                
                                                                                
                                                                                
                                                                                
                                                                                
                                                                                
                                        
BR Coef=-1 , 1 , 0 ,, 0 ,,,.8,0,1.2,0,
WSPro=,,,, 1 ,,,, 0 ,,,, 0 ,,,,-1 ,-1 ,-1 , 0 , 0 , 0 , 0 , 0
BC Design=,, 0 ,, 0 ,,,,,,

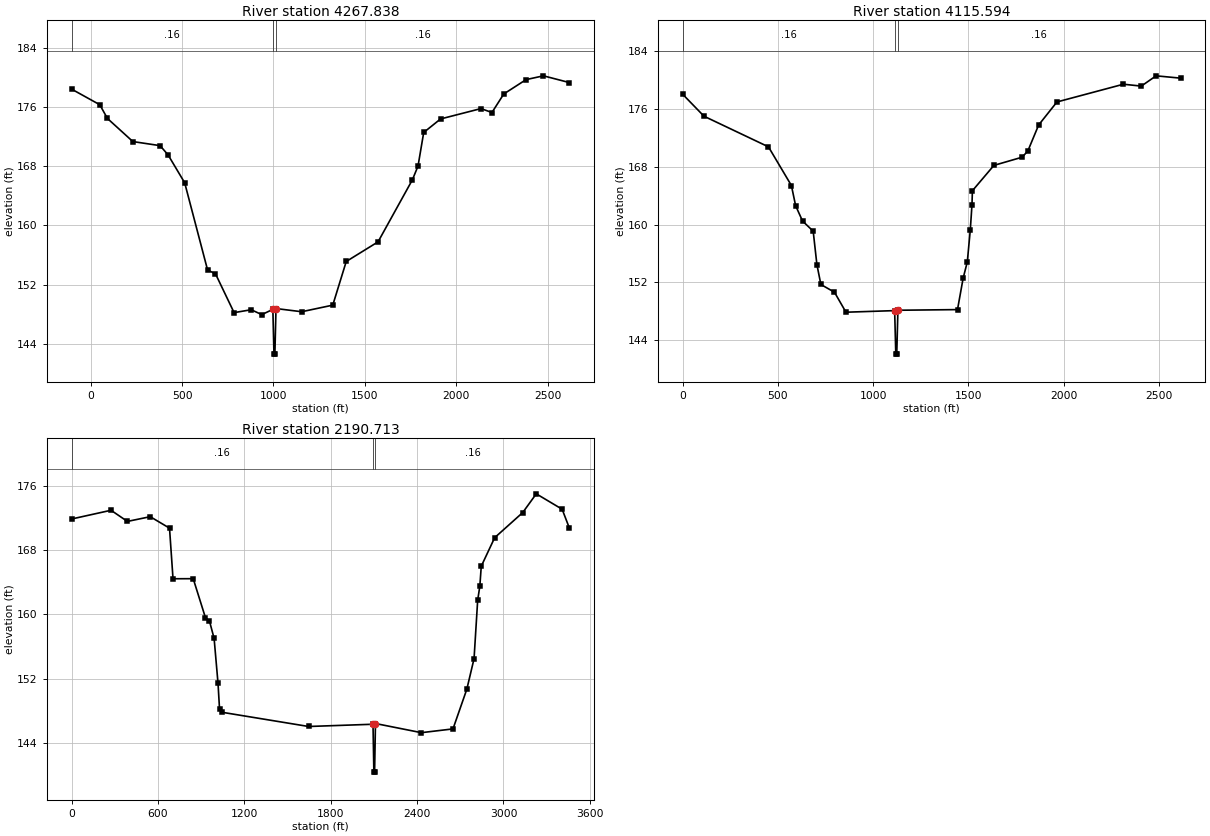
Type RM Length L Ch R = 1 ,4267.838,138.76,152.24,161.16
XS GIS Cut Line= 2
     1865221.119      343738.848     1862787.267      342517.187
#Sta/Elev= 30
  -104.2   178.4   50.26  176.29   91.93  174.44  231.15  171.32  380.03  170.77
  423.55  169.53  514.62  165.76     640  153.98  683.14  153.48  784.84  148.24
  878.64  148.63  936.47  147.97  996.99  148.68 1003.03  142.64 1008.03  142.64
 1014.18  148.79 1154.57  148.36 1324.81  149.25  1398.4  155.14 1572.45  157.79
 1760.46  166.17 1791.14  168.02 1822.22  172.55 1914.34  174.37 2135.36  175.77
 2195.45  175.24 2260.19  177.74 2382.24  179.68 2477.34  180.19 2619.05  179.28
#Mann= 3 , 0 , 0
  -104.2     .16       0  996.99    .055       0 1014.18     .16       0
Bank Sta=996.99,1014.18
Exp/Cntr=.5,.3

Type RM Length L Ch R = 1 ,4115.594,1738.47,1924.88,1986.32
XS GIS Cut Line= 2
     1865240.059      343615.735     1862929.321      342394.074
#Sta/Elev= 30
       0  177.99  111.83  174.96  450.27  170.73  570.69  165.39  592.91   162.6
  629.09  160.49  685.06  159.08  704.56  154.47  725.45  151.72  796.82  150.65
  857.14  147.89 1112.81  148.11 1118.82   142.1 1123.82   142.1 1129.88  148.16
 1442.82  148.25 1472.35  152.58  1494.2  154.83 1509.92  159.24 1518.84  162.73
 1521.07  164.67 1634.02  168.17 1782.06   169.3 1812.14  170.16 1868.88  173.75
 1964.97  176.93 2313.95  179.38 2407.79  179.12 2485.63  180.54  2613.8  180.22
#Mann= 3 , 0 , 0
       0     .16       0 1112.81    .055       0 1129.88     .16       0
Bank Sta=1112.81,1129.88
Exp/Cntr=.3,.1

Type RM Length L Ch R = 1 ,2190.713,1804.34,2190.71,2705.27
XS GIS Cut Line= 2
      1866258.11      342659.241     1863644.324      340395.853
#Sta/Elev= 30
       0   171.9  274.11  172.99  387.95   171.6  546.38  172.19  680.41  170.76
   704.7  164.45  844.96  164.46  929.85   159.6  957.84  159.18  990.12  157.01
  1017.2  151.42 1027.94  148.16 1045.93   147.8 1646.56  146.03 2093.74  146.31
 2099.71  140.34 2104.71  140.34 2110.77   146.4 2429.61  145.26 2649.26  145.73
 2745.33  150.68 2795.55  154.49 2820.68  161.77 2835.74  163.54 2845.54  166.01
 2938.63  169.57 3133.87  172.71 3227.64  175.04 3407.29  173.12 3457.57  170.77
#Mann= 3 , 0 , 0
       0     .16       0 2093.74    .055       0 2110.77     .16       0
Bank Sta=2093.74,2110.77
Exp/Cntr=.3,.1

Chan Stop Cuts= 1